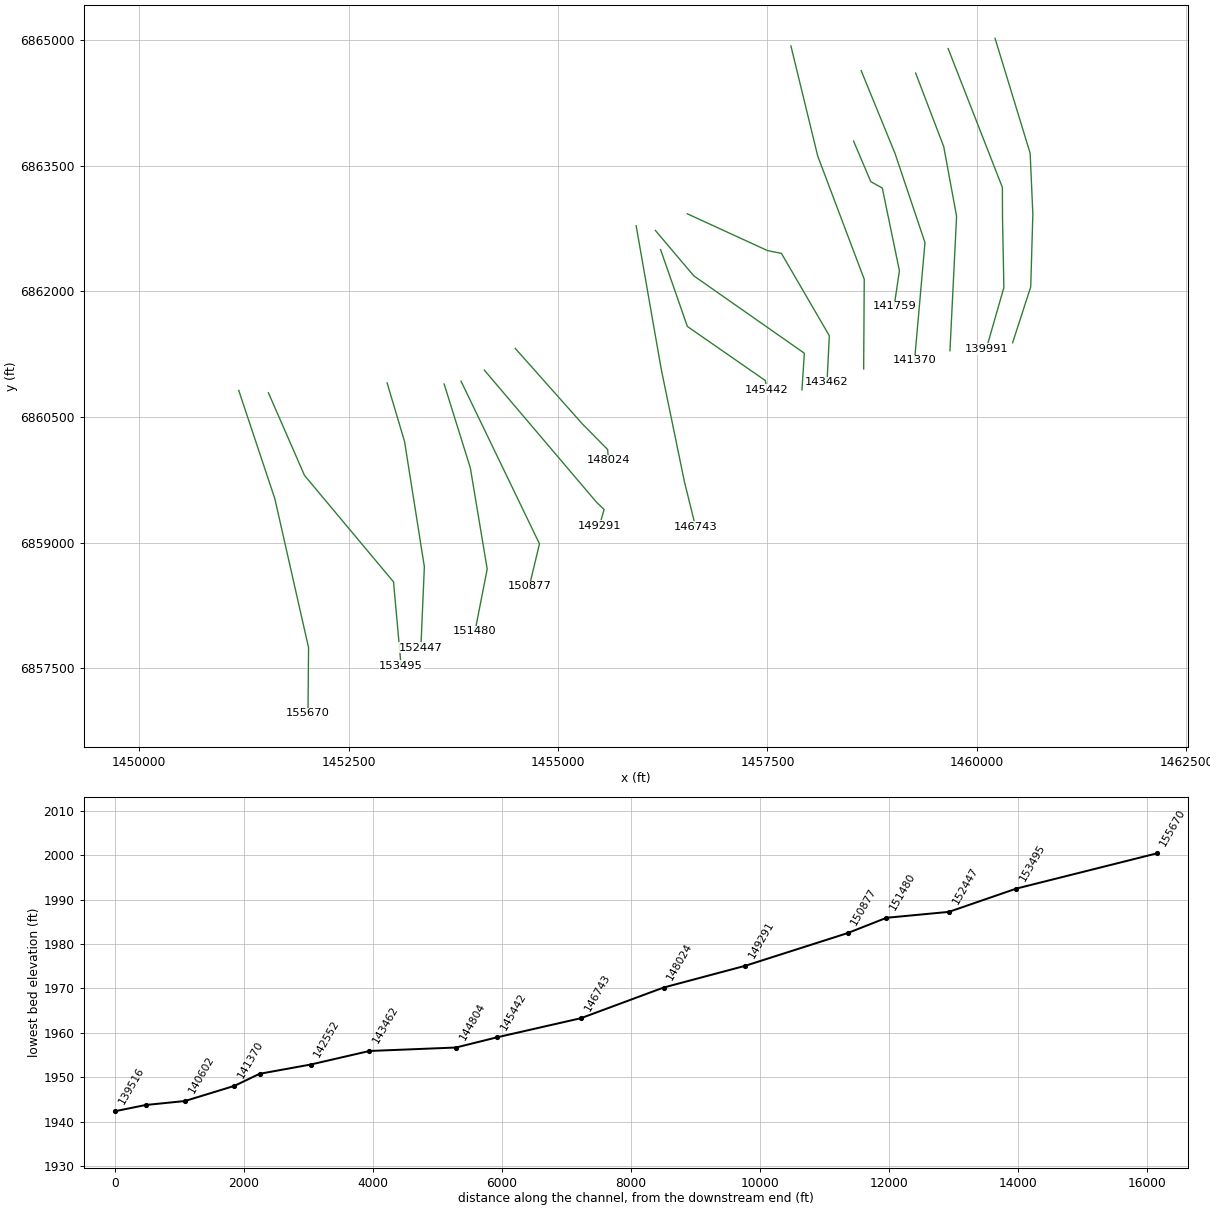
HEC-RAS study Noodle Creek.prj: Noodle Creek Base Level Engineering

--- Noodle Creek.g01 (geometry) --- (continued)

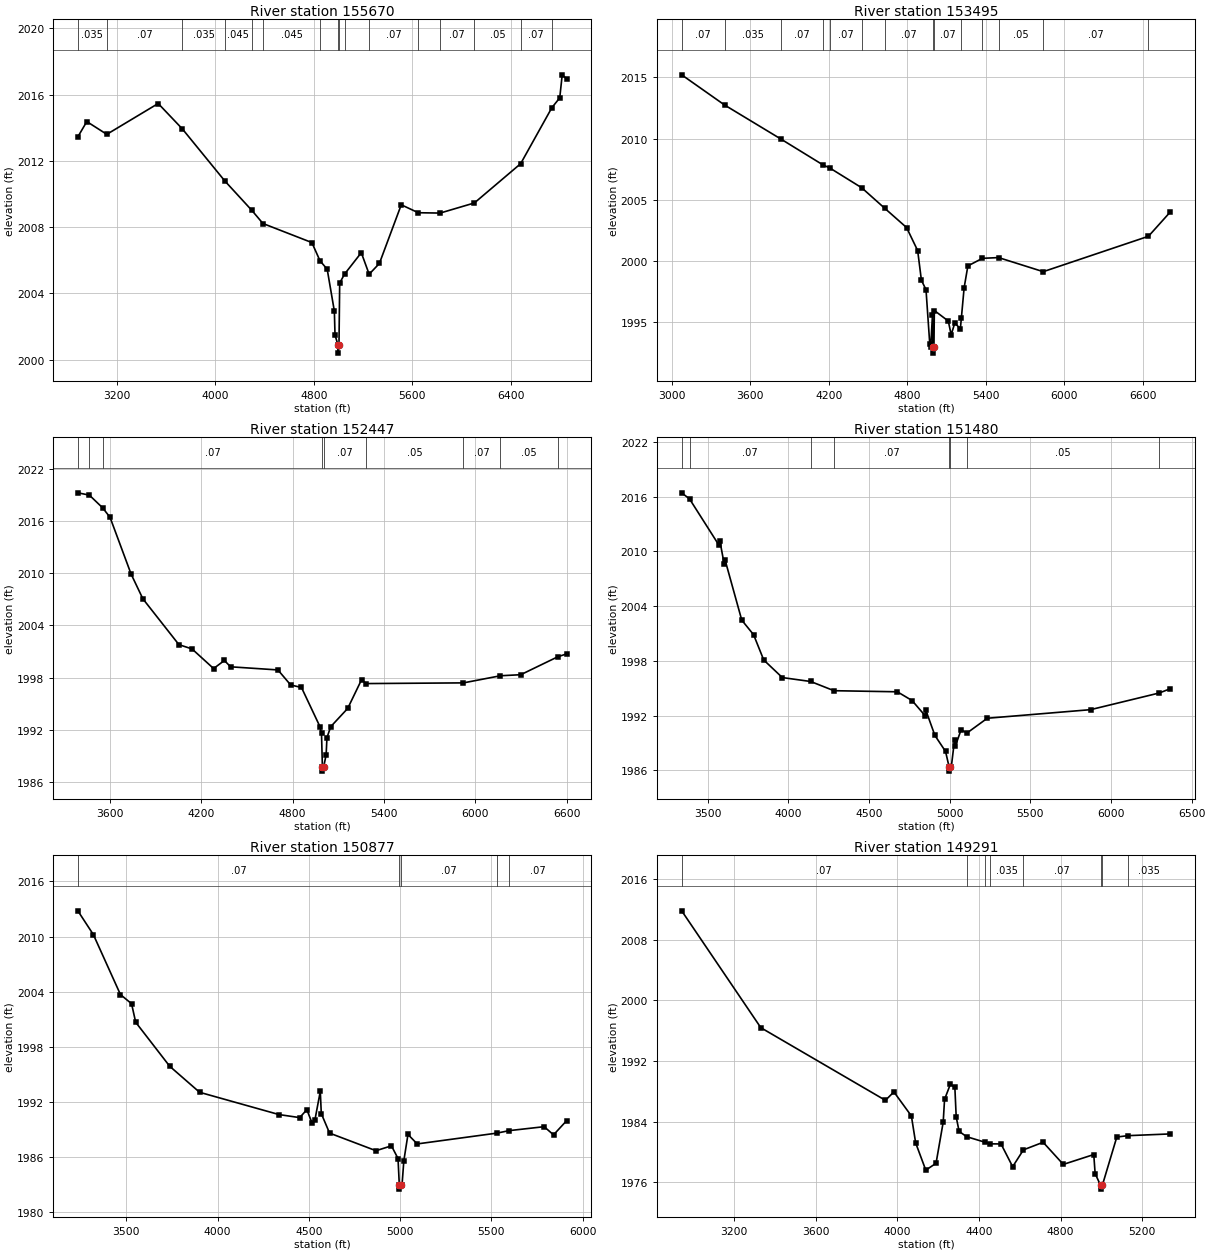
Type RM Length L Ch R = 1 ,155670  ,2175,2175,2175
BEGIN DESCRIPTION:
Mapping XS 93888a68
END DESCRIPTION:
XS GIS Cut Line= 4
      1451189.51      6860817.03      1451620.05       6859525.4
      1452022.83      6857747.62      1452015.89      6856962.99
#Sta/Elev= 30
  2883.2 2013.45    2956 2014.37  3118.4  2013.6  3535.7 2015.46  3731.7 2013.93
  4076.6 2010.79  4296.7 2009.01  4386.5 2008.22  4783.9 2007.07  4850.1 2005.97
  4908.5 2005.46  4966.7 2002.93  4971.9 2001.49    4996  2000.9  4996.5  2000.4
  5004.1  2000.9  5009.9 2004.63  5049.7 2005.17  5185.4 2006.46  5249.2 2005.16
  5332.3 2005.81    5510 2009.35  5648.3 2008.87  5825.8 2008.85  6103.8 2009.46
  6479.8 2011.83  6733.4 2015.21  6797.2  2015.8  6817.2 2017.19  6852.2 2016.95
#Mann= 16 ,-1 , 0
  2883.2    .035       0  3118.4     .07       0  3731.7    .035       0
  4076.6    .045       0  4296.7     .07       0  4386.5    .045       0
  4850.1     .07       0    4996     .07       0  5004.1     .07       0
  5049.7     .16       0  5249.2     .07       0  5648.3     .05       0
  5825.8     .07       0  6103.8     .05       0  6479.8     .07       0
  6733.4    .035       0
Bank Sta=4996,5004.1
XS Rating Curve= 0 ,0
Exp/Cntr=0.3,0.1

Type RM Length L Ch R = 1 ,153495  ,1048,1048,1048
BEGIN DESCRIPTION:
Mapping XS 0cd88bcd
END DESCRIPTION:
XS GIS Cut Line= 4
      1451543.66      6860789.31      1451974.22      6859803.18
      1453036.72      6858532.34      1453126.97      6857532.72
#Sta/Elev= 30
  3075.4  2015.2  3402.8 2012.74  3838.2 2009.93  4156.6 2007.84  4207.1  2007.6
  4451.8 2005.98  4626.2 2004.32    4795 2002.73  4879.6 2000.85  4908.2 1998.43
  4943.4 1997.66    4972 1993.25  4979.4 1992.98  4992.8  1995.6    4996 1992.98
  4996.5 1992.48  5004.1 1992.98  5007.1 1995.96  5113.8  1995.1  5135.8 1993.98
  5163.3 1994.93  5206.2 1994.48  5213.6 1995.33  5234.9 1997.82  5263.5  1999.6
  5374.7 2000.22  5498.1 2000.28  5839.8 1999.13  6644.2 2002.02  6811.6 2004.01
#Mann= 14 ,-1 , 0
  3075.4     .07       0  3402.8    .035       0  3838.2     .07       0
  4156.6    .045       0  4207.1     .07       0  4451.8    .045       0
  4626.2     .07       0    4996     .07       0  5004.1     .07       0
  5213.6     .05       0  5374.7     .07       0  5498.1     .05       0
  5839.8     .07       0  6644.2     .05       0
Bank Sta=4996,5004.1
XS Rating Curve= 0 ,0
Exp/Cntr=0.3,0.1

Type RM Length L Ch R = 1 ,152447  ,967,967,967
BEGIN DESCRIPTION:
Mapping XS 753e77e4
END DESCRIPTION:
XS GIS Cut Line= 4
      1452960.33      6860907.34      1453168.67      6860205.96
      1453404.78       6858712.9      1453363.11      6857747.58
#Sta/Elev= 30
  3389.6 2019.27  3464.9 2019.01    3552 2017.55    3601 2016.45    3739 2009.93
  3816.6 2007.07  4053.5 2001.79  4139.4  2001.3  4281.2 1999.04  4352.1 1999.97
  4392.6 1999.24  4703.7 1998.88  4787.4 1997.15  4858.3 1996.86  4979.8 1992.35
  4989.9 1991.58  4995.8 1987.73  4996.3 1987.23  5004.2 1987.73  5020.3 1989.11
  5025.7 1991.09  5050.6 1992.35    5162 1994.45  5253.1 1997.76  5284.4 1997.31
  5922.2 1997.39  6165.3 1998.21  6298.4 1998.33  6542.3  2000.4  6599.1 2000.72
#Mann= 9 ,-1 , 0
  3389.6     .07       0  3464.9    .035       0    3552     .07       0
  4995.8     .07       0  5004.2     .07       0  5284.4     .05       0
  5922.2     .07       0  6165.3     .05       0  6542.3     .07       0
Bank Sta=4995.8,5004.2
XS Rating Curve= 0 ,0
Exp/Cntr=0.3,0.1

Type RM Length L Ch R = 1 ,151480  ,603,603,603
BEGIN DESCRIPTION:
Mapping XS d748c733
END DESCRIPTION:
XS GIS Cut Line= 4
      1453640.88      6860893.49      1453953.39      6859893.46
      1454154.78      6858685.12      1454009.03      6857942.52
#Sta/Elev= 30
  3338.4 2016.42  3387.1 2015.75  3569.8 2010.67    3575 2011.17  3602.3 2008.57
  3607.5 2009.05  3710.8 2002.46  3784.2 2000.86    3847 1998.09  3962.3 1996.16
    4138 1995.73  4282.5 1994.72  4675.5  1994.6  4766.8 1993.64  4847.5 1991.98
  4852.5 1992.55  4908.3 1989.81  4974.2 1988.06  4995.8  1986.4  4996.3  1985.9
  5004.3  1986.4  5010.1  1986.4    5030 1989.31    5035 1988.65  5070.9 1990.45
  5106.4 1990.07  5233.1  1991.7  5873.2 1992.64  6299.2 1994.47  6367.9 1994.94
#Mann= 8 ,-1 , 0
  3338.4    .035       0  3387.1     .07       0    4138     .16       0
  4282.5     .07       0  4995.8     .07       0  5004.3     .07       0
  5106.4     .05       0  6299.2     .07       0
Bank Sta=4995.8,5004.3
XS Rating Curve= 0 ,0
Exp/Cntr=0.3,0.1

Type RM Length L Ch R = 1 ,150877  ,1586,1586,1586
BEGIN DESCRIPTION:
Noodle Creek 82.0
END DESCRIPTION:
XS GIS Cut Line= 3
      1453842.26      6860928.22      1454778.61      6858986.67
      1454657.08      6858478.85
#Sta/Elev= 30
  3234.4  2012.8  3319.6  2010.2  3467.8 2003.67  3528.7 2002.67  3551.3 2000.65
  3737.7 1995.85  3901.6 1993.01  4336.8 1990.58  4449.8 1990.25  4489.2 1991.11
  4517.7 1989.67  4533.6 1990.01  4562.9 1993.12  4568.4 1990.69  4613.7 1988.56
  4867.9 1986.64  4952.8 1987.17  4988.8 1985.79  4995.8 1982.95  4996.3 1982.45
  5004.3 1982.95    5011 1982.95  5020.7 1985.55  5043.3 1988.41  5094.1 1987.38
  5531.2 1988.56  5598.3 1988.83  5789.6 1989.26    5841 1988.37  5912.1  1989.9
#Mann= 5 ,-1 , 0
  3234.4     .07       0  4995.8     .07       0  5004.3     .07       0
  5531.2    .035       0  5598.3     .07       0
Bank Sta=4995.8,5004.3
XS Rating Curve= 0 ,0
Exp/Cntr=0.3,0.1

Type RM Length L Ch R = 1 ,149291  ,1267,1267,1267
BEGIN DESCRIPTION:
Noodle Creek 81.0
END DESCRIPTION:
XS GIS Cut Line= 4
      1454120.08      6861060.09        1455455.        6859488.
      1455549.78      6859396.74      1455494.56      6859202.92
#Sta/Elev= 30
  2942.3 2011.79  3330.2 1996.38    3941  1986.8  3982.6 1987.91  4068.3 1984.74
  4089.2 1981.19  4138.9 1977.59  4189.2  1978.5  4224.3 1983.93  4230.9 1986.92
  4259.4 1988.92  4281.4 1988.52    4288  1984.6  4302.3 1982.71  4338.6 1982.01
  4428.5 1981.28  4453.5 1981.06  4507.7 1981.05  4564.8 1978.05  4617.6 1980.27
  4714.2 1981.27    4813 1978.35  4962.4 1979.65    4969 1977.15  4995.6 1975.59
  4996.1 1975.09  5004.4 1975.59  5075.3 1981.96  5129.5 1982.14  5337.8 1982.37
#Mann= 8 ,-1 , 0
  2942.3     .07       0  4338.6    .035       0  4428.5     .07       0
  4453.5    .035       0  4617.6     .07       0  4995.6     .07       0
  5004.4     .07       0  5129.5    .035       0
Bank Sta=4995.6,5004.4
XS Rating Curve= 0 ,0
Exp/Cntr=0.3,0.1

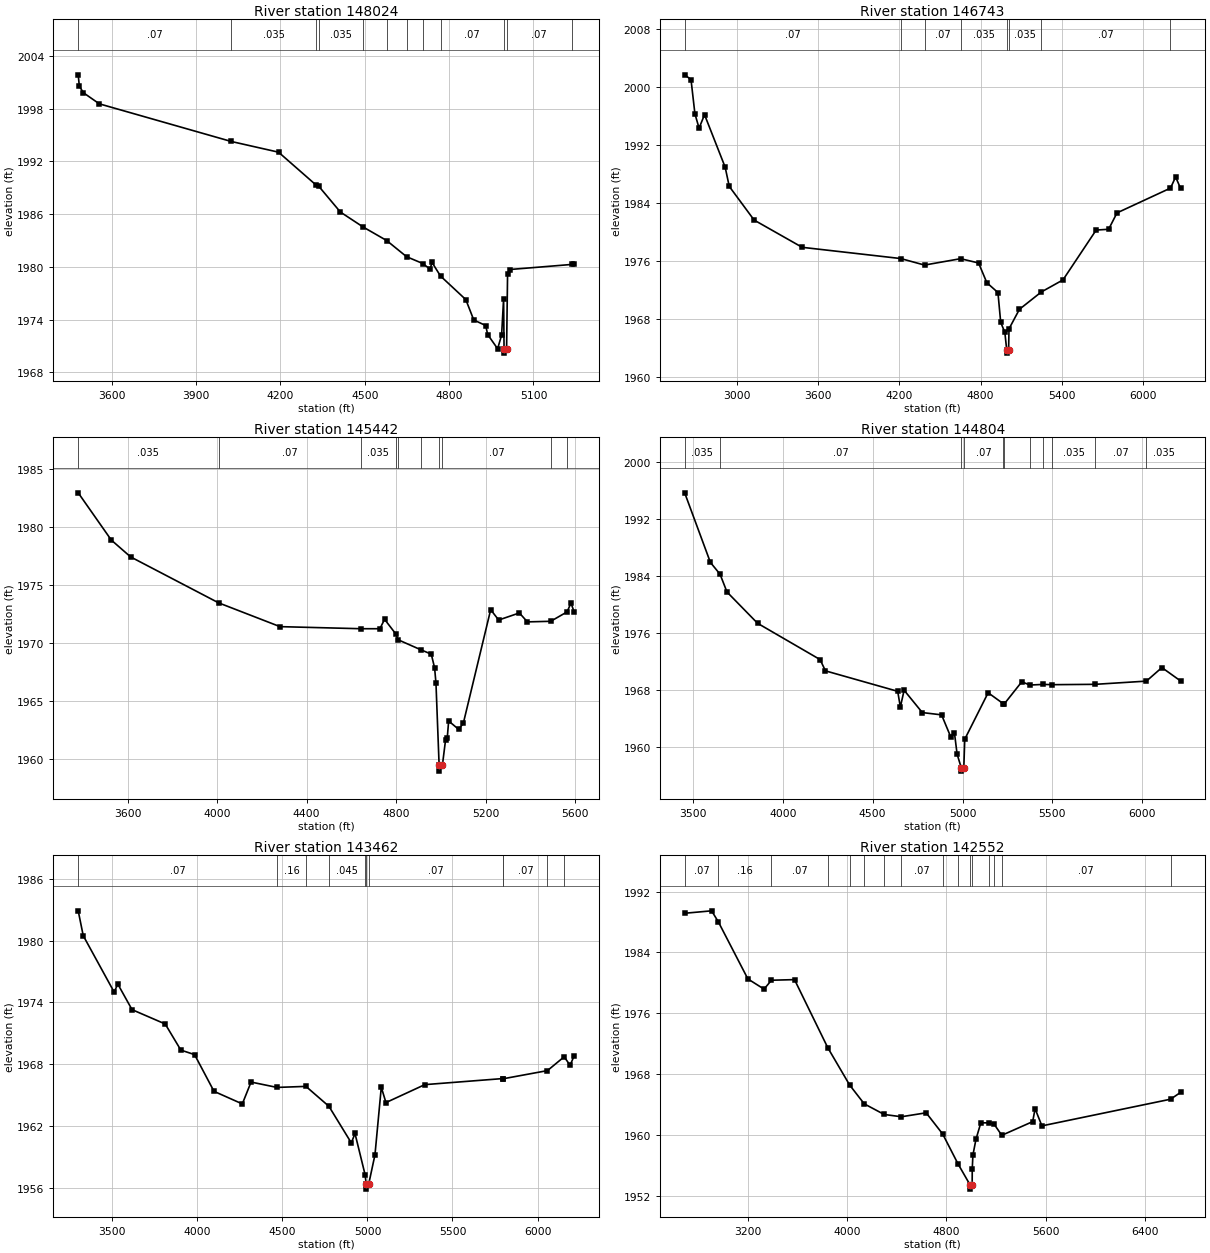
Type RM Length L Ch R = 1 ,148024  ,1281,1281,1281
BEGIN DESCRIPTION:
Noodle Creek 80.0
END DESCRIPTION:
XS GIS Cut Line= 4
      1454489.72      6861318.56      1455289.72      6860418.56
       1455592.1      6860112.04      1455603.04      6859984.03
#Sta/Elev= 30
  3481.5 2001.85  3485.4 2000.58  3499.6 1999.82  3556.5 1998.55  4025.4 1994.27
  4193.7 1993.05  4325.8 1989.35  4336.3 1989.19  4413.6 1986.24  4494.9 1984.53
  4578.1    1983  4648.9 1981.16  4706.9 1980.38  4732.2 1979.74  4739.3 1980.51
  4769.6 1978.96  4859.5 1976.28  4887.8 1973.96  4930.2 1973.33  4937.3  1972.3
  4972.6 1970.69  4986.8 1972.24  4993.9  1976.4  4995.5 1970.69    4996 1970.19
  5004.5 1970.69    5008 1979.22  5015.1  1979.7  5236.6 1980.28  5244.7  1980.3
#Mann= 12 ,-1 , 0
  3481.5     .07       0  4025.4    .035       0  4325.8     .07       0
  4336.3    .035       0  4494.9     .07       0  4578.1    .035       0
  4648.9     .07       0  4706.9    .035       0  4769.6     .07       0
  4995.5     .07       0  5004.5     .07       0  5236.6    .035       0
Bank Sta=4995.5,5004.5
XS Rating Curve= 0 ,0
Exp/Cntr=0.3,0.1

Type RM Length L Ch R = 1 ,146743  ,1301,1301,1301
BEGIN DESCRIPTION:
Mapping XS acd212ea
END DESCRIPTION:
XS GIS Cut Line= 4
      1455932.55      6862782.39      1456231.17      6861074.01
      1456508.94      6859726.79      1456640.89      6859192.07
#Sta/Elev= 30
  2616.2 2001.69  2662.9 2001.04  2691.7 1996.32  2722.4 1994.33  2762.8 1996.19
  2915.1 1988.94  2945.1  1986.3  3128.7 1981.65  3483.5 1977.89  4210.8 1976.34
  4386.4 1975.44  4652.5 1976.32  4785.4 1975.73  4846.7    1973  4928.4 1971.65
  4948.8 1967.54  4979.4 1966.15  4992.9 1963.79  4993.4 1963.29  5007.2 1963.79
  5010.1 1966.64  5087.1 1969.34  5248.8 1971.73  5408.3 1973.39  5653.3 1980.27
  5745.4 1980.38  5807.2 1982.64    6202 1986.06  6239.8 1987.59  6276.8 1986.02
#Mann= 8 ,-1 , 0
  2616.2     .07       0  4210.8    .035       0  4386.4     .07       0
  4652.5    .035       0  4992.9    .035       0  5007.2    .035       0
  5248.8     .07       0    6202    .035       0
Bank Sta=4992.9,5007.2
XS Rating Curve= 0 ,0
Exp/Cntr=0.3,0.1

Type RM Length L Ch R = 1 ,145442  ,638,638,638
BEGIN DESCRIPTION:
Mapping XS c8fcb332
END DESCRIPTION:
XS GIS Cut Line= 4
      1456224.22      6862497.62      1456543.67      6861580.96
      1457474.22      6860935.12      1457495.06        6860824.
#Sta/Elev= 30
  3379.7 1982.96  3527.6 1978.89  3613.8 1977.44  4007.2 1973.48  4281.6 1971.43
    4644 1971.25    4728 1971.25  4748.9 1972.06  4798.3 1970.82  4809.3  1970.3
  4910.6 1969.44  4957.6 1969.06  4972.5 1967.88  4978.6 1966.56  4992.7 1959.48
  4993.2 1958.98  5007.3 1959.48  5021.5 1961.67  5029.2 1961.87  5035.3  1963.3
  5079.9 1962.58  5100.8  1963.1  5223.1 1972.89  5258.9    1972  5351.4 1972.61
  5387.2 1971.84  5491.4 1971.89  5564.5  1972.7    5582 1973.46  5596.2  1972.7
#Mann= 10 ,-1 , 0
  3379.7    .035       0  4007.2     .07       0    4644    .035       0
  4798.3     .07       0  4809.3    .035       0  4910.6     .07       0
  4992.7     .07       0  5007.3     .07       0  5491.4    .035       0
  5564.5     .07       0
Bank Sta=4992.7,5007.3
XS Rating Curve= 0 ,0
Exp/Cntr=0.3,0.1

Type RM Length L Ch R = 1 ,144804  ,1342,1342,1342
BEGIN DESCRIPTION:
Mapping XS 48335c3d
END DESCRIPTION:
XS GIS Cut Line= 4
      1456161.72      6862726.79      1456620.05      6862185.12
       1457939.5      6861261.51      1457911.72      6860824.03
#Sta/Elev= 30
  3454.7  1995.7  3597.6 1985.95  3651.6 1984.28  3689.9  1981.8  3860.1 1977.41
  4207.9 1972.32  4237.6 1970.74  4639.5 1967.87  4654.3 1965.67  4675.3 1968.02
  4776.4 1964.89  4883.6 1964.57  4934.2  1961.5  4955.1 1962.06    4970 1959.06
  4992.7 1957.18  4993.2 1956.68  5007.3 1957.18  5012.5 1961.15  5142.6 1967.67
  5226.5 1966.14  5232.8 1966.12  5329.9 1969.21  5374.5 1968.75  5450.1 1968.84
  5497.8  1968.8  5738.3 1968.85  6022.9  1969.3    6109  1971.2  6213.2 1969.32
#Mann= 11 ,-1 , 0
  3454.7    .035       0  3651.6     .07       0  4992.7     .07       0
  5007.3     .07       0  5226.5    .035       0  5232.8     .07       0
  5374.5    .035       0  5450.1     .07       0  5497.8    .035       0
  5738.3     .07       0  6022.9    .035       0
Bank Sta=4992.7,5007.3
XS Rating Curve= 0 ,0
Exp/Cntr=0.3,0.1

Type RM Length L Ch R = 1 ,143462  ,910,910,910
BEGIN DESCRIPTION:
Mapping XS c8cc32b1
END DESCRIPTION:
XS GIS Cut Line= 5
      1456543.24      6862925.32      1457499.84      6862486.47
      1457666.49      6862452.53      1458238.11      6861469.84
      1458210.33      6860914.32
#Sta/Elev= 30
  3299.6 1982.88  3329.1 1980.47  3510.6 1975.01  3532.6 1975.77    3616  1973.3
    3811 1971.91  3902.9 1969.38  3983.7 1968.94  4097.9 1965.38  4264.3 1964.16
  4315.8 1966.28  4468.3 1965.76  4638.4 1965.86  4773.5 1963.93  4905.2 1960.38
  4926.7  1961.3    4986 1957.31  4992.6  1956.4  4993.1  1955.9  5007.5  1956.4
  5044.2 1959.23  5081.4 1965.78  5108.7 1964.29  5337.2 1966.03  5797.2 1966.62
    5798  1966.6  6058.2 1967.39  6156.5 1968.73  6191.5  1967.9  6215.2 1968.83
#Mann= 11 ,-1 , 0
  3299.6     .07       0  4468.3     .16       0  4638.4     .07       0
  4773.5    .045       0    4986     .07       0  4992.6     .07       0
  5007.5     .07       0  5797.2    .035       0    5798     .07       0
  6058.2    .035       0  6156.5     .07       0
Bank Sta=4992.6,5007.5
XS Rating Curve= 0 ,0
Exp/Cntr=0.3,0.1

Type RM Length L Ch R = 1 ,142552  ,793,793,793
BEGIN DESCRIPTION:
Mapping XS 74fdbd27
END DESCRIPTION:
XS GIS Cut Line= 4
      1457779.78      6864928.15      1458099.22      6863615.68
      1458654.78      6862143.46      1458647.83      6861074.02
#Sta/Elev= 30
  2692.4 1989.14  2909.3 1989.46  2963.8    1988  3201.4  1980.5  3331.7 1979.16
    3391 1980.33  3576.9 1980.41  3845.2 1971.44    4021 1966.54  4138.3 1964.07
  4299.2 1962.67  4437.5 1962.37  4637.1 1962.89  4770.5 1960.09  4893.3 1956.18
  4992.6 1953.35  4993.1 1952.85  5007.5 1953.35  5008.2  1955.5  5013.5 1957.33
  5038.4 1959.42  5077.5 1961.58  5142.2 1961.56  5184.8 1961.38  5246.1 1959.93
  5494.8 1961.73  5514.3 1963.43  5569.1 1961.17  6605.5 1964.68  6686.2 1965.58
#Mann= 16 ,-1 , 0
  2692.4     .07       0  2963.8     .16       0    3391     .07       0
  3845.2     .16       0    4021    .035       0  4138.3     .07       0
  4299.2    .035       0  4437.5     .07       0  4770.5    .045       0
  4893.3     .07       0  4992.6    .045       0  5007.5     .07       0
  5142.2     .07       0  5184.8    .035       0  5246.1     .07       0
  6605.5    .035       0
Bank Sta=4992.6,5007.5
XS Rating Curve= 0 ,0
Exp/Cntr=0.3,0.1

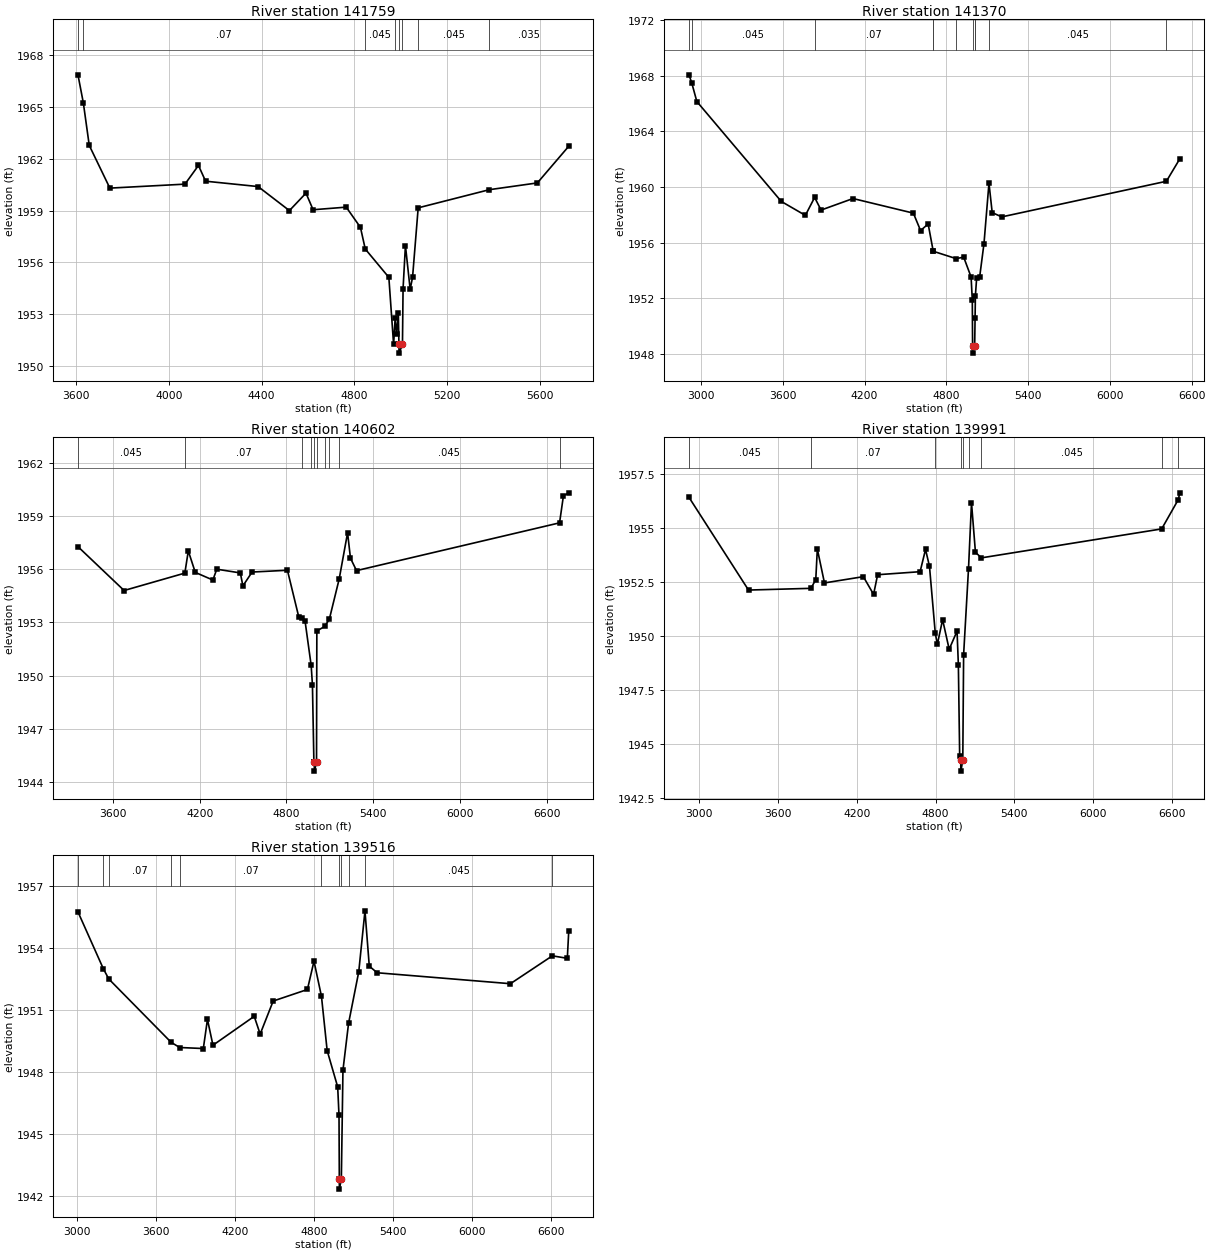
Type RM Length L Ch R = 1 ,141759  ,389,389,389
BEGIN DESCRIPTION:
Mapping XS 54da1a62
END DESCRIPTION:
XS GIS Cut Line= 5
       1458527.6       6863792.8      1458732.56      6863309.73
      1458870.38       6863232.4      1459074.47      6862245.94
      1459011.98      6861824.08
#Sta/Elev= 30
  3608.1 1966.85  3631.3 1965.23  3656.8 1962.77  3745.7  1960.3  4069.6 1960.53
  4127.8 1961.61  4158.6  1960.7    4385 1960.39    4520    1959  4591.5 1960.01
  4622.2 1959.05  4765.1  1959.2  4826.4 1958.03  4847.1 1956.78  4948.9 1955.14
  4969.4 1951.26    4976 1952.77  4982.3 1951.89  4989.8 1953.07  4992.4 1951.26
  4992.9 1950.76  5007.6 1951.26  5010.2 1954.49  5020.4 1956.98  5040.8 1954.45
  5051.1 1955.14  5075.4 1959.16  5382.5 1960.21  5589.3  1960.6  5724.7 1962.72
#Mann= 8 ,-1 , 0
  3608.1     .16       0  3631.3     .07       0  4847.1    .045       0
    4976     .07       0  4992.4     .07       0  5007.6     .07       0
  5075.4    .045       0  5382.5    .035       0
Bank Sta=4992.4,5007.6
XS Rating Curve= 0 ,0
Exp/Cntr=0.3,0.1

Type RM Length L Ch R = 1 ,141370  ,768,768,768
BEGIN DESCRIPTION:
Mapping XS 2b6b6b00
END DESCRIPTION:
XS GIS Cut Line= 4
      1458617.71      6864635.15      1459022.83      6863643.46
      1459379.58      6862582.13      1459255.38      6861176.64
#Sta/Elev= 30
  2911.1 1968.05  2930.7 1967.49  2968.7 1966.13  3588.6 1958.95  3765.1 1957.95
  3833.2 1959.24  3880.2 1958.33  4114.7 1959.16  4557.8 1958.11  4610.5 1956.86
  4666.3 1957.33  4703.6 1955.37  4703.8 1955.37    4872 1954.84    4927 1954.95
  4981.4 1953.52  4990.3 1951.86  4992.4 1948.55  4992.9 1948.05  5007.6 1948.55
  5010.6 1950.54    5013 1952.19    5022 1953.42  5044.5 1953.54    5076 1955.92
  5112.6 1960.26  5136.3 1958.15  5206.2 1957.84  6414.7  1960.4    6513 1962.01
#Mann= 11 ,-1 , 0
  2911.1     .07       0  2930.7    .045       0  3833.2     .07       0
  4703.6    .045       0  4703.8     .07       0    4872    .045       0
  4992.4    .045       0  5007.6    .045       0  5010.6     .07       0
  5112.6    .045       0  6414.7    .035       0
Bank Sta=4992.4,5007.6
XS Rating Curve= 0 ,0
Exp/Cntr=0.3,0.1

Type RM Length L Ch R = 1 ,140602  ,611,611,611
BEGIN DESCRIPTION:
Mapping XS b3b3fb03
END DESCRIPTION:
XS GIS Cut Line= 4
      1459267.97      6864605.48      1459603.12      6863727.71
      1459756.77      6862896.98      1459677.77      6861291.21
#Sta/Elev= 30
  3358.8 1957.27  3677.7  1954.8  4097.6 1955.78  4121.4 1957.03  4169.6 1955.82
  4291.2 1955.39  4318.4    1956  4481.1 1955.79  4498.8 1955.06  4562.5 1955.84
  4806.6 1955.94  4884.4 1953.33  4909.6 1953.26  4928.6 1953.07  4970.7 1950.58
  4979.4 1949.49  4989.6 1945.13  4992.4 1945.13  4992.9 1944.63  5007.7 1945.13
  5009.9 1952.52  5064.5 1952.78  5096.4 1953.19  5164.4 1955.45  5222.3 1958.05
  5242.3 1956.62  5284.1 1955.92  6687.5 1958.61  6714.1 1960.13  6750.9  1960.3
#Mann= 10 ,-1 , 0
  3358.8    .045       0  4097.6     .07       0  4909.6    .045       0
  4970.7     .07       0  4992.4     .07       0  5007.7     .07       0
  5064.5    .045       0  5096.4     .07       0  5164.4    .045       0
  6687.5    .035       0
Bank Sta=4992.4,5007.7
XS Rating Curve= 0 ,0
Exp/Cntr=0.3,0.1

Type RM Length L Ch R = 1 ,139991  ,475,475,475
BEGIN DESCRIPTION:
Mapping XS eb63021a
END DESCRIPTION:
XS GIS Cut Line= 5
      1459655.99      6864897.16      1460303.49       6863239.5
      1460304.82      6862875.85      1460321.35      6862045.12
      1460110.73      6861311.85
#Sta/Elev= 30
  2922.9  1956.4    3376 1952.11  3851.1 1952.19  3888.2 1952.59  3900.1 1954.01
  3954.4 1952.44  4250.5 1952.73  4328.4 1951.91  4359.2 1952.82  4682.7 1952.96
    4724 1953.99    4754 1953.21  4798.3 1950.11    4814  1949.6    4854 1950.74
    4904 1949.37    4964 1950.21    4974 1948.66    4984 1944.43  4992.3 1944.23
  4992.8 1943.73  5007.7 1944.23    5014 1949.12  5051.2 1953.09    5074 1956.15
    5104 1953.86  5149.1  1953.6  6522.1 1954.94    6649  1956.3    6660 1956.61
#Mann= 9 ,-1 , 0
  2922.9    .045       0  3851.1     .07       0  4798.3     .16       0
  4992.3     .07       0  5007.7     .16       0  5051.2     .07       0
  5149.1    .045       0  6522.1    .035       0    6649    .045       0
Bank Sta=4992.3,5007.7
XS Rating Curve= 0 ,0
Exp/Cntr=0.3,0.1

Type RM Length L Ch R = 1 ,139516  ,479,479,479
BEGIN DESCRIPTION:
Mapping XS 9cdc41a8
END DESCRIPTION:
XS GIS Cut Line= 5
       1460215.9      6865019.51      1460634.89      6863647.75
      1460667.05      6862919.97      1460641.67      6862052.93
      1460425.51      6861386.22
#Sta/Elev= 30
  3005.3 1955.76  3197.8 1953.01  3239.5 1952.51  3713.9 1949.44  3778.8 1949.19
  3958.4 1949.14  3989.8 1950.55  4031.6  1949.3  4345.3  1950.7  4390.5 1949.84
  4489.4 1951.44  4749.7    1952  4799.7 1953.37  4856.5 1951.67  4899.8 1949.04
  4979.9 1947.28  4989.9  1945.9  4992.3 1942.83  4992.8 1942.33  5007.7 1942.83
  5019.9 1948.09  5062.5 1950.36  5140.1 1952.86  5187.3 1955.81  5220.1 1953.13
  5280.1 1952.81    6293 1952.28  6611.7 1953.63  6725.6 1953.51  6736.4 1954.82
#Mann= 11 ,-1 , 0
  3005.3     .07       0  3197.8    .045       0  3239.5     .07       0
  3713.9    .045       0  3778.8     .07       0  4856.5     .16       0
  4992.3     .07       0  5007.7     .16       0  5062.5     .07       0
  5187.3    .045       0  6611.7    .035       0
Bank Sta=4992.3,5007.7
XS Rating Curve= 0 ,0
Exp/Cntr=0.3,0.1