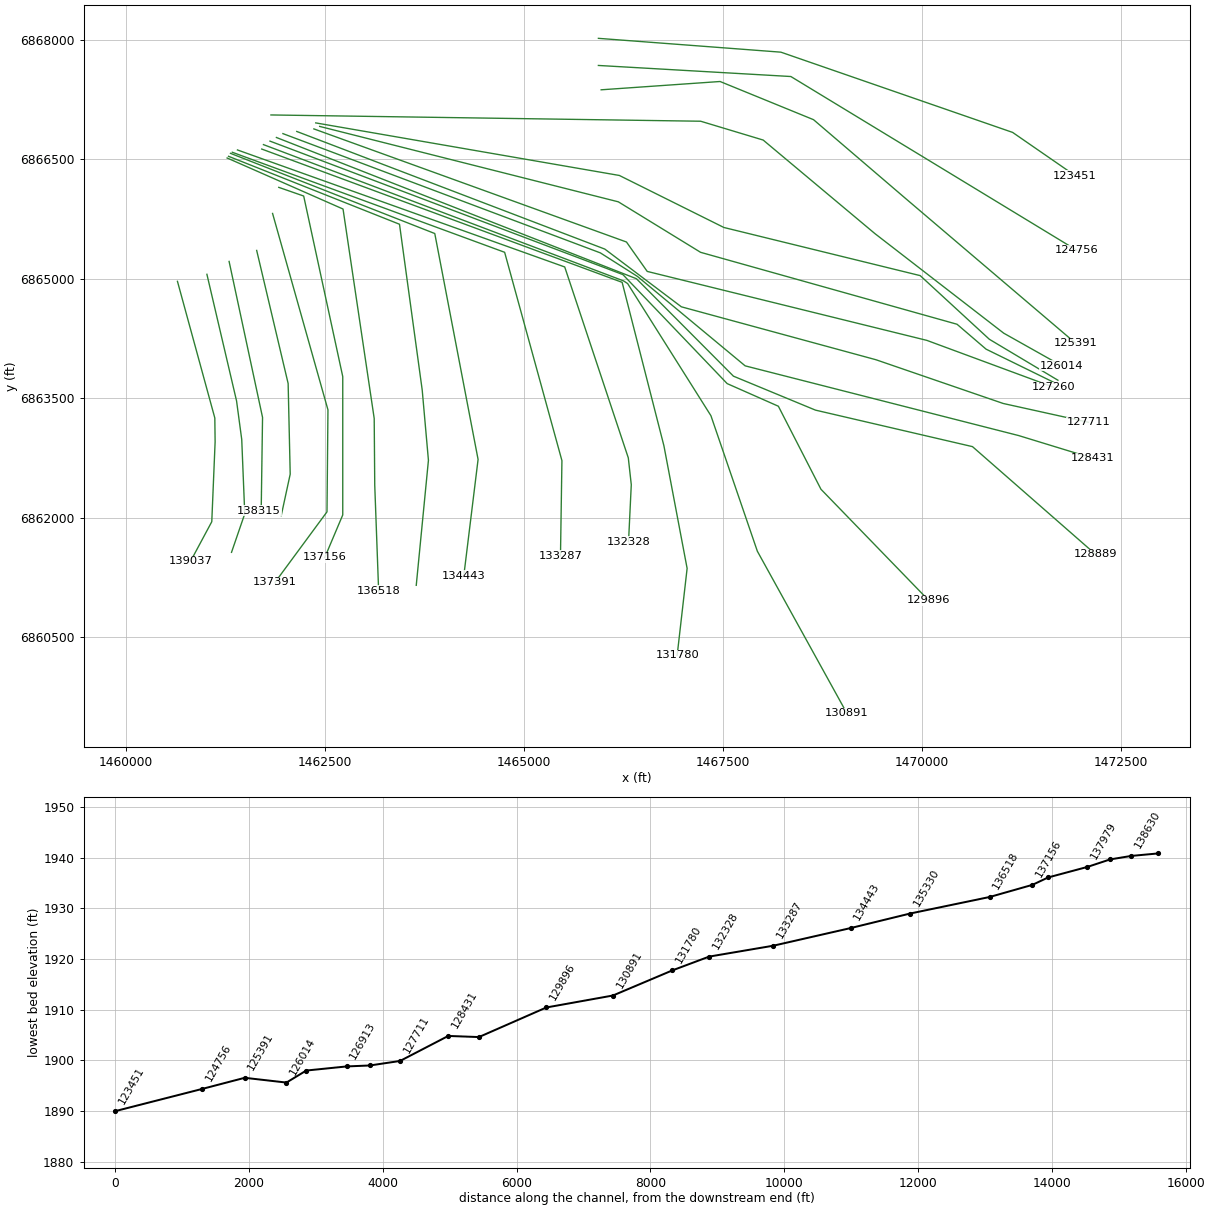
HEC-RAS study Noodle Creek.prj: Noodle Creek Base Level Engineering

--- Noodle Creek.g01 (geometry) --- (continued)

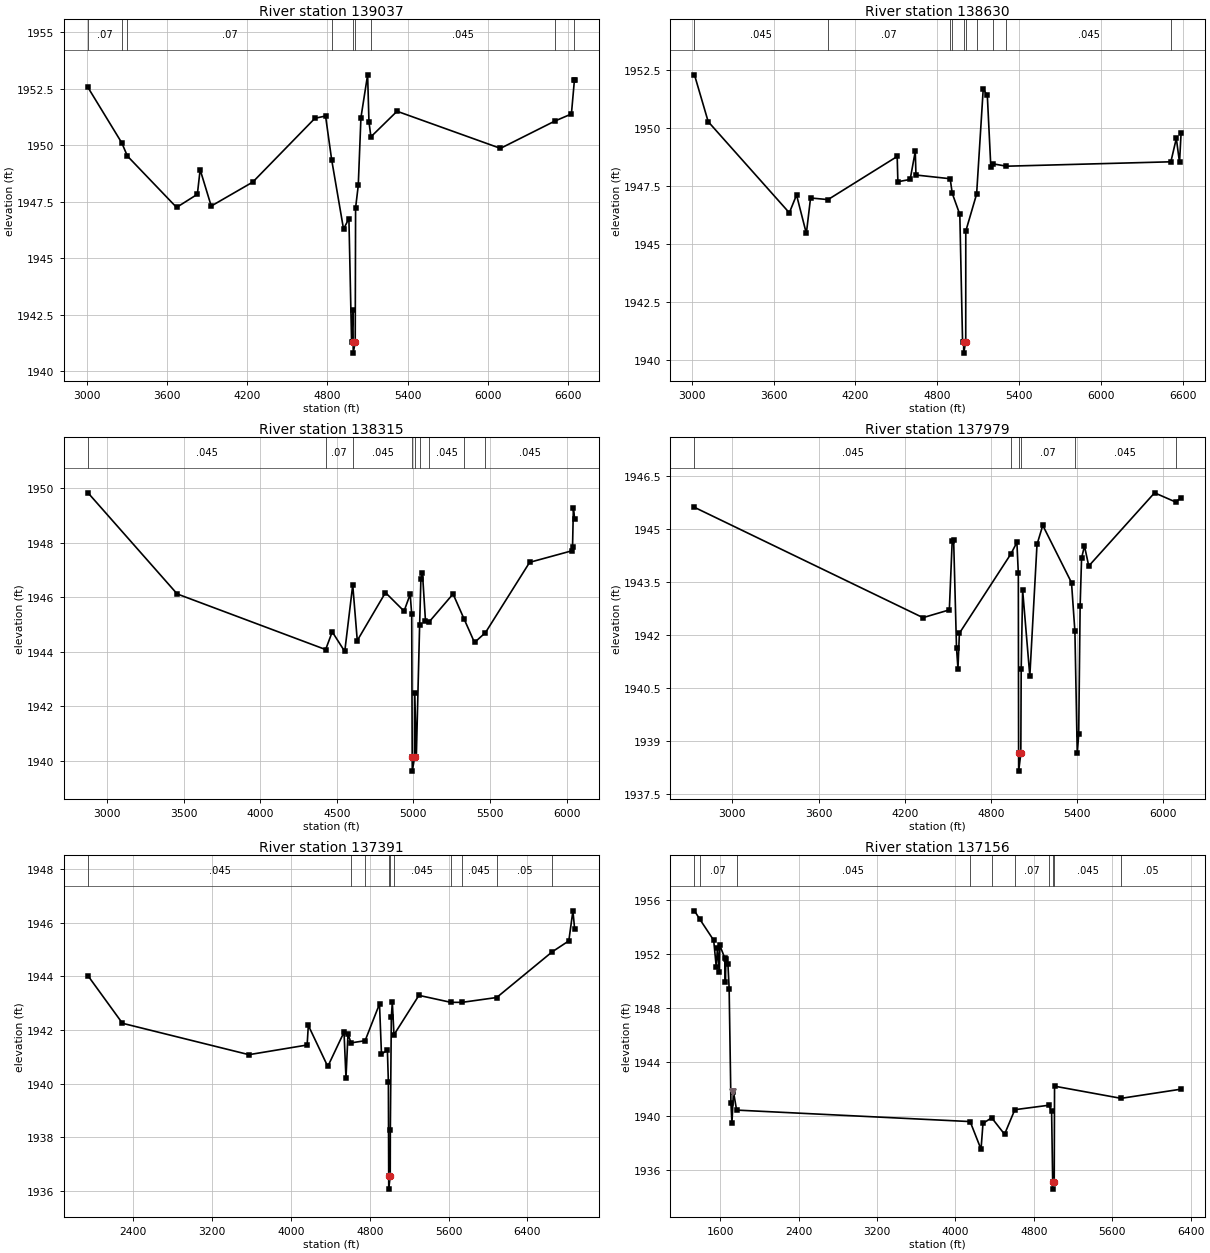
Type RM Length L Ch R = 1 ,139037  ,407,407,407
BEGIN DESCRIPTION:
Mapping XS 34820cd5
END DESCRIPTION:
XS GIS Cut Line= 5
       1460650.8      6864967.42      1461119.95      6863252.54
      1461123.69      6862953.94      1461081.77      6861951.37
      1460816.12      6861456.54
#Sta/Elev= 30
    3008 1952.55  3261.1  1950.1  3302.8 1949.52  3670.9 1947.25  3826.4 1947.83
  3847.2 1948.92  3930.1 1947.31  4241.1 1948.37  4706.4 1951.19  4785.7 1951.29
  4831.4 1949.36  4920.4 1946.29  4960.5 1946.76  4980.5 1941.31  4990.5 1942.72
  4992.3 1941.31  4992.8 1940.81  5007.7 1941.31  5010.5 1947.23  5030.5 1948.22
  5050.5 1951.22  5100.5 1953.11  5110.5 1951.04  5125.2 1950.37  5320.7  1951.5
  6094.6 1949.86  6502.9 1951.07  6625.6 1951.38  6648.1 1952.88  6649.6 1952.88
#Mann= 9 ,-1 , 0
    3008     .07       0  3261.1    .045       0  3302.8     .07       0
  4831.4     .16       0  4992.3     .07       0  5007.7     .16       0
  5125.2    .045       0  6502.9    .035       0  6648.1    .045       0
Bank Sta=4992.3,5007.7
XS Rating Curve= 0 ,0
Exp/Cntr=0.3,0.1

Type RM Length L Ch R = 1 ,138630  ,315,315,315
BEGIN DESCRIPTION:
Mapping XS d1eeb050
END DESCRIPTION:
XS GIS Cut Line= 5
      1461020.59      6865055.95      1461392.99      6863466.47
      1461457.91        6862983.      1461495.83      6862050.33
      1461329.59       6861567.2
#Sta/Elev= 30
  3020.5 1952.31  3121.1 1950.29  3715.5 1946.36  3768.2 1947.13  3840.1 1945.47
  3870.9    1947  3998.8 1946.93  4505.5 1948.79  4510.6  1947.7  4600.6  1947.8
    4638 1949.01  4643.1 1947.99  4893.7 1947.83  4908.8  1947.2  4964.3 1946.29
  4984.4 1940.81  4992.3 1940.81  4992.8 1940.31  5007.7 1940.81    5008 1945.57
  5087.4 1947.17  5135.8  1951.7  5165.8 1951.42  5191.6 1948.32  5209.2 1948.47
  5306.2 1948.37  6510.4 1948.56  6550.3 1949.57  6573.8 1948.53  6585.2  1949.8
#Mann= 10 ,-1 , 0
  3020.5    .045       0  3998.8     .07       0  4893.7    .045       0
  4908.8     .07       0  4992.3     .07       0  5007.7     .07       0
  5087.4    .045       0  5209.2     .07       0  5306.2    .045       0
  6510.4    .035       0
Bank Sta=4992.3,5007.7
XS Rating Curve= 0 ,0
Exp/Cntr=0.3,0.1

Type RM Length L Ch R = 1 ,138315  ,336,336,336
BEGIN DESCRIPTION:
Mapping XS cd676420
END DESCRIPTION:
XS GIS Cut Line= 4
      1461299.24      6865217.39      1461719.22      6863260.42
      1461703.39      6862164.29      1461675.76      6862089.19
#Sta/Elev= 30
  2875.1 1949.83  3457.5 1946.12    4427 1944.08    4470 1944.73  4551.8 1944.01
  4603.9 1946.45  4633.6 1944.41  4817.7 1946.17  4939.1 1945.49  4979.1 1946.11
  4989.1 1945.37  4992.3 1940.12  4992.8 1939.62  5007.7 1940.12  5009.1 1942.47
  5019.1 1940.12  5040.8 1944.99  5049.1 1946.67  5059.1  1946.9  5079.1 1945.12
  5102.1 1945.09  5259.1 1946.12  5330.4 1945.21  5399.1 1944.34  5470.6  1944.7
  5759.1 1947.28  6032.9  1947.7  6039.4 1947.85  6044.7 1949.26  6052.9 1948.88
#Mann= 9 ,-1 , 0
  2875.1    .045       0    4427     .07       0  4603.9    .045       0
  4992.3     .07       0  5007.7    .045       0  5040.8     .07       0
  5102.1    .045       0  5330.4     .07       0  5470.6    .045       0
Bank Sta=4992.3,5007.7
XS Rating Curve= 0 ,0
Exp/Cntr=0.3,0.1

Type RM Length L Ch R = 1 ,137979  ,588,588,588
BEGIN DESCRIPTION:
Mapping XS 0e59c922
END DESCRIPTION:
XS GIS Cut Line= 4
      1461645.58      6865355.49      1462040.56      6863685.66
       1462066.6      6862548.51      1461953.75      6862027.65
#Sta/Elev= 30
  2736.7 1945.61  4326.9 1942.49  4510.3 1942.71  4530.3 1944.67  4540.3 1944.68
  4560.3 1941.63  4570.3 1941.05  4580.3 1942.05  4939.9  1944.3  4980.4 1944.62
  4990.4 1943.74  4992.3 1938.65  4992.8 1938.15  5007.7 1938.65  5010.4 1941.04
  5020.4 1943.27  5070.4 1940.84  5120.4 1944.56  5160.5  1945.1  5360.5 1943.48
  5384.1  1942.1  5400.5 1938.65  5410.5 1939.19  5420.5 1942.82  5430.5 1944.17
  5450.5 1944.52  5480.5 1943.95  5938.5 1946.02  6085.4 1945.76    6123 1945.88
#Mann= 6 ,-1 , 0
  2736.7    .045       0  4939.9     .07       0  4992.3     .07       0
  5007.7     .07       0  5384.1    .045       0  6085.4     .05       0
Bank Sta=4992.3,5007.7
XS Rating Curve= 0 ,0
Exp/Cntr=0.3,0.1

Type RM Length L Ch R = 1 ,137391  ,235,235,235
BEGIN DESCRIPTION:
Mapping XS c780a29b
END DESCRIPTION:
XS GIS Cut Line= 4
       1461845.2      6865819.47      1462540.58      6863354.95
      1462528.47      6862075.31      1461877.33      6861192.51
#Sta/Elev= 30
  1941.3 1944.02  2290.7 1942.25  3574.1 1941.08  4164.8 1941.44  4176.8 1942.17
  4374.2 1940.64    4539 1941.92  4558.9  1940.2    4579 1941.84    4611 1941.52
  4752.9  1941.6    4899 1942.97    4919  1941.1    4979 1941.25    4989 1940.06
  4992.3 1936.57  4992.8 1936.07  5007.8 1936.57    5009 1938.28    5019 1942.48
    5029 1943.04  5045.7 1941.82    5299 1943.29  5622.7 1943.03  5737.2 1943.03
    6088 1943.21  6650.5 1944.91  6819.8 1945.32  6861.5 1946.44  6878.7 1945.77
#Mann= 10 ,-1 , 0
  1941.3    .045       0    4611     .16       0  4752.9     .07       0
  4992.3     .07       0  5007.8     .07       0  5045.7    .045       0
  5622.7     .05       0  5737.2    .045       0    6088     .05       0
  6650.5    .035       0
Bank Sta=4992.3,5007.8
XS Rating Curve= 0 ,0
Exp/Cntr=0.3,0.1

Type RM Length L Ch R = 1 ,137156  ,638,638,638
BEGIN DESCRIPTION:
Mapping XS 861ccd03
END DESCRIPTION:
XS GIS Cut Line= 5
      1461923.15      6866146.82      1462235.81      6866038.25
      1462726.33      6863772.46      1462726.33      6862036.35
      1462500.73      6861502.74
#Sta/Elev= 30
  1337.5 1955.21  1392.7 1954.58  1533.7 1953.03  1559.5 1951.08  1572.3 1952.48
  1590.6 1950.67  1595.9 1952.66  1646.4 1951.72  1652.9 1949.91  1658.2 1951.65
    1679 1951.26  1691.3 1949.46  1709.7 1940.97  1719.9  1939.5  1735.4 1941.81
  1767.5 1940.46  4150.2 1939.61  4261.2 1937.56  4281.2 1939.48    4370 1939.89
  4501.2 1938.67    4606 1940.49  4953.2 1940.82  4981.2 1940.36  4992.3 1935.11
  4992.8 1934.61  5007.8 1935.11  5011.2 1942.23    5690 1941.33  6302.2 1942.01
#Mann= 10 ,-1 , 0
  1337.5    .035       0  1392.7     .07       0  1767.5    .045       0
  4150.2     .07       0    4370    .045       0    4606     .07       0
  4953.2    .045       0  4992.3    .045       0  5007.8    .045       0
    5690     .05       0
Levee=-1,1735.4,1941.81,0,,,,
Bank Sta=4992.3,5007.8
XS Rating Curve= 0 ,0
Exp/Cntr=0.3,0.1

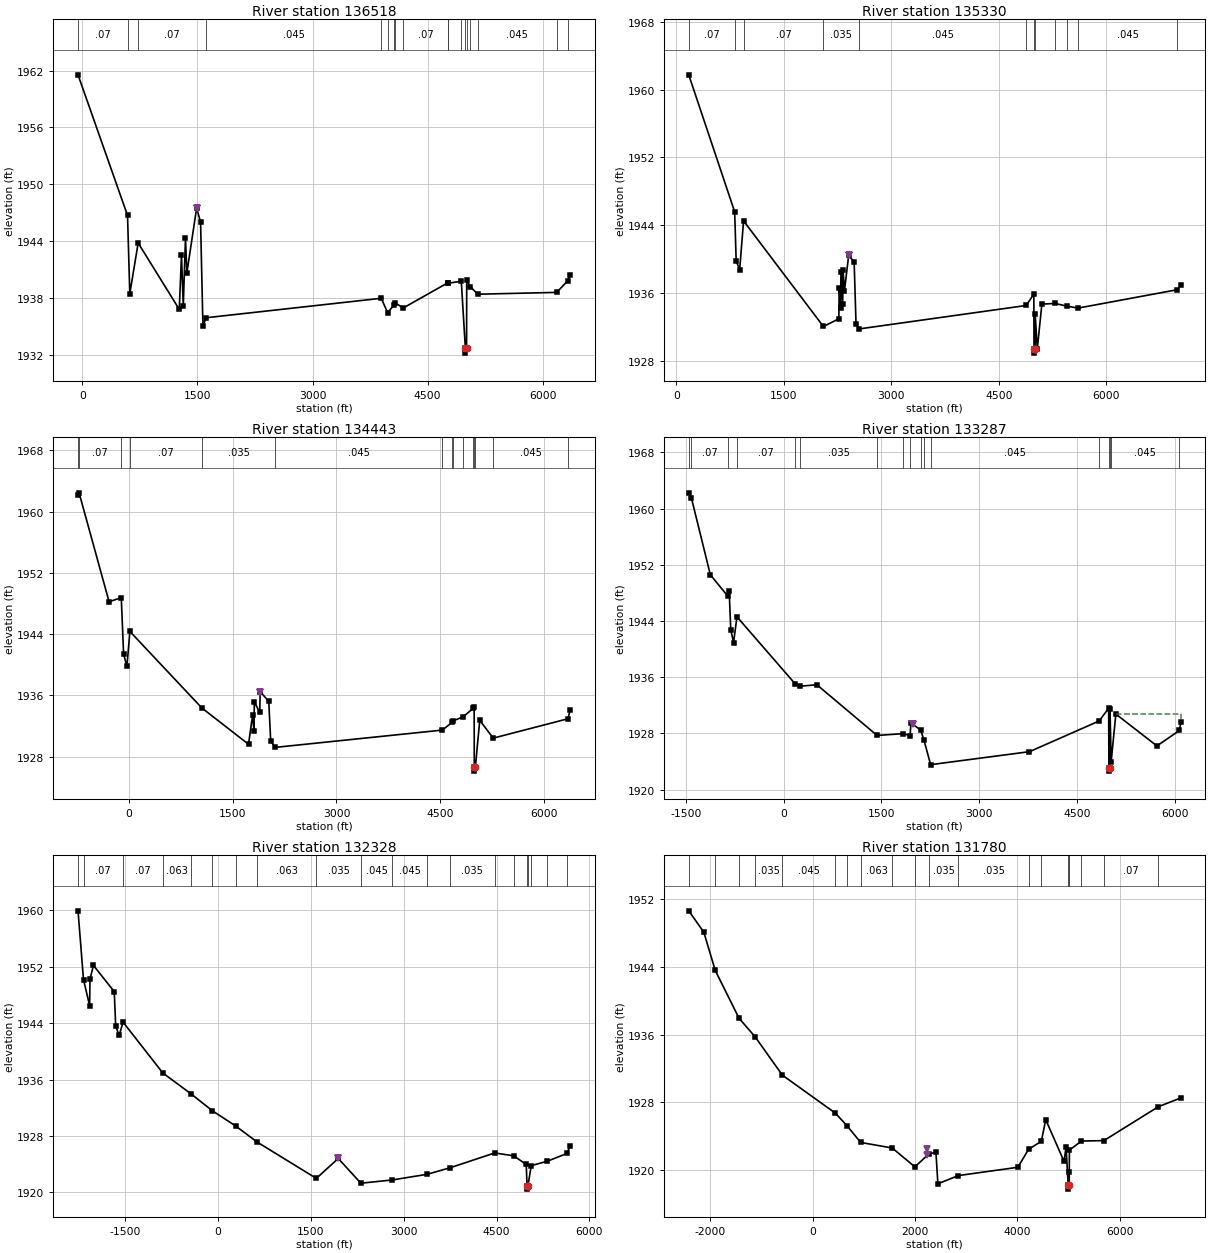
Type RM Length L Ch R = 1 ,136518  ,1188,1188,1188
BEGIN DESCRIPTION:
Mapping XS 1550876d
END DESCRIPTION:
XS GIS Cut Line= 5
      1461274.26      6866515.68      1462730.01      6865875.05
      1463121.29      6863247.29      1463128.13       6862410.2
        1463177.      6861081.42
#Sta/Elev= 30
   -56.9 1961.55   588.4 1946.73     618 1938.47   726.9 1943.83    1263 1936.83
  1291.8 1942.53  1315.1 1937.17  1343.9 1944.39  1361.8 1940.67  1489.4 1947.52
  1540.7 1946.01    1571 1935.13  1614.4 1935.95    3896    1938  3978.3 1936.49
    4059 1937.25  4076.9 1937.51  4182.8 1936.98    4763 1939.63  4770.7 1939.59
  4938.9  1939.8  4992.3 1932.72  4992.8 1932.22  5007.8 1932.72  5009.6 1939.93
  5056.6 1939.22  5154.5 1938.43  6181.8 1938.62  6329.1 1939.86  6357.1  1940.5
#Mann= 18 ,-1 , 0
   -56.9     .07       0   588.4    .035       0   726.9     .07       0
  1614.4    .045       0    3896     .07       0  3978.3    .045       0
    4059     .07       0  4076.9     .16       0  4182.8     .07       0
    4763     .12       0  4770.7     .07       0  4938.9     .12       0
  4992.3     .07       0  5007.8     .12       0  5056.6     .07       0
  5154.5    .045       0  6181.8     .05       0  6329.1    .035       0
Levee=-1,1489.4,1947.52,0,,,,
Bank Sta=4992.3,5007.8
XS Rating Curve= 0 ,0
Exp/Cntr=0.3,0.1

Type RM Length L Ch R = 1 ,135330  ,887,887,887
BEGIN DESCRIPTION:
Mapping XS 34f94a3c
END DESCRIPTION:
XS GIS Cut Line= 5
       1461292.5      6866536.51      1463438.94      6865684.09
      1463724.16      6863603.08      1463802.28      6862722.01
      1463649.28      6861153.25
#Sta/Elev= 30
   171.5 1961.73   812.7  1945.6   833.6 1939.85   882.2 1938.77   937.1 1944.53
  2051.5  1932.1  2267.1    1933  2272.5 1936.66  2291.4 1934.33  2296.8  1938.5
  2321.1 1934.73  2326.5 1938.74  2345.4 1936.31  2404.8 1940.47    2481 1939.68
  2507.3  1932.4  2550.3 1931.81  4883.2 1934.57  4990.2 1935.91  4992.3 1929.46
  4992.8 1928.96  5007.8 1929.46  5008.2 1933.62  5038.3 1929.46  5102.1 1934.73
  5286.7 1934.81  5447.8  1934.5  5606.6 1934.26  6988.1 1936.42  7042.2 1936.94
#Mann= 12 ,-1 , 0
   171.5     .07       0   812.7    .035       0   937.1     .07       0
  2051.5    .035       0  2550.3    .045       0  4883.2     .07       0
  4992.3     .07       0  5007.8     .07       0  5286.7     .12       0
  5447.8     .07       0  5606.6    .045       0  6988.1    .035       0
Levee=-1,2404.8,1940.47,0,,,,
Bank Sta=4992.3,5007.8
XS Rating Curve= 0 ,0
Exp/Cntr=0.3,0.1

Type RM Length L Ch R = 1 ,134443  ,1156,1156,1156
BEGIN DESCRIPTION:
Noodle Creek 75.0
END DESCRIPTION:
XS GIS Cut Line= 4
       1461316.8      6866573.84      1463881.97      6865567.62
      1464425.72      6862732.96       1464246.2      6861271.56
#Sta/Elev= 30
  -736.6 1962.12  -721.2 1962.45  -287.4 1948.22  -111.3 1948.76   -77.5 1941.38
   -29.6 1939.77      13 1944.35    1055 1934.34  1728.5 1929.61  1788.1 1933.47
  1807.2 1931.31  1812.6 1935.14  1891.2 1933.77  1896.6  1936.5  2021.2  1935.2
    2049 1930.04  2111.8  1929.2  4531.4 1931.46  4676.4 1932.51  4684.4 1932.65
  4828.9 1933.19  4980.8 1934.32  4990.8 1934.46  4992.3  1926.6  4992.8  1926.1
  5007.8  1926.6  5071.4 1932.73  5266.5 1930.41  6346.9 1932.94  6377.6 1934.08
#Mann= 15 ,-1 , 0
  -736.6    .035       0  -721.2     .07       0  -111.3    .035       0
      13     .07       0    1055    .035       0  2111.8    .045       0
  4531.4     .07       0  4676.4    .045       0  4684.4     .07       0
  4828.9     .16       0  4980.8     .12       0  4992.3     .07       0
  5007.8     .12       0  5266.5    .045       0  6346.9    .035       0
Levee=-1,1896.6,1936.5,0,,,,
Bank Sta=4992.3,5007.8
XS Rating Curve= 0 ,0
Exp/Cntr=0.3,0.1

Type RM Length L Ch R = 1 ,133287  ,959,959,959
BEGIN DESCRIPTION:
Noodle Creek 74.0
END DESCRIPTION:
XS GIS Cut Line= 4
      1461339.38      6866587.36      1464759.21      6865332.15
       1465478.6      6862717.51      1465460.33      6861521.06
#Sta/Elev= 30
 -1455.7 1962.25 -1415.6 1961.55 -1124.3 1950.58  -851.5 1947.49  -835.4 1948.24
  -810.6 1942.78    -768 1940.93  -715.6 1944.59   173.7 1935.09   252.9 1934.71
   510.3 1934.92  1434.6  1927.7  1839.1 1927.96    1942 1927.66  1953.1 1929.48
  2103.5 1928.48  2155.1 1927.01  2256.1 1923.54  3773.3 1925.39  4841.9 1929.76
  4988.5 1931.57  4992.2 1923.12  4992.7 1922.62  5007.8 1923.12  5008.5 1931.53
  5026.7 1923.94  5098.5 1930.75  5728.6 1926.21  6074.9 1928.41  6095.6  1929.6
#Mann= 17 ,-1 , 0
 -1455.7    .035       0 -1415.6     .07       0  -851.5    .035       0
  -715.6     .07       0   173.7    .063       0   252.9    .035       0
  1434.6    .063       0  1839.1    .035       0    1942    .063       0
  2103.5    .035       0  2155.1    .063       0  2256.1    .045       0
  4841.9     .07       0  4992.2     .07       0  5007.8     .07       0
  5026.7    .045       0  6074.9    .035       0
Levee=-1,1983.6,1929.4,0,,,,
#XS Ineff= 2 , 0
       0                  5098.5       0 1930.75
Permanent Ineff=
       F       F
Bank Sta=4992.2,5007.8
XS Rating Curve= 0 ,0
Exp/Cntr=0.3,0.1

Type RM Length L Ch R = 1 ,132328  ,548,548,548
BEGIN DESCRIPTION:
Noodle Creek 73.0
END DESCRIPTION:
XS GIS Cut Line= 5
       1461404.1      6866616.42      1465513.71      6865148.06
      1466312.06       6862752.2      1466349.44      6862415.78
      1466315.03      6861701.04
#Sta/Elev= 30
 -2256.1 1959.94 -2167.6 1950.19 -2068.5 1946.48 -2063.1 1950.25 -2006.9  1952.2
 -1671.1 1948.48   -1648 1943.59 -1591.8 1942.27 -1529.1 1944.16  -887.1 1936.94
  -434.4    1934   -87.9 1931.59   289.3 1929.42   640.6 1927.12  1591.4 1921.99
  1944.7 1924.82  2309.8 1921.31  2817.2 1921.77  3378.5 1922.57  3750.2  1923.5
  4470.2  1925.6  4775.1  1925.2  4979.6 1923.98  4992.2 1920.97  4992.7 1920.47
  5007.8 1920.97  5060.3  1923.8  5319.6 1924.43  5638.3 1925.53  5687.4 1926.64
#Mann= 20 ,-1 , 0
 -2256.1    .035       0 -2167.6     .07       0 -1529.1     .07       0
  -887.1    .063       0  -434.4    .035       0   -87.9    .045       0
   289.3    .035       0   640.6    .063       0  1591.4    .035       0
  2309.8    .045       0  2817.2    .045       0  3378.5    .035       0
  3750.2    .035       0  4470.2    .035       0  4775.1    .045       0
  4992.2    .045       0  5007.8    .045       0  5060.3    .035       0
  5319.6    .045       0  5638.3    .035       0
Levee=-1,1944.7,1924.82,0,,,,
Bank Sta=4992.2,5007.8
XS Rating Curve= 0 ,0
Exp/Cntr=0.3,0.1

Type RM Length L Ch R = 1 ,131780  ,889,889,889
BEGIN DESCRIPTION:
Mapping XS 7db703ef
END DESCRIPTION:
XS GIS Cut Line= 5
      1461709.09      6866627.58      1466234.73      6864955.01
      1466759.21      6862904.11      1467050.61      6861365.68
      1466925.61      6860275.43
#Sta/Elev= 30
 -2416.2 1950.63   -2122 1948.11   -1899 1943.59 -1434.3 1937.94 -1121.8 1935.76
  -588.4 1931.22     445 1926.74   669.3 1925.27   940.9 1923.27  1555.5 1922.62
    1998 1920.39  2266.1 1921.89  2408.6 1922.13  2446.8 1918.39  2845.5 1919.36
  4007.3 1920.34  4217.3 1922.46  4466.1 1923.41  4552.1 1925.96  4909.7 1921.03
    4949 1922.75  4989.7 1918.26  4990.2 1917.76  5010.4 1918.26  5011.9 1919.84
  5014.3 1922.37  5249.6 1923.44  5687.4 1923.49  6752.1  1927.5  7188.7 1928.53
#Mann= 20 ,-1 , 0
 -2416.2     .07       0   -1899     .07       0 -1434.3    .063       0
 -1121.8    .035       0  -588.4    .045       0     445    .045       0
   669.3    .063       0   940.9    .063       0  1555.5    .063       0
    1998    .063       0  2266.1    .035       0  2845.5    .035       0
  4217.3    .063       0  4466.1    .035       0  4989.7     .07       0
  5010.4     .16       0  5011.9    .045       0  5249.6    .035       0
  5687.4     .07       0  6752.1    .045       0
Levee=-1,2242.5,1922.55,0,,,,
Bank Sta=4989.7,5010.4
XS Rating Curve= 0 ,0
Exp/Cntr=0.3,0.1

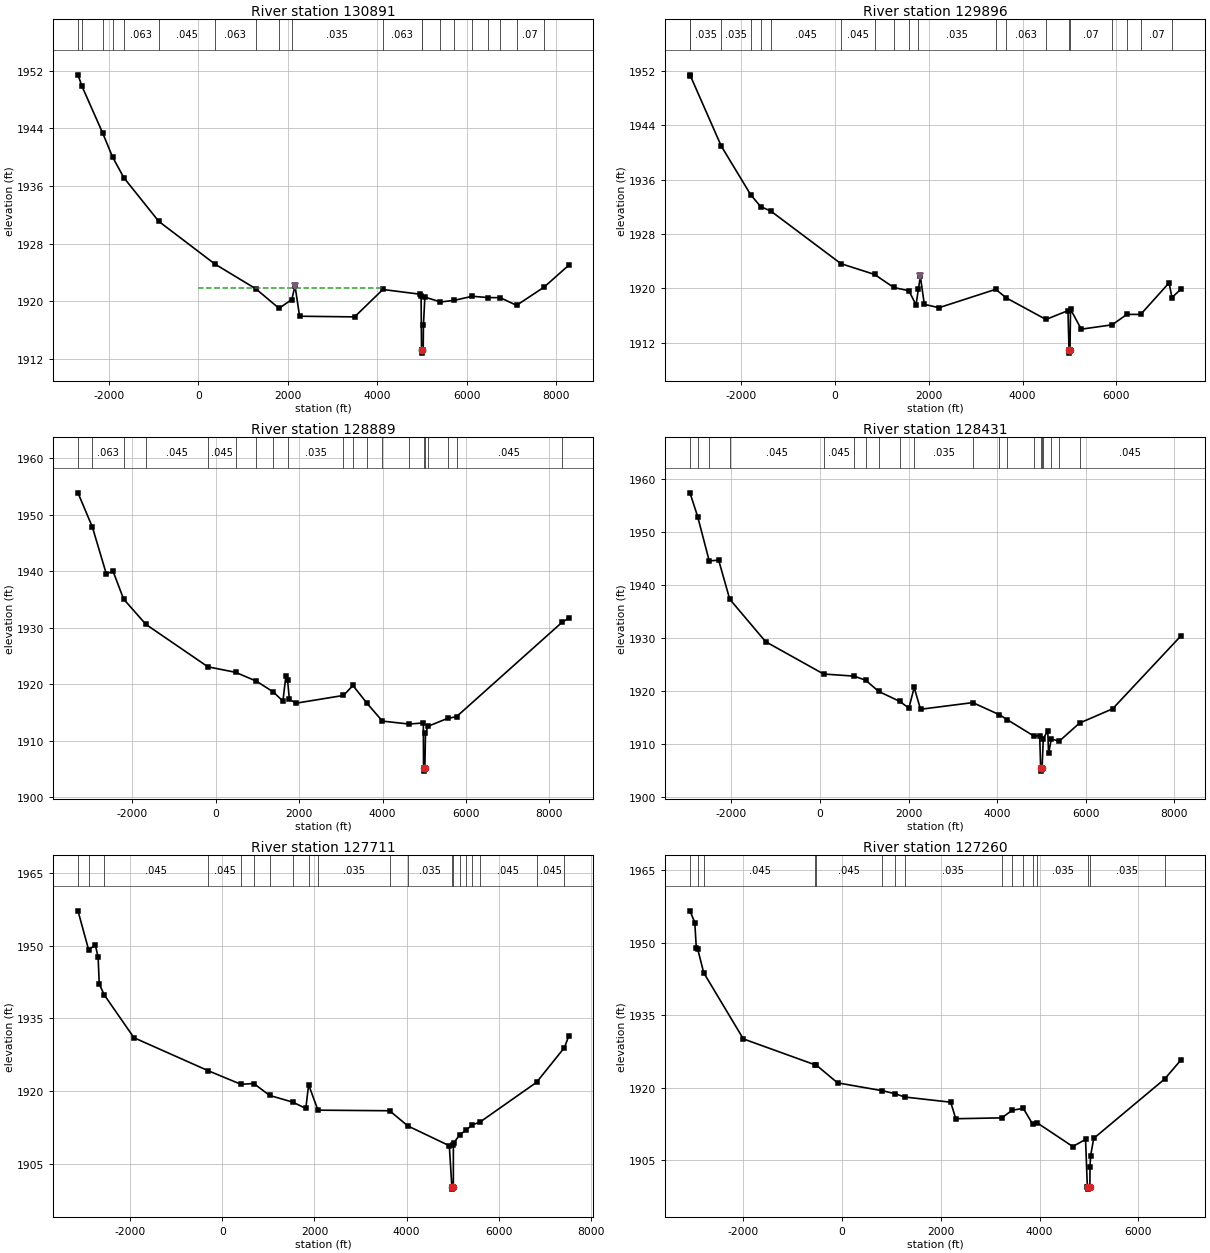
Type RM Length L Ch R = 1 ,130891  ,995,995,995
BEGIN DESCRIPTION:
Mapping XS 381e69fd
END DESCRIPTION:
XS GIS Cut Line= 6
      1461730.73      6866683.33       1466252.4      6864973.27
      1466303.64      6864939.73      1467349.45      6863281.68
      1467932.55      6861580.96      1469057.55      6859546.25
#Sta/Elev= 30
 -2694.5 1951.42 -2608.6 1949.89   -2141 1943.33 -1920.1 1940.01   -1667 1937.13
  -886.2 1931.08   368.6 1925.16  1282.5 1921.73  1802.5 1919.02  2088.3 1920.24
  2159.6 1922.15  2262.1 1917.92  3492.6 1917.83    4124 1921.63    4964 1920.97
  4979.2  1920.7  4989.6  1913.3  4990.1  1912.8  5010.4  1913.3  5026.5  1913.3
    5032  1916.7  5063.8 1920.58  5412.9  1919.9  5717.1 1920.12  6125.7 1920.69
  6477.7 1920.51  6751.2 1920.49  7114.3 1919.43  7728.2 1921.95  8284.2 1925.01
#Mann= 20 ,-1 , 0
 -2694.5     .07       0 -2608.6    .035       0   -2141     .07       0
 -1920.1    .035       0   -1667    .063       0  -886.2    .045       0
   368.6    .063       0  1282.5    .063       0  1802.5    .063       0
  2088.3    .035       0    4124    .063       0  4989.6    .045       0
  5010.4    .045       0  5412.9     .07       0  5717.1    .045       0
  6125.7    .045       0  6477.7    .045       0  6751.2    .045       0
  7114.3     .07       0  7728.2    .045       0
Levee=-1,2159.6,1922.15,0,,,,
#XS Ineff= 2 , 0
       0  4103.4 1921.79               0
Permanent Ineff=
       F       F
Bank Sta=4989.6,5010.4
XS Rating Curve= 0 ,0
Exp/Cntr=0.3,0.1

Type RM Length L Ch R = 1 ,129896  ,1007,1007,1007
BEGIN DESCRIPTION:
Mapping XS 47fe6989
END DESCRIPTION:
XS GIS Cut Line= 6
      1461812.46      6866727.27      1466243.94      6865052.44
      1467553.64      6863684.24      1468196.44       6863400.4
      1468731.17      6862358.73      1470085.29      6860962.95
#Sta/Elev= 30
 -3078.7 1951.44   -3072 1951.33 -2412.4 1940.94 -1788.2  1933.8 -1574.2 1932.02
 -1360.2 1931.38   134.8 1923.62   851.1 1922.03  1258.7 1920.11  1581.9 1919.63
  1733.5 1917.54  1783.5 1919.85  1825.3 1921.74  1910.2 1917.63  2221.2 1917.13
  3429.7 1919.84  3656.4 1918.57    4499  1915.4  4967.9  1916.7  4989.6 1910.94
  4990.1 1910.44  5010.4 1910.94  5022.5 1916.89  5250.7 1913.97  5908.3 1914.61
    6222 1916.15  6514.8 1916.14  7119.7 1920.79  7181.7 1918.63    7371 1919.86
#Mann= 20 ,-1 , 0
 -3078.7     .07       0   -3072    .035       0 -2412.4    .035       0
 -1788.2     .07       0 -1574.2     .07       0 -1360.2    .045       0
   134.8    .045       0   851.1    .063       0  1258.7    .035       0
  1581.9    .063       0  1783.5    .035       0  3429.7    .035       0
  3656.4    .063       0    4499    .035       0  4989.6     .07       0
  5010.4     .07       0  5908.3    .035       0    6222     .07       0
  6514.8     .07       0  7181.7    .045       0
Levee=-1,1825.3,1921.74,0,,,,
Bank Sta=4989.6,5010.4
XS Rating Curve= 0 ,0
Exp/Cntr=0.3,0.1

Type RM Length L Ch R = 1 ,128889  ,458,458,458
BEGIN DESCRIPTION:
Mapping XS f2f6007f
END DESCRIPTION:
XS GIS Cut Line= 6
      1461893.33      6866772.77      1466414.08      6865000.45
      1467632.22      6863777.63      1468661.72      6863351.79
      1470633.94      6862893.46      1472181.25      6861540.43
#Sta/Elev= 30
 -3307.8 1953.84 -2961.8 1947.78 -2629.1 1939.54 -2464.3 1939.94 -2212.6 1935.05
 -1677.5 1930.57  -188.7 1923.06     474 1922.09   975.4 1920.52  1383.7 1918.59
  1609.2 1916.99  1680.5 1921.35  1722.3 1920.65  1765.2 1917.29  1927.9 1916.63
  3063.4    1918  3290.4 1919.76    3630 1916.59  3996.1 1913.46  4635.7 1912.94
  4979.4 1913.13  4984.1 1905.11  4984.6 1904.61  5015.9 1905.11  5030.8 1911.34
  5091.6 1912.54  5559.8 1913.94  5775.7 1914.24  8311.1 1930.96  8471.1 1931.68
#Mann= 20 ,-1 , 0
 -3307.8    .035       0 -2961.8    .063       0 -2212.6    .045       0
 -1677.5    .045       0  -188.7    .045       0     474    .063       0
   975.4    .035       0  1383.7    .063       0  1722.3    .035       0
  3063.4    .063       0  3290.4    .063       0    3630    .063       0
  3996.1    .035       0  4635.7    .035       0  4984.1    .045       0
  5015.9    .045       0  5091.6     .07       0  5559.8    .045       0
  5775.7    .045       0  8311.1    .045       0
Bank Sta=4984.1,5015.9
XS Rating Curve= 0 ,0
Exp/Cntr=0.3,0.1

Type RM Length L Ch R = 1 ,128431  ,720,720,720
BEGIN DESCRIPTION:
Mapping XS 5eee7404
END DESCRIPTION:
XS GIS Cut Line= 6
      1461975.01      6866821.35      1465961.08      6865324.83
      1466426.36       6865029.7      1467779.44      6863907.14
       1471213.8      6863032.34      1472144.34      6862747.63
#Sta/Elev= 30
 -2935.1 1957.47 -2760.1 1952.94 -2500.5 1944.59 -2287.2 1944.74 -2037.9 1937.36
 -1226.1 1929.31    81.8  1923.2   770.4  1922.8  1030.9 1922.03  1327.6  1919.9
  1800.2 1918.03  2008.3 1916.75    2128 1920.66  2270.8 1916.53  3450.3 1917.79
  4051.5  1915.5  4224.8 1914.59  4824.9 1911.49  4961.8 1911.54  4984.1 1905.33
  4984.6 1904.83  5015.9 1905.33  5042.6 1910.98  5143.9 1912.48  5162.1 1908.18
  5225.8 1910.95  5399.6 1910.47    5862 1913.92  6609.6 1916.62  8149.8  1930.4
#Mann= 20 ,-1 , 0
 -2935.1    .035       0 -2760.1    .035       0 -2500.5    .063       0
 -2037.9    .045       0    81.8    .045       0   770.4    .063       0
  1030.9    .045       0  1327.6    .035       0  1800.2    .063       0
    2128    .035       0  3450.3    .035       0  4051.5    .063       0
  4224.8    .035       0  4824.9    .035       0  4984.1    .035       0
  5015.9    .035       0  5042.6     .16       0  5225.8    .035       0
  5399.6     .07       0    5862    .045       0
Bank Sta=4984.1,5015.9
XS Rating Curve= 0 ,0
Exp/Cntr=0.3,0.1

Type RM Length L Ch R = 1 ,127711  ,451,451,451
BEGIN DESCRIPTION:
Mapping XS 8ebadeab
END DESCRIPTION:
XS GIS Cut Line= 6
      1462149.15      6866848.37      1466017.36       6865372.3
      1466978.27      6864648.12      1469422.14      6863983.73
      1471019.36      6863435.12      1472088.81      6863199.01
#Sta/Elev= 30
 -3136.5 1957.14 -2905.6 1949.15 -2758.9 1950.06 -2698.7 1947.63   -2674 1942.07
 -2562.9 1939.82 -1920.8 1931.04  -309.4 1924.26   402.4 1921.46   682.9 1921.62
  1025.6 1919.17    1533 1917.78  1812.2 1916.49  1872.6 1921.38  2075.5 1916.14
  3632.4 1916.02  4026.9  1912.9  4928.3 1908.83  4984.1  1900.4  4984.6  1899.9
    5016  1900.4  5016.8 1908.91  5022.1 1909.38  5155.4  1911.1  5296.6 1912.07
    5432 1913.15    5585 1913.63  6822.2 1921.86  7428.8 1929.01  7524.8 1931.46
#Mann= 20 ,-1 , 0
 -3136.5    .094       0 -2905.6    .035       0 -2562.9    .045       0
  -309.4    .045       0   402.4    .063       0   682.9    .045       0
  1025.6    .035       0    1533    .063       0  1872.6    .035       0
  2075.5    .035       0  3632.4    .035       0  4026.9    .035       0
  4984.1    .035       0    5016    .035       0  5155.4    .035       0
  5296.6     .07       0    5432    .035       0    5585    .045       0
  6822.2    .045       0  7428.8     .07       0
Bank Sta=4984.1,5016
XS Rating Curve= 0 ,0
Exp/Cntr=0.3,0.1

Type RM Length L Ch R = 1 ,127260  ,347,347,347
BEGIN DESCRIPTION:
Noodle Creek 72.0
END DESCRIPTION:
XS GIS Cut Line= 5
      1462363.75      6866880.47      1466289.09      6865461.21
      1466549.51      6865092.28      1470061.03      6864226.79
      1471655.03      6863637.99
#Sta/Elev= 30
 -3081.8 1956.57 -2984.8 1954.15 -2952.9 1948.84 -2927.6 1948.77 -2803.9 1943.77
 -2001.1 1930.08  -545.1 1924.71  -521.5 1924.65   -93.6 1920.99   816.3 1919.36
  1066.8 1918.76  1267.5 1918.06  2198.3 1916.99  2301.3 1913.57  3233.3 1913.75
  3440.8  1915.3  3667.7 1915.73  3855.9 1912.49  3939.8 1912.79  4669.9 1907.82
  4929.2 1909.29  4965.5 1899.51  4983.9 1899.51  4984.4 1899.01  5016.2 1899.51
  5020.3 1903.68  5030.6 1905.85  5095.1 1909.51  6529.7 1921.77  6859.7  1925.7
#Mann= 16 ,-1 , 0
 -3081.8    .063       0 -2927.6    .035       0 -2803.9    .045       0
  -545.1    .035       0  -521.5    .045       0   816.3    .035       0
  1066.8    .063       0  1267.5    .035       0  3233.3    .063       0
  3440.8    .094       0  3667.7    .035       0  3855.9    .063       0
  3939.8    .035       0  4983.9    .035       0  5016.2    .035       0
  6529.7    .063       0
Bank Sta=4983.9,5016.2
XS Rating Curve= 0 ,0
Exp/Cntr=0.3,0.1

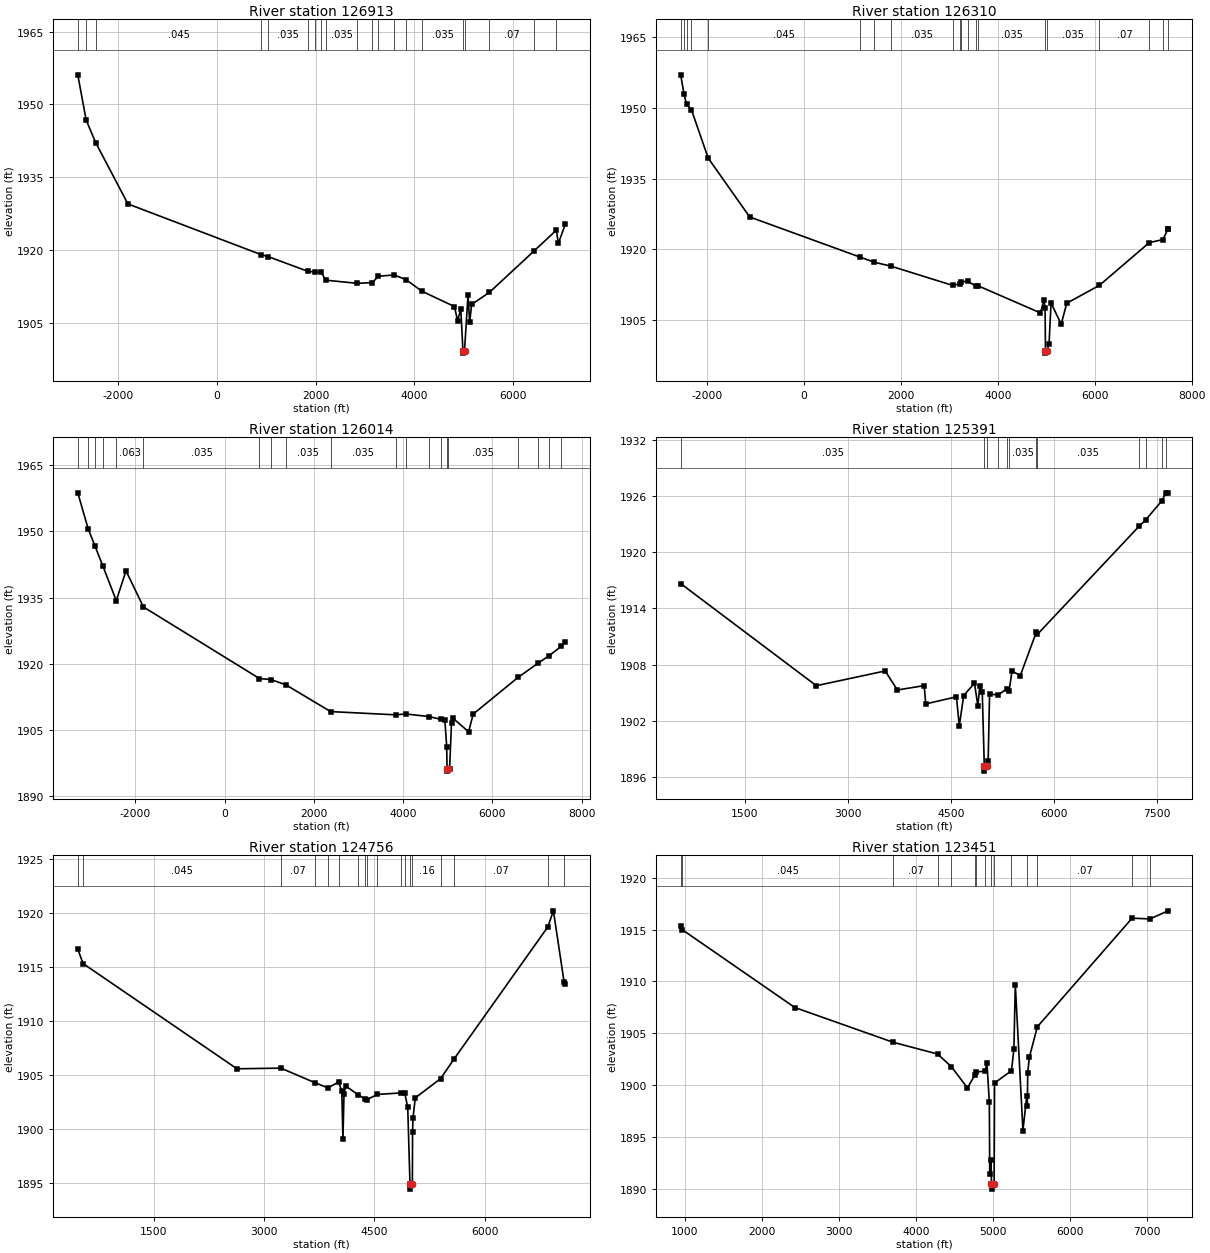
Type RM Length L Ch R = 1 ,126913  ,603,603,603
BEGIN DESCRIPTION:
Mapping XS e965443c
END DESCRIPTION:
XS GIS Cut Line= 6
      1462436.64      6866911.73      1466186.66      6865965.55
      1467219.64      6865331.87      1470440.13      6864429.09
      1470804.71      6864116.59      1471672.75      6863691.25
#Sta/Elev= 30
 -2815.3 1956.09 -2646.5 1946.81 -2452.7 1942.13 -1799.9 1929.52   899.5 1919.08
  1046.4 1918.66  1839.2 1915.67    1996 1915.49  2109.9 1915.48  2209.4 1913.83
  2848.4 1913.18  3148.8 1913.34  3273.5 1914.65  3593.7  1914.9    3834 1913.92
  4155.6 1911.55    4813  1908.4  4875.4 1905.49  4941.2 1907.87  4983.8 1899.32
  4984.4 1898.82  5016.2 1899.32  5086.8 1910.79  5120.6 1905.13  5159.6 1908.83
  5521.9 1911.34  6416.5 1919.77  6875.6 1924.12  6917.1 1921.41  7055.6 1925.31
#Mann= 20 ,-1 , 0
 -2815.3    .035       0 -2646.5    .035       0 -2452.7    .045       0
   899.5     .07       0  1046.4    .035       0  1839.2    .063       0
    1996    .035       0  2109.9    .063       0  2209.4    .035       0
  2848.4    .063       0  3148.8    .063       0  3273.5    .035       0
  3593.7    .063       0    3834    .035       0  4155.6    .035       0
  4983.8    .035       0  5016.2    .035       0  5521.9     .07       0
  6416.5    .035       0  6875.6    .063       0
Bank Sta=4983.8,5016.2
XS Rating Curve= 0 ,0
Exp/Cntr=0.3,0.1

Type RM Length L Ch R = 1 ,126310  ,296,296,296
BEGIN DESCRIPTION:
Noodle Creek 71.0
END DESCRIPTION:
XS GIS Cut Line= 6
      1462387.16      6866955.84      1466199.92      6866296.23
      1467512.42      6865643.46      1469977.69      6865039.29
      1470845.75      6864240.68      1471706.83      6863726.81
#Sta/Elev= 30
 -2542.3 1957.02 -2474.8 1953.03   -2422 1950.77   -2321 1949.64 -1974.3 1939.36
 -1118.2 1926.88  1166.6 1918.34  1454.3 1917.28  1800.2 1916.44    3069 1912.37
  3210.7 1912.71  3250.6 1913.17  3385.8 1913.22  3550.1  1912.2  3601.8 1912.25
  4880.8 1906.53  4953.3 1909.35  4975.8 1907.58  4983.8 1898.51  4984.3 1898.01
  5016.2 1898.51  5057.1 1899.85  5098.9 1908.66  5308.1 1904.14  5423.1 1908.59
  6097.6 1912.39  7126.7 1921.45  7406.8 1922.08  7512.1 1924.34  7514.1 1924.34
#Mann= 20 ,-1 , 0
 -2542.3    .063       0 -2474.8    .035       0   -2422    .063       0
   -2321    .035       0 -1974.3    .045       0  1166.6    .035       0
  1454.3     .07       0  1800.2    .035       0    3069    .063       0
  3210.7    .035       0  3250.6    .063       0  3385.8    .035       0
  3550.1    .063       0  3601.8    .035       0  4983.8    .035       0
  5016.2    .035       0  6097.6     .07       0  7126.7    .035       0
  7406.8    .063       0  7512.1    .035       0
Bank Sta=4983.8,5016.2
XS Rating Curve= 0 ,0
Exp/Cntr=0.3,0.1

Type RM Length L Ch R = 1 ,126014  ,623,623,623
BEGIN DESCRIPTION:
Noodle Creek 70.0
END DESCRIPTION:
XS GIS Cut Line= 6
      1461824.63      6867055.61      1467220.75      6866976.79
      1468005.47      6866740.68      1469408.25      6865567.07
       1471026.3      6864317.07      1471755.48      6863907.34
#Sta/Elev= 30
 -3293.4 1958.74 -3061.8 1950.62   -2909  1946.7 -2731.5 1942.15 -2430.3 1934.29
 -2212.9 1941.07 -1822.9 1932.87   779.5 1916.63  1039.1  1916.4  1375.9 1915.18
  2374.3 1909.14  3837.2  1908.4  4053.6 1908.61  4576.8 1908.01  4837.7 1907.41
  4934.6 1907.28  4976.2 1901.18  4983.8 1896.14  4984.3 1895.64  5016.2 1896.14
  5040.5 1896.14    5084 1906.66  5119.3 1907.59    5468 1904.56    5569 1908.57
  6573.4 1916.87    7029 1920.15  7277.8 1921.85  7544.4 1923.94  7632.8 1924.91
#Mann= 20 ,-1 , 0
 -3293.4    .125       0 -3061.8    .094       0   -2909    .063       0
 -2731.5    .094       0 -2430.3    .063       0 -1822.9    .035       0
   779.5    .063       0  1039.1     .07       0  1375.9    .035       0
  2374.3    .035       0  3837.2    .063       0  4053.6    .035       0
  4576.8    .125       0  4837.7    .035       0  4983.8    .035       0
  5016.2    .035       0  6573.4     .07       0    7029     .07       0
  7277.8    .035       0  7544.4    .063       0
Bank Sta=4983.8,5016.2
XS Rating Curve= 0 ,0
Exp/Cntr=0.3,0.1

Type RM Length L Ch R = 1 ,125391  ,635,635,635
BEGIN DESCRIPTION:
Noodle Creek 69.0
END DESCRIPTION:
XS GIS Cut Line= 5
      1465971.33      6867371.18      1467464.38      6867475.34
      1468637.99      6866996.18      1469790.77      6866010.06
      1471928.28       6864191.8
#Sta/Elev= 30
   568.8 1916.67  2541.4 1905.73  3542.2 1907.31    3720 1905.27  4109.7 1905.74
  4131.7 1903.78  4578.5 1904.54  4620.2 1901.44  4684.6 1904.68  4840.8    1906
  4890.2 1903.57  4918.8  1905.7  4953.9 1905.04  4983.8 1897.08  4984.3 1896.58
  5016.3 1897.08  5039.5 1897.66  5060.4 1904.86  5179.9 1904.72  5317.9 1905.42
    5345  1905.2  5386.6  1907.3  5507.4 1906.82  5740.1 1911.47  5757.1 1911.24
  7238.2 1922.84  7329.1 1923.48  7564.1 1925.53  7622.2 1926.33  7656.4 1926.39
#Mann= 12 ,-1 , 0
   568.8    .035       0  4983.8    .035       0  5016.3    .035       0
  5179.9     .07       0  5317.9    .063       0    5345    .035       0
  5740.1     .07       0  5757.1    .035       0  7238.2    .063       0
  7329.1    .035       0  7564.1    .063       0  7622.2    .035       0
Bank Sta=4983.8,5016.3
XS Rating Curve= 0 ,0
Exp/Cntr=0.3,0.1

Type RM Length L Ch R = 1 ,124756  ,1305,1305,1305
BEGIN DESCRIPTION:
Noodle Creek 68.0
END DESCRIPTION:
XS GIS Cut Line= 3
      1465936.57      6867676.73      1468353.27      6867537.84
      1471943.57      6865357.27
#Sta/Elev= 30
   471.3 1916.66   543.7 1915.32  2633.3 1905.56  3230.5 1905.62  3698.6 1904.25
  3869.1 1903.79  4014.6 1904.33  4057.6 1903.48  4073.1 1899.01  4087.4 1903.18
  4109.9 1903.97  4278.4 1903.15  4372.1 1902.77  4393.3 1902.68  4540.8 1903.18
  4867.7 1903.32  4913.5 1903.28  4953.2 1901.97  4983.8 1894.89  4984.3 1894.39
  5016.3 1894.89  5018.9 1899.72  5024.8    1901  5055.8 1902.86    5400 1904.65
  5578.5 1906.43  6855.7 1918.72  6931.9 1920.22  7078.1 1913.58  7092.6 1913.46
#Mann= 18 ,-1 , 0
   471.3    .035       0   543.7    .045       0  3230.5     .07       0
  3698.6    .035       0  3869.1    .045       0  4014.6    .035       0
  4278.4     .16       0  4372.1     .07       0  4393.3    .035       0
  4540.8     .07       0  4867.7    .035       0  4913.5     .16       0
  4983.8     .07       0  5016.3     .16       0    5400    .035       0
  5578.5     .07       0  6855.7    .035       0  7078.1     .07       0
Bank Sta=4983.8,5016.3
XS Rating Curve= 0 ,0
Exp/Cntr=0.3,0.1

Type RM Length L Ch R = 1 ,123451  ,1174,1174,1174
BEGIN DESCRIPTION:
Mapping XS 8f999cf3
END DESCRIPTION:
XS GIS Cut Line= 4
      1465936.65      6868017.01      1468228.27       6867843.4
      1471137.99      6866836.45      1471921.37      6866295.72
#Sta/Elev= 30
   947.2 1915.31   966.1    1915  2429.8 1907.49  3706.4 1904.14  4282.7 1903.01
  4462.7 1901.79  4670.5 1899.74  4766.5 1900.98  4777.7 1901.29  4899.7 1901.35
  4923.8 1902.16  4954.9 1898.37  4960.2 1891.45  4977.4 1892.77  4982.7 1890.49
  4983.4 1889.99  5017.3 1890.49  5022.6 1900.22  5242.3  1901.4  5273.6 1903.46
  5292.4 1909.68  5391.2 1895.64  5440.5 1898.96  5448.2 1897.99  5453.5 1901.21
  5474.1 1902.68    5578 1905.63  6808.5  1916.1  7041.6 1916.03  7276.3 1916.81
#Mann= 15 ,-1 , 0
   947.2    .035       0   966.1    .045       0  3706.4     .07       0
  4282.7    .045       0  4462.7    .035       0  4766.5     .07       0
  4777.7    .035       0  4899.7     .16       0  4982.7     .07       0
  5017.3     .16       0  5242.3     .07       0  5440.5     .16       0
    5578     .07       0  6808.5    .035       0  7041.6    .045       0
Bank Sta=4982.7,5017.3
XS Rating Curve= 0 ,0
Exp/Cntr=0.3,0.1