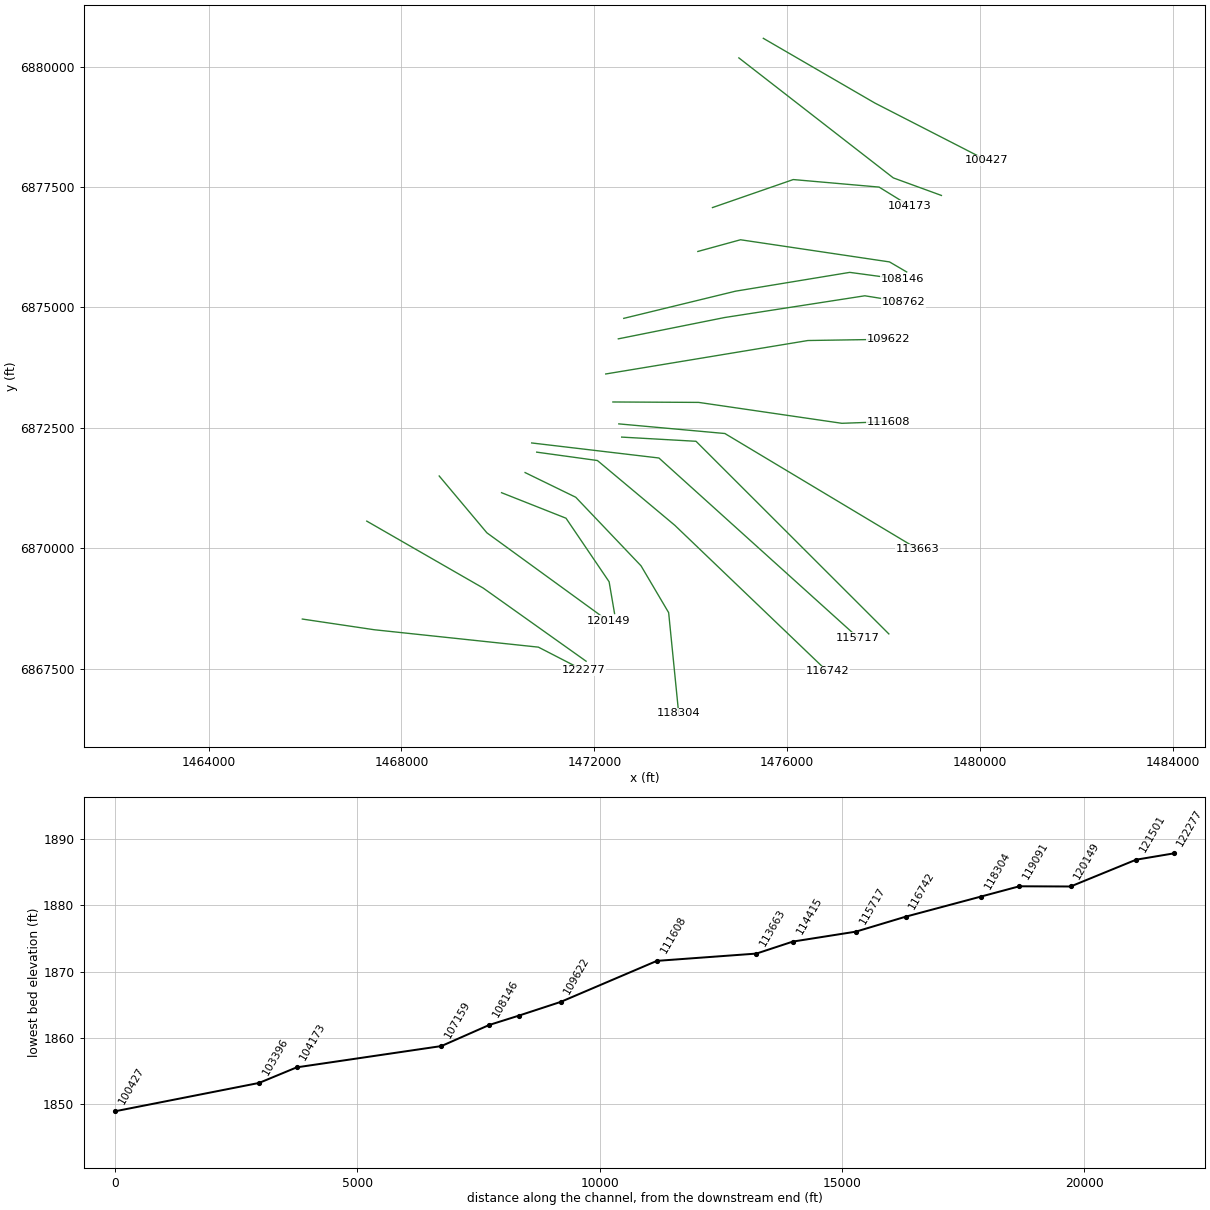
HEC-RAS study Noodle Creek.prj: Noodle Creek Base Level Engineering

--- Noodle Creek.g01 (geometry) --- (continued)

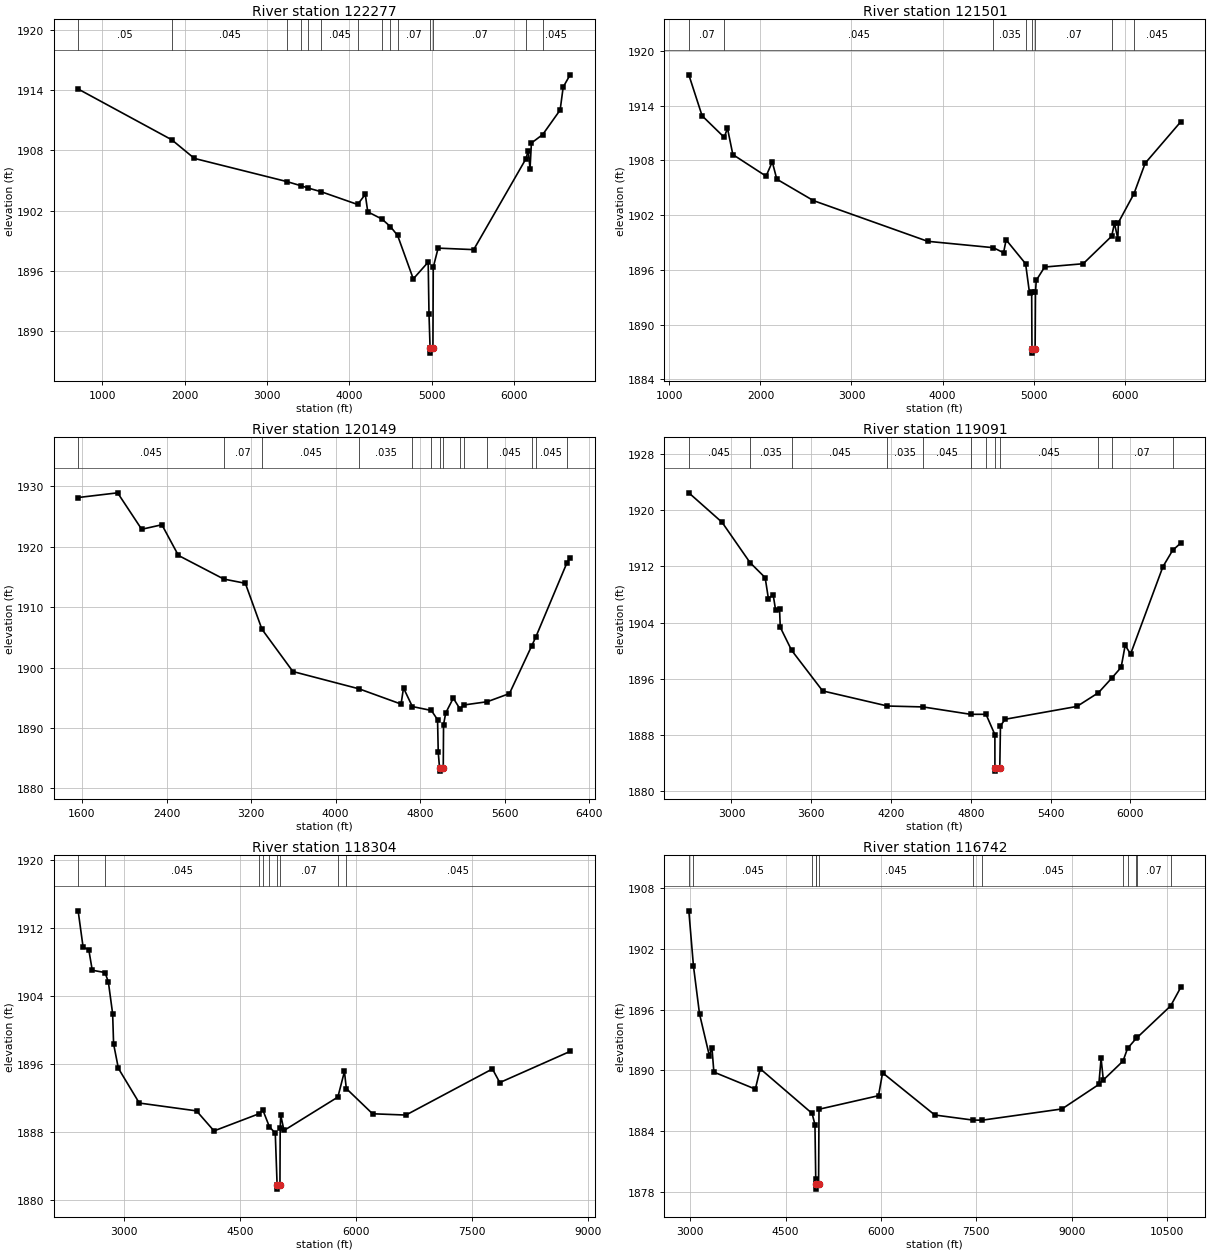
Type RM Length L Ch R = 1 ,122277  ,776,776,776
BEGIN DESCRIPTION:
Mapping XS 2da12238
END DESCRIPTION:
XS GIS Cut Line= 4
      1465943.57      6868530.89      1467436.61      6868308.68
      1470839.38      6867947.56       1471769.9      6867468.42
#Sta/Elev= 30
   706.4 1914.09  1844.1 1909.04  2118.4 1907.19  3245.5 1904.88    3411 1904.48
  3494.1 1904.26    3662 1903.87  4101.9 1902.61  4195.3 1903.61  4225.5 1901.88
  4397.7 1901.16  4501.7  1900.4  4588.1 1899.53  4778.6 1895.21  4959.6 1896.88
  4969.6 1891.69  4982.7 1888.33  4983.4 1887.83  5017.3 1888.33  5021.3 1896.36
  5080.3 1898.27  5512.7 1898.12  6145.9 1907.13  6175.2 1907.95  6197.3 1906.17
  6213.9 1908.72    6351 1909.56    6563    1912  6600.2 1914.29  6684.4  1915.5
#Mann= 14 ,-1 , 0
   706.4     .05       0  1844.1    .045       0  3245.5     .07       0
    3411    .045       0  3494.1     .07       0    3662    .045       0
  4101.9    .035       0  4397.7     .07       0  4501.7    .035       0
  4588.1     .07       0  4982.7     .07       0  5017.3     .07       0
  6145.9    .035       0    6351    .045       0
Bank Sta=4982.7,5017.3
XS Rating Curve= 0 ,0
Exp/Cntr=0.3,0.1

Type RM Length L Ch R = 1 ,121501  ,1352,1352,1352
BEGIN DESCRIPTION:
Noodle Creek 67.0
END DESCRIPTION:
XS GIS Cut Line= 3
      1467280.37      6870563.88      1469693.55      6869174.99
      1471828.93      6867655.92
#Sta/Elev= 30
    1213 1917.39  1358.8  1912.9  1601.6 1910.54  1637.6 1911.53  1696.5 1908.65
  2061.6 1906.28  2129.8 1907.85  2179.4 1905.95  2581.8  1903.6  3836.3 1899.14
  4557.9 1898.44  4670.7 1897.89  4698.6  1899.3  4912.7 1896.68  4956.3 1893.43
  4979.4 1893.62  4982.6 1887.38  4983.4 1886.88  5017.4 1887.38  5021.2 1893.53
  5029.8 1894.86    5122 1896.32  5545.4 1896.68  5858.4  1899.7    5889 1901.13
  5925.8 1899.41  5932.4  1901.2    6103 1904.35  6226.3  1907.7  6617.9 1912.25
#Mann= 8 ,-1 , 0
    1213     .07       0  1601.6    .045       0  4557.9    .035       0
  4912.7     .07       0  4982.6     .07       0  5017.4     .07       0
  5858.4    .035       0    6103    .045       0
Bank Sta=4982.6,5017.4
XS Rating Curve= 0 ,0
Exp/Cntr=0.3,0.1

Type RM Length L Ch R = 1 ,120149  ,1058,1058,1058
BEGIN DESCRIPTION:
Noodle Creek 66.0
END DESCRIPTION:
XS GIS Cut Line= 3
      1468782.11      6871501.36      1469771.68      6870320.83
      1472289.04      6868489.23
#Sta/Elev= 30
    1564 1928.17  1937.3 1928.95    2165 1922.91  2356.2 1923.66  2512.3 1918.58
  2942.1 1914.66  3145.6 1913.96  3302.5 1906.35  3595.3 1899.34  4221.9 1896.47
  4618.5 1893.95  4641.6 1896.62  4725.1 1893.54  4905.1 1892.89  4963.6 1891.36
  4970.1 1885.97  4982.5 1883.34  4983.3 1882.84  5017.5 1883.34  5020.3 1890.55
  5041.2 1892.49  5112.3 1894.93  5174.3 1893.19  5216.7 1893.81  5433.8 1894.34
  5643.7 1895.69  5854.4  1903.6    5892 1905.02  6186.6 1917.32  6217.6 1918.23
#Mann= 14 ,-1 , 0
    1564    .045       0  2942.1     .07       0  3302.5    .045       0
  4221.9    .035       0  4725.1    .045       0  4905.1     .07       0
  4982.5     .07       0  5017.5     .07       0  5174.3    .045       0
  5216.7    .035       0  5433.8    .045       0  5854.4     .07       0
    5892    .045       0  6186.6     .07       0
Bank Sta=4982.5,5017.5
XS Rating Curve= 0 ,0
Exp/Cntr=0.3,0.1

Type RM Length L Ch R = 1 ,119091  ,787,787,787
BEGIN DESCRIPTION:
Mapping XS bd73883f
END DESCRIPTION:
XS GIS Cut Line= 4
      1470075.45      6871154.18       1471412.3      6870624.65
       1472306.4       6869305.2      1472419.25      6868645.43
#Sta/Elev= 30
  2679.1 1922.45    2929 1918.26  3139.4 1912.53  3253.3 1910.39  3277.6 1907.42
  3313.2 1907.98  3331.7 1905.81  3361.4 1905.98    3367 1903.33  3452.1 1900.06
  3685.7 1894.28  4173.3 1892.13  4440.8    1892  4798.7 1890.95  4914.8 1890.95
  4981.5 1888.06  4981.7 1883.37  4982.6 1882.87  5018.3 1883.37  5023.5 1889.33
  5059.5 1890.25  5598.8 1892.07  5760.3 1894.02  5858.9 1896.06  5931.2 1897.63
  5961.6 1900.76  6002.2 1899.52  6245.7 1911.95  6318.3 1914.26  6380.2 1915.32
#Mann= 12 ,-1 , 0
  2679.1    .045       0  3139.4    .035       0  3452.1    .045       0
  4173.3    .035       0  4440.8    .045       0  4798.7     .07       0
  4914.8    .045       0  4981.7    .045       0  5018.3    .045       0
  5760.3    .035       0  5858.9     .07       0  6318.3    .045       0
Bank Sta=4981.7,5018.3
XS Rating Curve= 0 ,0
Exp/Cntr=0.3,0.1

Type RM Length L Ch R = 1 ,118304  ,1562,1562,1562
BEGIN DESCRIPTION:
Mapping XS 052e307d
END DESCRIPTION:
XS GIS Cut Line= 5
      1470563.85      6871571.96       1471614.2      6871059.81
      1472968.36       6869636.2      1473541.28      6868663.98
      1473749.56      6866572.45
#Sta/Elev= 30
  2408.1 1913.98  2472.4  1909.7  2545.5 1909.44  2590.6 1907.01  2755.6 1906.74
    2799 1905.64  2854.4  1901.9  2866.6 1898.37  2928.6  1895.5    3199 1891.43
  3939.1 1890.51  4165.6 1888.16  4752.7 1890.19    4796 1890.64  4881.7 1888.65
  4957.9 1887.89  4981.7 1881.83  4982.6 1881.33  5018.4 1881.83  5021.5 1888.51
  5028.4 1890.01  5070.8 1888.21  5767.4 1892.13  5852.8 1895.14  5876.7 1893.13
  6216.4 1890.17  6647.8 1890.02  7766.7 1895.43  7861.8 1893.83  8771.8 1897.49
#Mann= 9 ,-1 , 0
  2408.1    .035       0  2755.6    .045       0  4752.7     .07       0
    4796    .045       0  4881.7     .07       0  4981.7    .045       0
  5018.4     .07       0  5767.4    .035       0  5876.7    .045       0
Bank Sta=4981.7,5018.4
XS Rating Curve= 0 ,0
Exp/Cntr=0.3,0.1

Type RM Length L Ch R = 1 ,116742  ,1025,1025,1025
BEGIN DESCRIPTION:
Mapping XS e7655eb0
END DESCRIPTION:
XS GIS Cut Line= 4
      1470804.64      6871996.18      1472063.34      6871822.56
      1473669.24      6870477.08      1476828.97      6867447.56
#Sta/Elev= 30
  2976.1 1905.77  3048.6 1900.34  3144.4 1895.59  3299.5 1891.45  3339.9 1892.25
  3370.3 1889.84  4022.6 1888.16  4099.6 1890.17    4916 1885.76  4961.1 1884.65
  4973.5 1879.27  4981.6 1878.78  4982.5 1878.28  5018.4 1878.78  5024.9 1886.17
  5961.6 1887.51  6025.4 1889.77  6847.5  1885.6  7447.7  1885.1  7592.3 1885.09
  8848.9  1886.2  9428.8 1888.62  9464.3 1891.21  9499.5 1889.06  9809.6 1890.93
  9880.8 1892.18 10018.3 1893.18 10036.6 1893.28 10559.1 1896.38 10719.2 1898.22
#Mann= 13 ,-1 , 0
  2976.1    .035       0  3048.6    .045       0    4916     .07       0
  4973.5    .045       0  4981.6    .045       0  5018.4    .045       0
  7447.7    .035       0  7592.3    .045       0  9809.6    .035       0
  9880.8     .07       0 10018.3    .045       0 10036.6     .07       0
 10559.1    .035       0
Bank Sta=4981.6,5018.4
XS Rating Curve= 0 ,0
Exp/Cntr=0.3,0.1

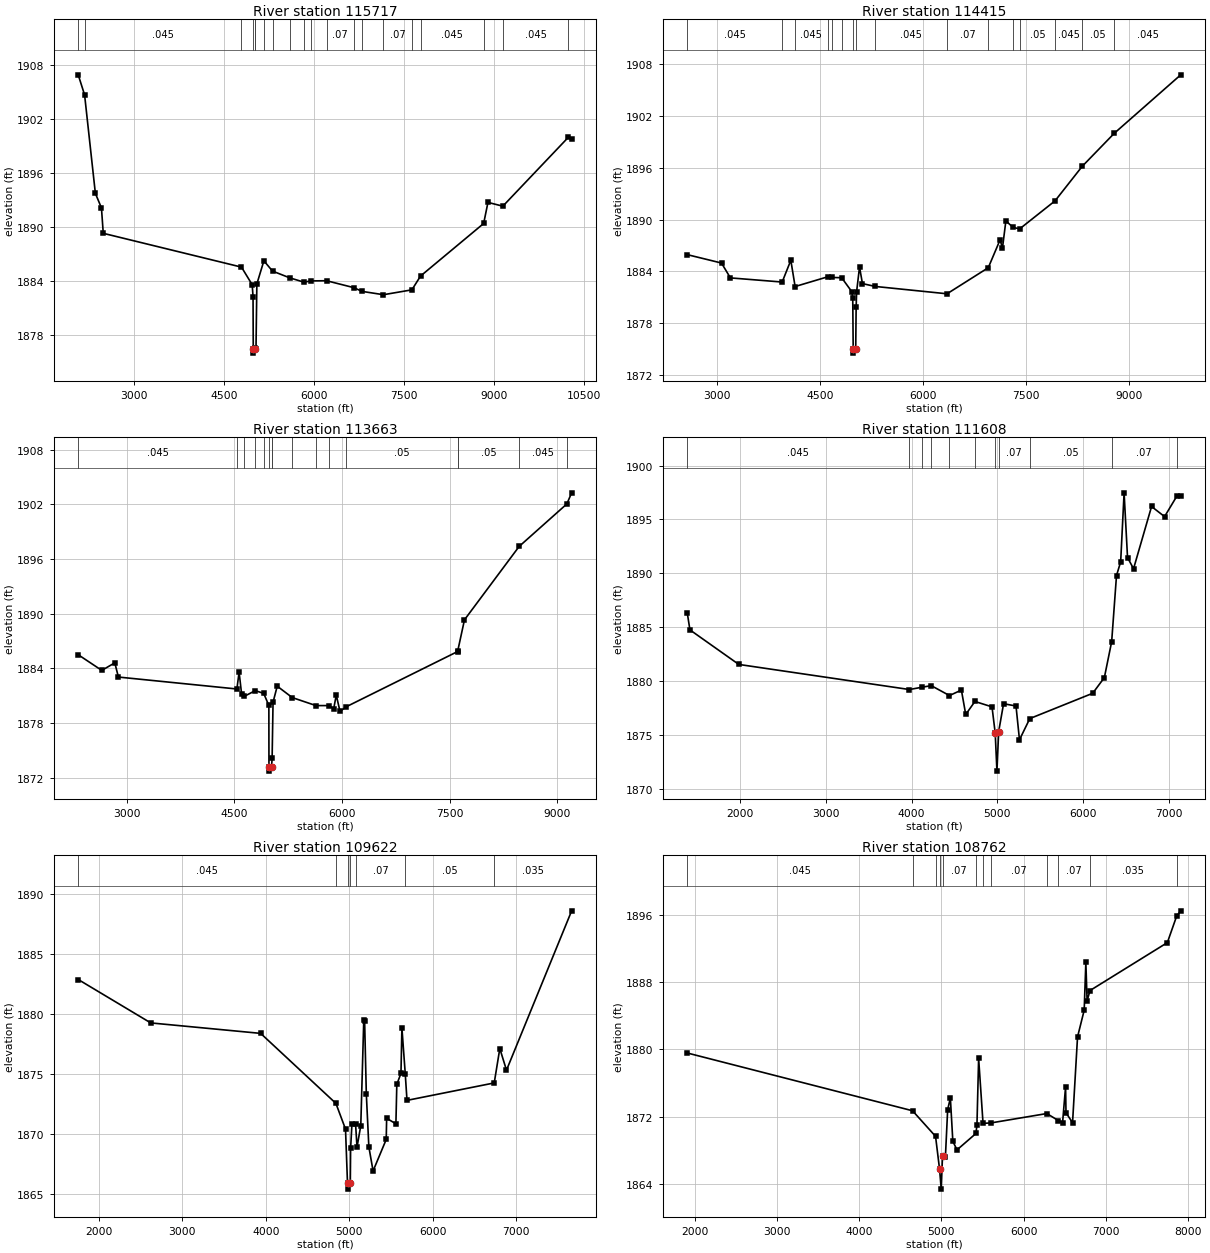
Type RM Length L Ch R = 1 ,115717  ,1302,1302,1302
BEGIN DESCRIPTION:
Noodle Creek 65.0
END DESCRIPTION:
XS GIS Cut Line= 3
      1470700.53      6872187.14      1473339.38      6871874.65
       1477470.1      6868143.12
#Sta/Elev= 30
  2064.3  1906.9  2170.5 1904.68  2350.2 1893.75  2451.5 1892.14  2481.7 1889.32
  4785.5 1885.57  4963.9 1883.62  4978.1  1882.3  4981.6 1876.53  4982.5 1876.03
  5018.4 1876.53    5019 1876.64  5027.4 1876.53  5041.6  1883.7  5158.7 1886.27
  5302.5 1885.13    5586 1884.39  5826.2  1883.9  5940.9 1884.04  6203.6 1884.06
  6659.8 1883.29  6793.2 1882.88  7151.7 1882.51  7625.4 1883.05  7769.8 1884.58
  8821.5 1890.41  8893.3 1892.75  9141.5 1892.33 10234.4 1899.98 10288.2 1899.74
#Mann= 20 ,-1 , 0
  2064.3    .035       0  2170.5    .045       0  4785.5     .16       0
  4981.6     .07       0  5018.4     .16       0    5019     .07       0
  5158.7    .045       0  5302.5    .035       0    5586    .035       0
  5826.2    .045       0  5940.9     .07       0  6203.6     .07       0
  6659.8    .045       0  6793.2     .07       0  7151.7     .07       0
  7625.4    .035       0  7769.8    .045       0  8821.5    .035       0
  9141.5    .045       0 10234.4     .07       0
Bank Sta=4981.6,5018.4
XS Rating Curve= 0 ,0
Exp/Cntr=0.3,0.1

Type RM Length L Ch R = 1 ,114415  ,752,752,752
BEGIN DESCRIPTION:
Noodle Creek 64.0
END DESCRIPTION:
XS GIS Cut Line= 3
      1472566.82      6872308.67      1474108.82      6872221.68
      1478108.18      6868222.32
#Sta/Elev= 30
  2560.9 1885.93  3059.9 1884.96  3189.7 1883.24  3945.3 1882.76  4071.5 1885.28
    4134 1882.24    4607 1883.36  4676.2 1883.29  4813.4 1883.26  4960.8 1881.65
    4975 1880.93  4981.6 1875.03  4982.5 1874.53  5018.4 1875.03  5024.5 1879.82
  5031.6 1881.65    5074  1884.5  5116.4 1882.58  5302.7 1882.25    6351  1881.4
  6952.8 1884.42  7124.6 1887.64    7160 1886.71  7209.4 1889.83  7316.5 1889.08
  7411.9 1888.92  7927.1 1892.16    8324 1896.16  8792.5 1899.99  9761.3 1906.75
#Mann= 16 ,-1 , 0
  2560.9    .045       0  3945.3     .16       0    4134    .045       0
    4607     .16       0  4676.2    .045       0  4813.4     .16       0
  4981.6    .045       0  5018.4     .16       0  5302.7    .045       0
    6351     .07       0  6952.8    .035       0  7316.5    .045       0
  7411.9     .05       0  7927.1    .045       0    8324     .05       0
  8792.5    .045       0
Bank Sta=4981.6,5018.4
XS Rating Curve= 0 ,0
Exp/Cntr=0.3,0.1

Type RM Length L Ch R = 1 ,113663  ,2055,2055,2055
BEGIN DESCRIPTION:
Noodle Creek 63.0
END DESCRIPTION:
XS GIS Cut Line= 3
      1472507.45      6872583.14      1474707.43      6872383.14
      1478707.42      6869983.15
#Sta/Elev= 30
  2324.4 1885.49  2652.8 1883.77    2834  1884.6  2884.3 1883.04  4534.8 1881.73
  4565.6 1883.58  4600.6 1881.17  4636.7 1880.92  4790.8 1881.55  4908.2 1881.25
  4980.2 1879.92  4981.6 1873.22  4982.5 1872.72  5018.4 1873.22  5025.7 1874.19
  5038.5 1880.28  5096.8 1882.04  5305.8 1880.79  5636.5 1879.91  5820.1 1879.91
  5883.4 1879.56    5919 1881.06  5971.4 1879.27  6060.6 1879.79  7609.8 1885.84
  7610.3 1885.87  7705.2 1889.32  8466.9 1897.37  9131.1 1902.03  9198.2 1903.25
#Mann= 16 ,-1 , 0
  2324.4    .045       0  4534.8     .16       0  4636.7    .045       0
  4790.8     .16       0  4908.2    .045       0  4981.6    .045       0
  5018.4    .045       0  5025.7     .07       0  5305.8    .045       0
  5636.5     .07       0  5820.1    .035       0  6060.6     .05       0
  7609.8    .035       0  7610.3     .05       0  8466.9    .045       0
  9131.1     .05       0
Bank Sta=4981.6,5018.4
XS Rating Curve= 0 ,0
Exp/Cntr=0.3,0.1

Type RM Length L Ch R = 1 ,111608  ,1986,1986,1986
BEGIN DESCRIPTION:
Mapping XS 11b640b8
END DESCRIPTION:
XS GIS Cut Line= 4
      1472384.48      6873037.84      1474164.04      6873029.16
      1477132.79      6872595.13      1478104.98      6872629.86
#Sta/Elev= 30
  1384.5 1886.29    1415 1884.74    1985 1881.53  3973.6  1879.2  4126.1 1879.42
  4228.4 1879.56  4441.1 1878.64  4579.9 1879.15  4630.5 1876.88  4737.4 1878.09
  4936.8 1877.59  4974.1 1875.16  4994.3 1871.62  5014.5  1875.3  5071.6 1877.88
  5216.6 1877.67  5257.1 1874.53  5377.3  1876.5  6110.5 1878.85  6246.7 1880.31
  6331.9 1883.65  6388.3 1889.79  6436.8 1891.06  6476.8 1897.47  6516.8 1891.46
  6586.9 1890.42    6797  1896.2  6948.6 1895.26  7092.3 1897.17  7137.2 1897.21
#Mann= 11 ,-1 , 0
  1384.5    .045       0  3973.6     .07       0  4126.1    .045       0
  4228.4     .07       0  4441.1    .035       0  4737.4     .07       0
  4974.1    .045       0  5014.5     .07       0  5377.3     .05       0
  6331.9     .07       0  7092.3    .035       0
Bank Sta=4974.1,5014.5
XS Rating Curve= 0 ,0
Exp/Cntr=0.3,0.1

Type RM Length L Ch R = 1 ,109622  ,860,860,860
BEGIN DESCRIPTION:
Mapping XS 255407c1
END DESCRIPTION:
XS GIS Cut Line= 3
      1472236.91      6873619.43      1476429.66      6874313.88
      1478096.28      6874339.92
#Sta/Elev= 30
  1751.3 1882.86  2621.1 1879.25  3938.8 1878.38  4841.1 1872.56  4956.4 1870.42
  4982.8 1865.43  4986.1 1865.93  5013.9 1865.93  5017.5 1868.81  5033.5 1870.83
  5077.4 1870.81  5094.3 1868.92  5139.5 1870.71  5175.4  1879.5  5185.5 1879.43
  5205.8 1873.36  5236.2 1868.95  5286.9 1866.94  5444.5 1869.56  5449.6 1871.32
  5560.6 1870.86  5571.6 1874.14  5621.4 1875.06  5632.6 1878.85    5673 1874.99
  5693.6 1872.81  6739.6 1874.26  6806.6 1877.12  6886.6 1875.32    7668 1888.57
#Mann= 7 ,-1 , 0
  1751.3    .045       0  4841.1    .035       0  4986.1    .035       0
  5013.9    .035       0  5077.4     .07       0    5673     .05       0
  6739.6    .035       0
Bank Sta=4986.1,5013.9
XS Rating Curve= 0 ,0
Exp/Cntr=0.3,0.1

Type RM Length L Ch R = 1 ,108762  ,616,616,616
BEGIN DESCRIPTION:
Mapping XS 90791676
END DESCRIPTION:
XS GIS Cut Line= 4
       1472497.4      6874348.61      1474702.23      6874791.31
      1477610.22       6875242.7      1478415.95      6875112.75
#Sta/Elev= 30
  1906.1 1879.56  4648.5 1872.69  4928.5 1869.65  4977.4 1865.75  4997.7 1863.37
  5013.2 1867.31  5048.3 1867.14  5076.1 1872.83    5109 1874.21  5139.1 1869.05
    5190 1868.04  5420.5 1869.99  5432.8 1871.04  5453.1 1878.92  5506.8 1871.19
  5606.6 1871.25  6283.3 1872.36  6424.3 1871.52  6475.2 1871.28  6511.8 1875.55
  6516.8 1872.46  6596.6 1871.27  6657.3 1881.47  6738.3 1884.65  6758.5 1890.34
  6773.7 1885.77  6809.2 1886.99  7750.9 1892.69    7864 1895.84  7913.9 1896.47
#Mann= 12 ,-1 , 0
  1906.1    .045       0  4648.5    .035       0  4928.5     .07       0
  4977.4    .045       0  5013.2     .07       0  5420.5     .05       0
  5506.8    .033       0  5606.6     .07       0  6283.3    .033       0
  6424.3     .07       0  6809.2    .035       0    7864     .07       0
Bank Sta=4977.4,5013.2
XS Rating Curve= 0 ,0
Exp/Cntr=0.3,0.1

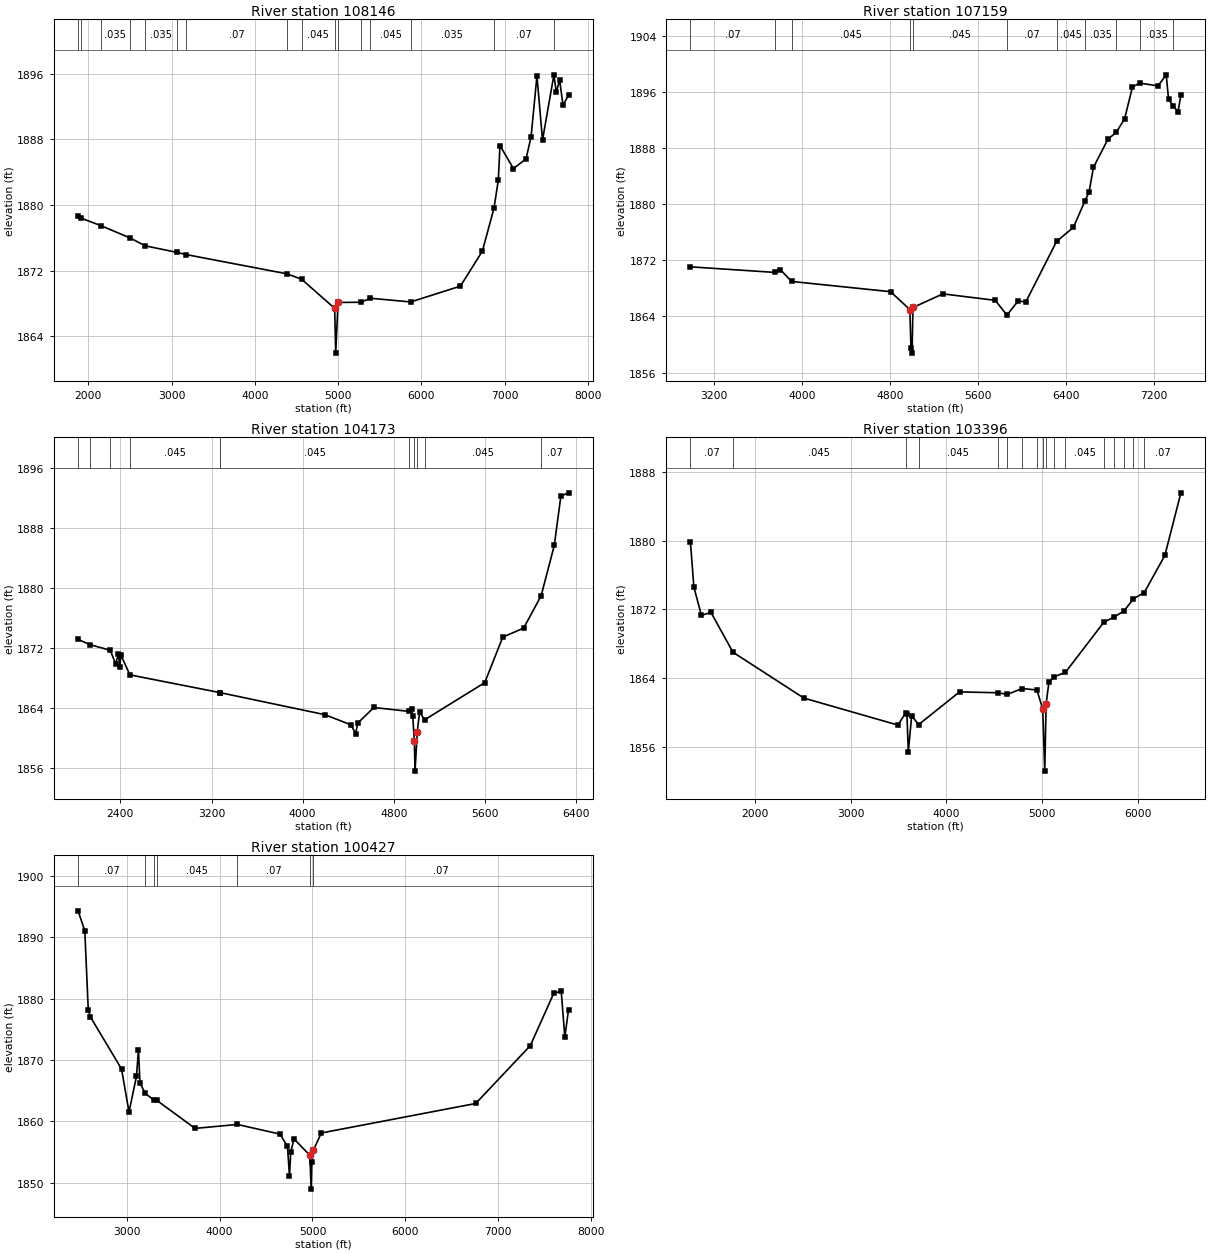
Type RM Length L Ch R = 1 ,108146  ,987,987,987
BEGIN DESCRIPTION:
Mapping XS b206c6d9
END DESCRIPTION:
XS GIS Cut Line= 4
      1472610.21      6874773.95      1474927.93      6875338.19
      1477297.72      6875728.81      1478390.74      6875581.34
#Sta/Elev= 30
  1877.9 1878.72  1917.7  1878.4  2149.9  1877.5  2500.7    1876  2684.5 1875.03
  3067.3 1874.23  3179.1 1873.96  4385.2 1871.62  4562.4 1870.96  4959.7 1867.41
    4972 1861.95  5000.2 1868.13    5273 1868.15  5388.7 1868.64  5872.9 1868.19
  6469.8 1870.12    6733 1874.38  6872.5  1879.6  6924.7 1883.03  6944.9 1887.26
  7106.3 1884.45  7257.7 1885.63  7318.2 1888.32  7388.9 1895.77  7455.5 1887.93
  7592.6 1895.88  7620.9 1893.77  7661.3 1895.25  7701.7 1892.19    7768 1893.39
#Mann= 16 ,-1 , 0
  1877.9    .035       0  1917.7    .045       0  2149.9    .035       0
  2500.7    .045       0  2684.5    .035       0  3067.3    .045       0
  3179.1     .07       0  4385.2    .035       0  4562.4    .045       0
  4959.7    .045       0  5000.2    .045       0    5273    .035       0
  5388.7    .045       0  5872.9    .035       0  6872.5     .07       0
  7592.6    .035       0
Bank Sta=4959.7,5000.2
XS Rating Curve= 0 ,0
Exp/Cntr=0.3,0.1

Type RM Length L Ch R = 1 ,107159  ,2986,2986,2986
BEGIN DESCRIPTION:
Mapping XS e23ef631
END DESCRIPTION:
XS GIS Cut Line= 4
      1474146.71      6876162.85      1475032.09       6876405.9
      1478122.37      6875945.83       1478478.3      6875737.48
#Sta/Elev= 30
  2987.9 1871.06  3751.8 1870.27  3805.4 1870.64  3906.7 1868.98  4806.1 1867.52
  4980.7 1864.98  4990.8 1859.57  5000.9 1858.77  5009.1 1865.27  5281.4 1867.21
  5756.7 1866.29  5862.6 1864.18  5964.7  1866.2  6034.1 1866.06  6313.7 1874.68
  6466.9 1876.69  6572.3 1880.48  6608.4  1881.7  6648.8 1885.24  6781.6 1889.28
  6855.4  1890.2  6931.9 1892.16  7002.7 1896.67    7069 1897.23  7235.1 1896.84
  7309.4 1898.41  7330.9 1894.92  7373.3 1893.97  7416.8 1893.13  7442.8 1895.55
#Mann= 11 ,-1 , 0
  2987.9     .07       0  3751.8    .035       0  3906.7    .045       0
  4980.7    .045       0  5009.1    .045       0  5862.6     .07       0
  6313.7    .045       0  6572.3    .035       0  6855.4     .07       0
    7069    .035       0  7373.3     .07       0
Bank Sta=4980.7,5009.1
XS Rating Curve= 0 ,0
Exp/Cntr=0.3,0.1

Type RM Length L Ch R = 1 ,104173  ,777,777,777
BEGIN DESCRIPTION:
Mapping XS 03866c57
END DESCRIPTION:
XS GIS Cut Line= 4
       1474450.5       6877074.3      1476125.84       6877655.9
      1477905.36      6877499.65      1478539.04      6877109.02
#Sta/Elev= 30
  2028.8 1873.11  2136.4  1872.4  2311.3 1871.67  2358.3 1869.86  2382.9 1871.13
  2394.8 1869.47  2404.1 1871.06  2483.4 1868.39  3272.4 1866.03  3272.5 1866.03
  4192.9 1863.09  4423.8 1861.73  4463.9 1860.56    4484 1861.96  4624.5 1864.04
  4934.7 1863.52  4955.8  1863.9  4965.8 1862.93  4979.8 1859.59  4985.9 1855.56
    5006 1860.84  5026.1 1863.48  5069.1 1862.39  5597.6 1867.35  5756.1 1873.42
  5939.5 1874.63  6092.5 1878.92    6208 1885.64  6265.9 1892.22    6333 1892.65
#Mann= 11 ,-1 , 0
  2028.8    .045       0  2136.4     .07       0  2311.3    .035       0
  2483.4    .045       0  3272.4     .07       0  3272.5    .045       0
  4934.7     .07       0  4979.8    .045       0    5006     .07       0
  5069.1    .045       0  6092.5     .07       0
Bank Sta=4979.8,5006
XS Rating Curve= 0 ,0
Exp/Cntr=0.3,0.1

Type RM Length L Ch R = 1 ,103396  ,2969,2969,2969
BEGIN DESCRIPTION:
Noodle Creek 57.0
END DESCRIPTION:
XS GIS Cut Line= 3
      1474997.41      6880181.91      1478200.49      6877690.62
      1479198.74      6877326.04
#Sta/Elev= 30
  1327.4 1879.83  1363.4  1874.6  1442.2 1871.32  1541.7 1871.66  1771.4 1867.03
  2511.8  1861.7  3494.5 1858.56  3573.5 1859.98  3587.7 1859.83  3602.2 1855.47
  3637.5 1859.66    3709 1858.61  4136.8 1862.42  4537.1 1862.32  4636.3 1862.13
  4790.4 1862.81  4944.4 1862.64  5005.7 1860.45  5026.5 1853.21    5041 1861.03
  5069.9 1863.54  5126.6 1864.18  5243.2  1864.7    5643 1870.51    5746 1871.11
  5852.5  1871.8  5952.8 1873.24  6065.5 1873.97  6280.5 1878.28    6448 1885.56
#Mann= 17 ,-1 , 0
  1327.4     .07       0  1771.4    .045       0  3573.5     .07       0
    3709    .045       0  4537.1     .07       0  4636.3    .045       0
  4790.4     .07       0  4944.4    .045       0  5005.7    .045       0
    5041     .07       0  5126.6     .07       0  5243.2    .045       0
    5643     .07       0    5746    .045       0  5852.5     .07       0
  5952.8    .045       0  6065.5     .07       0
Bank Sta=5005.7,5041
XS Rating Curve= 0 ,0
Exp/Cntr=0.3,0.1

Type RM Length L Ch R = 1 ,100427  ,823,823,823
BEGIN DESCRIPTION:
Noodle Creek 56.0
END DESCRIPTION:
XS GIS Cut Line= 3
      1475504.98      6880588.01      1477818.55      6879244.44
      1480136.25      6878055.21
#Sta/Elev= 30
  2476.5  1894.3    2549 1891.04  2586.2 1878.19  2607.7 1877.05  2944.7 1868.52
    3025 1861.51  3105.3 1867.31  3126.8 1871.68  3142.5 1866.28  3199.3 1864.54
  3295.8 1863.44  3323.8 1863.41  3736.1 1858.84  4191.8 1859.48  4650.6 1857.91
  4731.2 1855.91  4752.7 1851.09  4766.2 1854.99  4801.5 1857.13  4972.1 1854.45
  4985.9 1848.94  4993.6 1853.35    5009 1855.26  5095.4 1858.09  6757.5  1862.9
  7345.4 1872.33  7598.1 1880.86  7678.3  1881.2    7717 1873.71  7756.9 1878.19
#Mann= 7 ,-1 , 0
  2476.5     .07       0  3199.3    .045       0  3295.8     .07       0
  3323.8    .045       0  4191.8     .07       0  4972.1    .045       0
    5009     .07       0
Bank Sta=4972.1,5009
XS Rating Curve= 0 ,0
Exp/Cntr=0.3,0.1