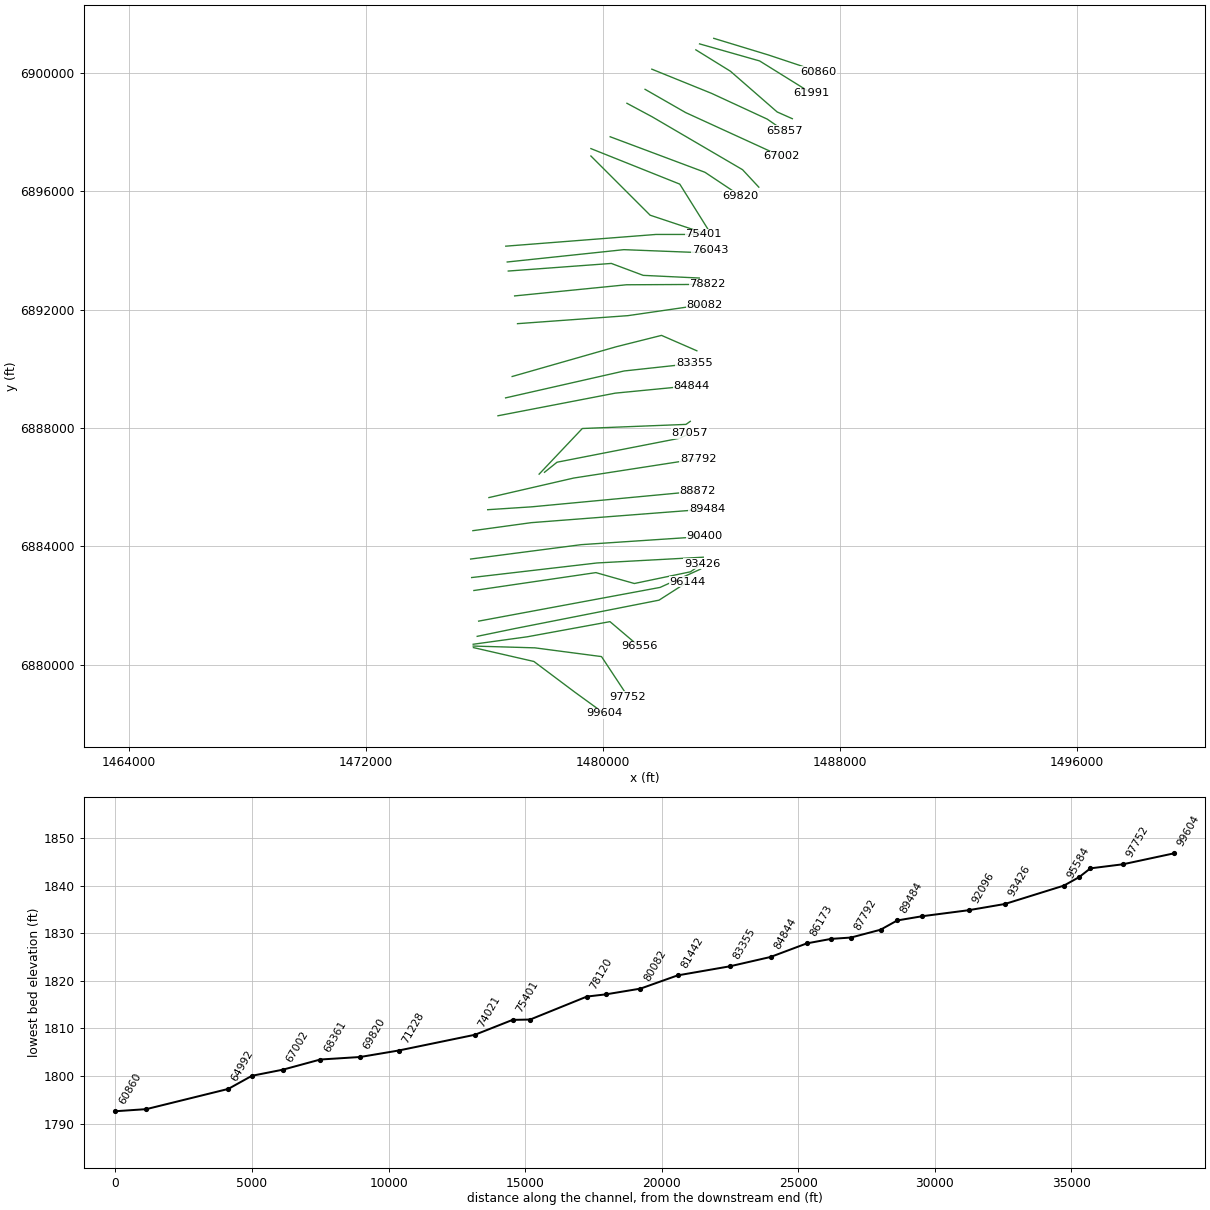
HEC-RAS study Noodle Creek.prj: Noodle Creek Base Level Engineering

--- Noodle Creek.g01 (geometry) --- (continued)

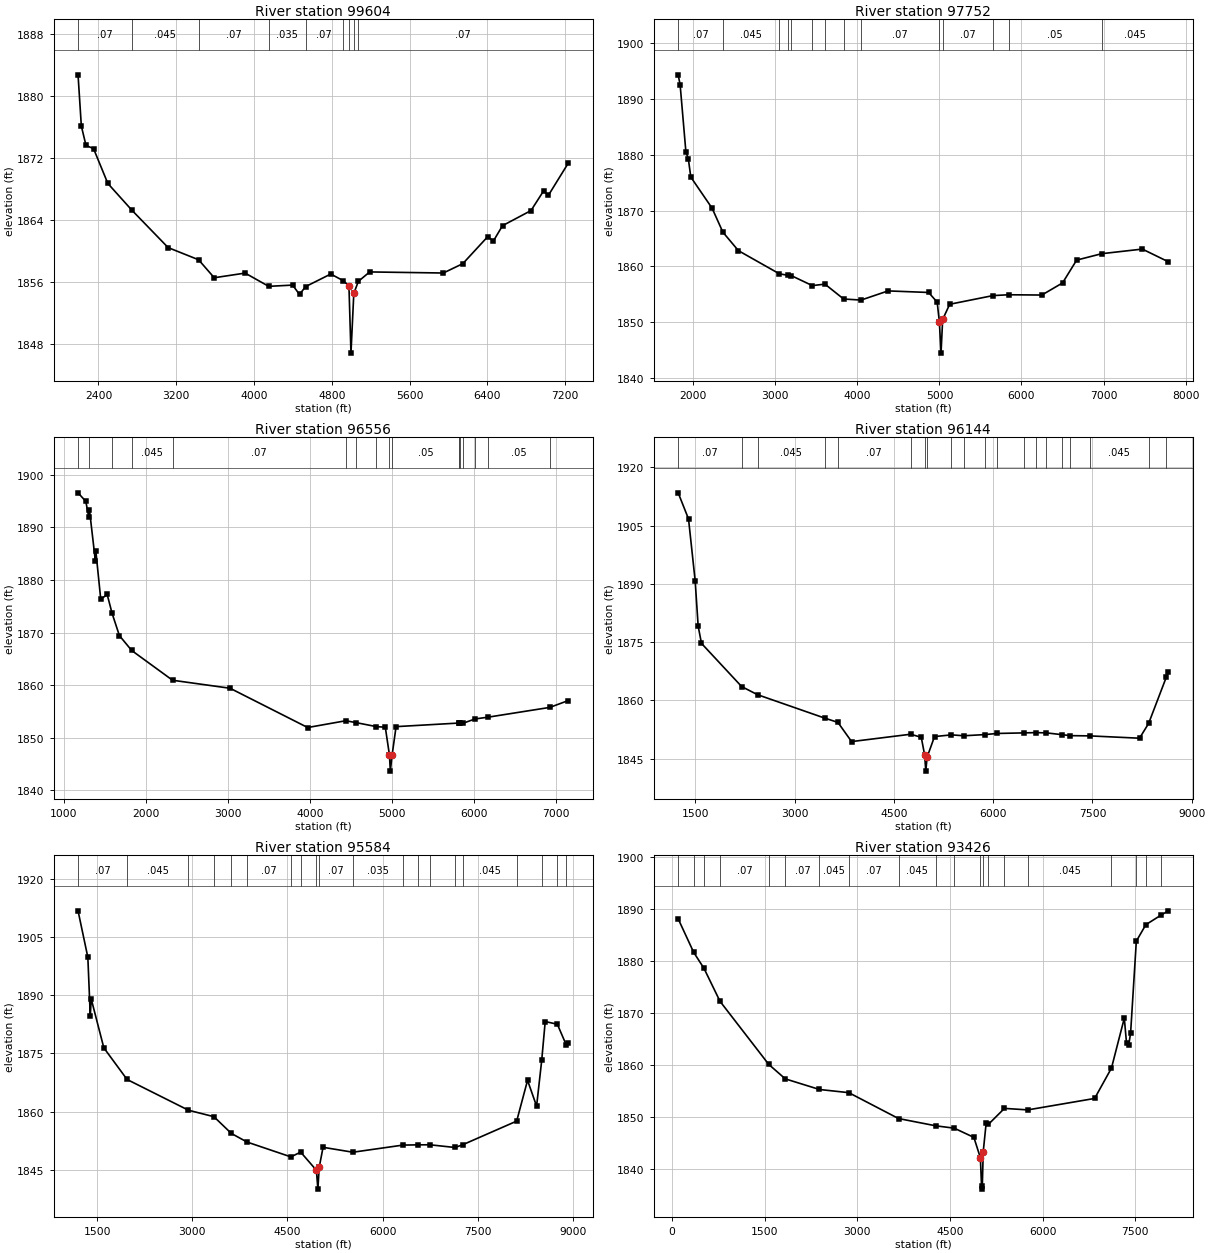
Type RM Length L Ch R = 1 ,99604   ,1852,1852,1852
BEGIN DESCRIPTION:
Mapping XS 41c1f2b8
END DESCRIPTION:
XS GIS Cut Line= 4
      1475639.77      6880581.23      1477679.66      6880112.49
      1479068.55      6879070.83      1480049.44      6878359.03
#Sta/Elev= 30
  2189.8  1882.7  2223.7 1876.09  2271.7 1873.58  2349.1 1873.18  2496.2 1868.68
  2744.2 1865.22  3116.6  1860.4  3429.8 1858.83  3590.6 1856.51  3908.7 1857.11
    4151  1855.4  4397.2 1855.56  4468.1 1854.35  4529.8 1855.36  4789.5 1856.99
  4915.8 1856.14  4976.4 1855.48  4997.2 1846.78  5026.4 1854.48  5073.2 1856.04
  5189.5 1857.26  5947.2 1857.12  6147.9 1858.33  6405.3 1861.83  6461.8 1861.24
  6556.1 1863.23  6849.1 1865.18  6978.3 1867.71  7027.7 1867.14  7230.9 1871.27
#Mann= 9 ,-1 , 0
  2189.8     .07       0  2744.2    .045       0  3429.8     .07       0
    4151    .035       0  4529.8     .07       0  4915.8    .035       0
  4976.4    .035       0  5026.4    .035       0  5073.2     .07       0
Bank Sta=4976.4,5026.4
XS Rating Curve= 0 ,0
Exp/Cntr=0.3,0.1

Type RM Length L Ch R = 1 ,97752   ,1196,1196,1196
BEGIN DESCRIPTION:
Mapping XS 1e4b5698
END DESCRIPTION:
XS GIS Cut Line= 4
      1475631.04      6880633.33      1477714.38      6880572.56
      1479962.65      6880277.43      1480856.75      6878923.25
#Sta/Elev= 30
  1814.6 1894.28  1838.6 1892.48  1908.6 1880.51  1938.6 1879.24  1968.6 1875.99
  2228.7 1870.41  2359.3 1866.14  2548.9 1862.83  3049.2 1858.68  3156.3 1858.42
  3193.9 1858.36  3449.8 1856.58  3604.3 1856.84  3831.6 1854.18  4044.5 1853.99
  4373.5 1855.63  4867.7 1855.35  4972.3 1853.62  4998.8 1850.09    5019  1844.5
  5039.1 1850.53  5124.8 1853.24  5651.7 1854.79  5842.1 1854.94    6248 1854.89
  6500.8 1857.06  6672.4 1861.14  6979.4 1862.29  7473.1 1863.11  7789.1 1860.85
#Mann= 14 ,-1 , 0
  1814.6     .07       0  2359.3    .045       0  3049.2     .07       0
  3156.3    .045       0  3193.9     .07       0  3449.8    .035       0
  3604.3     .07       0  3831.6    .035       0  4044.5     .07       0
  4998.8    .045       0  5039.1     .07       0  5651.7    .035       0
  5842.1     .05       0  6979.4    .045       0
Bank Sta=4998.8,5039.1
XS Rating Curve= 0 ,0
Exp/Cntr=0.3,0.1

Type RM Length L Ch R = 1 ,96556   ,412,412,412
BEGIN DESCRIPTION:
Mapping XS 7cb992e5
END DESCRIPTION:
XS GIS Cut Line= 4
      1475631.06      6880694.09      1477453.97      6880945.83
      1480249.11      6881457.98      1481230.02      6880624.63
#Sta/Elev= 30
  1176.3 1896.56  1271.1 1894.93  1307.4  1891.9  1315.5 1893.31  1387.4 1883.61
  1392.5 1885.57  1452.8 1876.31  1531.2 1877.23  1591.4 1873.62    1680 1869.41
  1829.8 1866.58  2327.6 1860.92  3027.7  1859.4  3973.2 1851.93  4436.9 1853.22
  4557.9 1852.88  4811.2  1852.1  4918.7 1851.99  4969.5 1846.67  4979.7 1843.64
  5001.7  1846.7  5049.8  1852.1  5812.5 1852.78  5819.6 1852.74  5830.3 1852.72
  5864.6 1852.74  6011.1 1853.56  6170.3  1853.9  6923.3 1855.76  7145.3 1857.05
#Mann= 17 ,-1 , 0
  1176.3    .035       0  1307.4     .07       0  1591.4    .035       0
  1829.8    .045       0  2327.6     .07       0  4436.9     .05       0
  4557.9     .07       0  4811.2     .05       0  4969.5     .05       0
  5001.7     .05       0  5812.5     .07       0  5819.6     .05       0
  5830.3     .07       0  5864.6     .05       0  6011.1    .035       0
  6170.3     .05       0  6923.3    .045       0
Bank Sta=4969.5,5001.7
XS Rating Curve= 0 ,0
Exp/Cntr=0.3,0.1

Type RM Length L Ch R = 1 ,96144   ,560,560,560
BEGIN DESCRIPTION:
Mapping XS 7a8c2ffd
END DESCRIPTION:
XS GIS Cut Line= 4
      1475766.43      6880961.45      1477009.52       6881218.4
      1481905.36      6882183.68      1482870.34      6882801.54
#Sta/Elev= 30
  1239.8 1913.41  1396.2 1906.69  1496.6 1890.76  1541.7  1879.1    1592 1874.67
    2199 1863.56  2438.6 1861.47  3452.9 1855.45  3653.6 1854.34  3860.2  1849.4
  4751.5 1851.29    4913 1850.51  4964.4 1845.92  4981.3  1841.8  5001.7 1845.41
  5113.3 1850.69    5368 1851.13  5557.9  1850.9  5872.7  1851.2  6058.5 1851.49
  6463.5 1851.64    6653 1851.71  6805.2 1851.64  7034.3 1851.19  7165.9 1850.93
  7456.5 1850.87  8211.3 1850.27  8348.8 1854.08  8616.8 1866.02  8645.1 1867.34
#Mann= 20 ,-1 , 0
  1239.8     .07       0    2199    .045       0  2438.6    .045       0
  3452.9    .035       0  3653.6     .07       0  4751.5    .035       0
  4964.4     .05       0  5001.7     .05       0    5368     .07       0
  5557.9    .035       0  5872.7     .07       0  6058.5    .035       0
  6463.5    .035       0    6653    .045       0  6805.2     .07       0
  7034.3     .07       0  7165.9    .035       0  7456.5    .045       0
  8348.8    .035       0  8616.8    .035       0
Bank Sta=4964.4,5001.7
XS Rating Curve= 0 ,0
Exp/Cntr=0.3,0.1

Type RM Length L Ch R = 1 ,95584   ,2158,2158,2158
BEGIN DESCRIPTION:
Mapping XS 6fef1006
END DESCRIPTION:
XS GIS Cut Line= 3
      1475815.05      6881475.34      1481940.08      6882614.23
      1483308.13      6883232.29
#Sta/Elev= 30
  1196.3 1911.73  1350.8 1899.76  1389.5  1884.6  1403.5 1889.06  1603.1 1876.42
  1969.6 1868.27  2938.8 1860.34  3339.5 1858.68  3615.8 1854.35  3863.1 1852.14
  4554.2 1848.32  4708.2 1849.55  4956.3 1844.88    4980 1840.01  5000.4 1845.59
  5061.4 1850.79  5532.2 1849.52  6323.1 1851.36  6559.4 1851.42  6745.5 1851.44
    7144 1850.74  7267.9 1851.47  8116.1 1857.54  8287.6 1868.05  8430.3 1861.39
  8510.8 1873.16  8566.2  1883.2  8757.8  1882.5  8901.3 1877.05  8927.5  1877.6
#Mann= 20 ,-1 , 0
  1196.3     .07       0  1969.6    .045       0  2938.8     .07       0
  3339.5     .07       0  3615.8    .045       0  3863.1     .07       0
  4554.2    .035       0  4708.2     .07       0  4956.3    .045       0
  5000.4     .07       0  5532.2    .035       0  6323.1     .07       0
  6559.4    .045       0  6745.5     .07       0    7144    .035       0
  7267.9    .045       0  8116.1    .035       0  8510.8    .035       0
  8757.8    .035       0  8901.3     .07       0
Bank Sta=4956.3,5000.4
XS Rating Curve= 0 ,0
Exp/Cntr=0.3,0.1

Type RM Length L Ch R = 1 ,93426   ,1330,1330,1330
BEGIN DESCRIPTION:
Mapping XS 7be599da
END DESCRIPTION:
XS GIS Cut Line= 5
      1475655.32      6882510.06      1479773.41      6883114.23
      1481072.02      6882746.18      1482967.86      6883142.01
      1483363.67      6883419.77
#Sta/Elev= 30
   102.3 1888.07   353.5 1881.63   519.6 1878.57   779.3 1872.23  1568.3 1860.11
  1836.1 1857.33  2389.5 1855.29  2863.8 1854.68  3668.6 1849.71  4272.8 1848.31
    4570 1847.86  4888.5 1846.09  4993.7 1842.18  5014.5 1836.15  5024.9 1836.74
  5039.8 1843.34  5087.2 1848.82  5122.5 1848.58  5383.2 1851.66  5760.7 1851.37
  6843.2 1853.57  7115.5  1859.4  7323.3 1868.99  7359.6 1864.17  7394.8 1863.84
  7425.4 1866.15    7518 1883.79  7672.3 1886.95  7913.2 1888.75  8034.5 1889.61
#Mann= 20 ,-1 , 0
   102.3     .16       0   353.5    .035       0   519.6     .07       0
   779.3     .07       0  1568.3    .045       0  1836.1     .07       0
  2389.5    .045       0  2863.8     .07       0  3668.6    .045       0
  4272.8     .07       0    4570     .07       0  4993.7    .045       0
  5039.8     .07       0  5122.5    .035       0  5383.2     .07       0
  5760.7    .045       0  7115.5    .035       0    7518     .07       0
  7672.3    .035       0  7913.2     .07       0
Bank Sta=4993.7,5039.8
XS Rating Curve= 0 ,0
Exp/Cntr=0.3,0.1

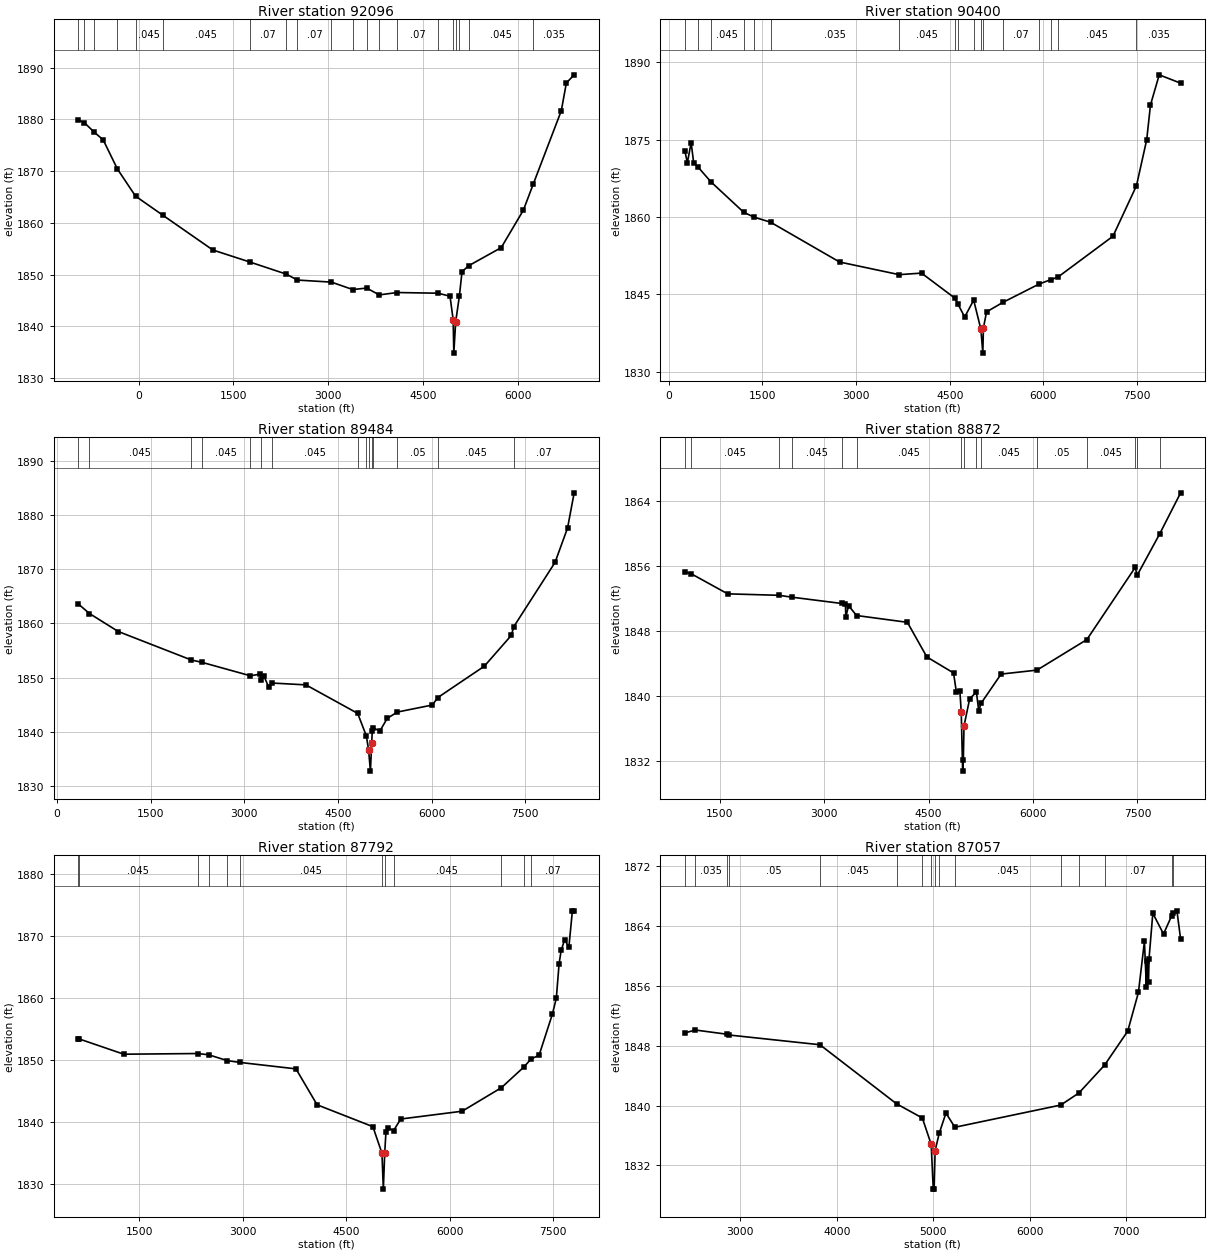
Type RM Length L Ch R = 1 ,92096   ,1696,1696,1696
BEGIN DESCRIPTION:
Mapping XS 4933e8a2
END DESCRIPTION:
XS GIS Cut Line= 3
      1475578.99      6882947.57      1479815.08      6883440.62
      1483398.42      6883635.07
#Sta/Elev= 30
  -956.8 1879.86  -863.1 1879.39  -704.3 1877.53  -563.5 1876.06  -337.5 1870.41
   -51.1 1865.18   381.4 1861.49  1173.5 1854.77  1758.8 1852.45  2338.4  1850.1
  2512.6 1848.96  3052.6 1848.56  3388.9 1847.13  3610.8 1847.41  3809.7 1846.09
  4090.9 1846.55  4741.5 1846.42  4930.2 1845.84  4980.3 1841.26  4990.3 1834.84
  5020.3 1840.94  5078.2 1845.82  5120.5 1850.59  5227.7 1851.74  5741.4 1855.23
  6091.9 1862.46  6246.9 1867.45  6692.8 1881.68  6772.9 1887.05  6896.5 1888.62
#Mann= 20 ,-1 , 0
  -956.8     .07       0  -863.1    .035       0  -704.3     .07       0
  -337.5    .045       0   -51.1    .045       0   381.4    .045       0
  1758.8     .07       0  2338.4    .035       0  2512.6     .07       0
  3052.6    .045       0  3388.9     .07       0  3610.8    .045       0
  3809.7    .045       0  4090.9     .07       0  4741.5    .045       0
  4980.3    .045       0  5020.3    .045       0  5078.2     .07       0
  5227.7    .045       0  6246.9    .035       0
Bank Sta=4980.3,5020.3
XS Rating Curve= 0 ,0
Exp/Cntr=0.3,0.1

Type RM Length L Ch R = 1 ,90400   ,916,916,916
BEGIN DESCRIPTION:
Mapping XS 7fb7149d
END DESCRIPTION:
XS GIS Cut Line= 3
      1475544.28      6883572.57      1479280.36      6884058.68
      1483447.04      6884336.45
#Sta/Elev= 30
   255.8 1872.85   296.9 1870.55   357.4 1874.41   397.7 1870.56   470.5 1869.65
   675.4 1866.81  1198.8 1860.92  1363.3 1859.98  1629.9 1858.99  2735.8 1851.26
  3690.5 1848.81  4048.1 1849.11  4582.6 1844.25  4633.1 1843.06  4739.6 1840.59
  4883.9 1843.86  4999.2 1838.22  5030.2 1833.58  5040.3 1838.51  5090.4 1841.59
  5355.4 1843.45  5937.2 1847.02  6122.6 1847.85  6232.8 1848.33  7114.9 1856.26
  7491.6 1866.06  7656.1    1875  7716.2 1881.74  7856.5 1887.59  8199.3 1885.97
#Mann= 17 ,-1 , 0
   255.8     .07       0   470.5    .035       0   675.4    .045       0
  1198.8    .035       0  1363.3    .045       0  1629.9    .035       0
  3690.5    .045       0  4582.6     .07       0  4633.1    .045       0
  4883.9     .07       0  4999.2    .045       0  5040.3     .07       0
  5355.4     .07       0  5937.2    .045       0  6122.6     .07       0
  6232.8    .045       0  7491.6    .035       0
Bank Sta=4999.2,5040.3
XS Rating Curve= 0 ,0
Exp/Cntr=0.3,0.1

Type RM Length L Ch R = 1 ,89484   ,612,612,612
BEGIN DESCRIPTION:
Mapping XS e3c6dd79
END DESCRIPTION:
XS GIS Cut Line= 3
      1475620.65       6884530.9      1477592.86      6884801.73
      1483530.17      6885260.05
#Sta/Elev= 30
   338.9  1863.6   516.9 1861.84   979.2 1858.51  2145.6 1853.26  2326.2 1852.79
  3097.6 1850.32  3244.5 1850.62  3269.4  1849.6  3314.7 1850.21  3387.7  1848.3
  3448.2 1848.98  3986.7 1848.64  4815.4 1843.37  4953.9 1839.22  4989.7 1836.67
  5019.7 1832.69  5039.8 1837.87  5049.8 1840.19  5068.8 1840.68  5170.2 1840.09
  5290.5 1842.47  5453.3 1843.62  6012.7 1844.92  6098.9 1846.29  6845.2  1852.1
  7276.4 1857.78    7318 1859.42  7978.5  1871.3  8179.1 1877.67  8284.6 1884.16
#Mann= 15 ,-1 , 0
   338.9     .07       0   516.9    .045       0  2145.6    .035       0
  2326.2    .045       0  3097.6     .07       0  3269.4    .035       0
  3448.2    .045       0  4815.4     .07       0  4953.9     .05       0
  4989.7     .05       0  5039.8     .05       0  5068.8    .045       0
  5453.3     .05       0  6098.9    .045       0    7318     .07       0
Bank Sta=4989.7,5039.8
XS Rating Curve= 0 ,0
Exp/Cntr=0.3,0.1

Type RM Length L Ch R = 1 ,88872   ,1080,1080,1080
BEGIN DESCRIPTION:
Mapping XS 8d60f0c7
END DESCRIPTION:
XS GIS Cut Line= 3
      1476120.61      6885239.23      1477606.74      6885336.45
      1483210.43      6885864.19
#Sta/Elev= 30
  1001.4  1855.3  1088.1 1855.09  1617.1 1852.59  2352.8 1852.41  2537.5 1852.18
  3255.9  1851.4  3307.3 1851.34  3312.6 1849.75  3352.8 1851.14  3466.4 1849.92
  4196.5 1849.08  4476.5 1844.81  4859.4 1842.84  4899.6  1840.5  4949.8 1840.67
  4969.9 1838.01    4990 1830.74    5000 1832.09  5009.3  1836.3  5090.4 1839.64
  5187.6  1840.5    5221 1838.17  5253.7 1839.09  5542.1  1842.7  6057.1 1843.19
    6773 1846.95  7467.7 1855.85  7494.3 1854.86  7819.8    1860  8119.2 1865.04
#Mann= 15 ,-1 , 0
  1001.4     .07       0  1088.1    .045       0  2352.8    .035       0
  2537.5    .045       0  3255.9    .035       0  3466.4    .045       0
  4969.9    .045       0  5009.3     .07       0  5187.6     .07       0
  5253.7    .045       0  6057.1     .05       0    6773    .045       0
  7467.7     .07       0  7494.3    .045       0  7819.8     .07       0
Bank Sta=4969.9,5009.3
XS Rating Curve= 0 ,0
Exp/Cntr=0.3,0.1

Type RM Length L Ch R = 1 ,87792   ,735,735,735
BEGIN DESCRIPTION:
Mapping XS f7c32c50
END DESCRIPTION:
XS GIS Cut Line= 3
      1476162.26      6885648.94      1479023.41      6886308.68
      1483230.87      6886961.32
#Sta/Elev= 30
     613 1853.43   617.4 1853.42  1272.6 1850.92  2345.2 1851.03    2503 1850.83
  2775.4 1849.88  2956.9 1849.59  3770.8 1848.55  4077.1 1842.74  4886.9  1839.2
  5018.2 1834.91  5038.4  1829.1  5058.7    1835  5075.9 1838.28  5099.1 1839.02
  5186.2 1838.56  5291.4 1840.44  6181.9  1841.7  6750.4  1845.5  7075.7 1848.83
  7182.7 1850.16  7298.1 1850.75  7492.1 1857.44  7548.1 1859.98  7588.5 1865.55
  7618.1 1867.71  7669.5 1869.45  7730.2 1868.22  7780.8 1874.05    7807 1874.11
#Mann= 12 ,-1 , 0
     613     .07       0   617.4    .045       0  2345.2     .07       0
    2503    .045       0  2775.4    .035       0  2956.9    .045       0
  5018.2    .045       0  5058.7     .07       0  5186.2    .045       0
  6750.4     .07       0  7075.7    .035       0  7182.7     .07       0
Bank Sta=5018.2,5058.7
XS Rating Curve= 0 ,0
Exp/Cntr=0.3,0.1

Type RM Length L Ch R = 1 ,87057   ,884,884,884
BEGIN DESCRIPTION:
Mapping XS d3924a55
END DESCRIPTION:
XS GIS Cut Line= 4
      1478037.33      6886503.14      1478460.91       6886843.4
      1482613.69       6887655.9      1482940.06      6887822.56
#Sta/Elev= 30
  2424.8 1849.71  2534.3  1850.1  2860.3 1849.54  2878.8 1849.44    3826 1848.13
  4620.2 1840.23  4887.6 1838.33  4979.6 1834.81  5001.1 1828.81  5010.2 1828.85
  5020.4 1833.97    5063 1836.28  5132.5 1838.98  5225.7 1837.09  6323.1 1840.06
  6510.9 1841.67  6776.8 1845.39  7017.6 1849.95  7128.5 1855.13  7190.8 1861.96
    7211 1855.87  7216.6 1859.35  7233.2 1856.56  7238.8 1859.67  7277.7 1865.73
  7388.8 1862.95  7473.7  1865.4  7491.9  1865.7  7527.7 1866.05  7566.1 1862.27
#Mann= 16 ,-1 , 0
  2424.8     .07       0  2534.3    .035       0  2860.3    .045       0
  2878.8     .05       0    3826    .045       0  4620.2    .035       0
  4887.6    .045       0  4979.6    .045       0  5020.4    .045       0
    5063     .07       0  5225.7    .045       0  6323.1    .035       0
  6510.9    .045       0  6776.8     .07       0  7473.7    .035       0
  7491.9     .07       0
Bank Sta=4979.6,5020.4
XS Rating Curve= 0 ,0
Exp/Cntr=0.3,0.1

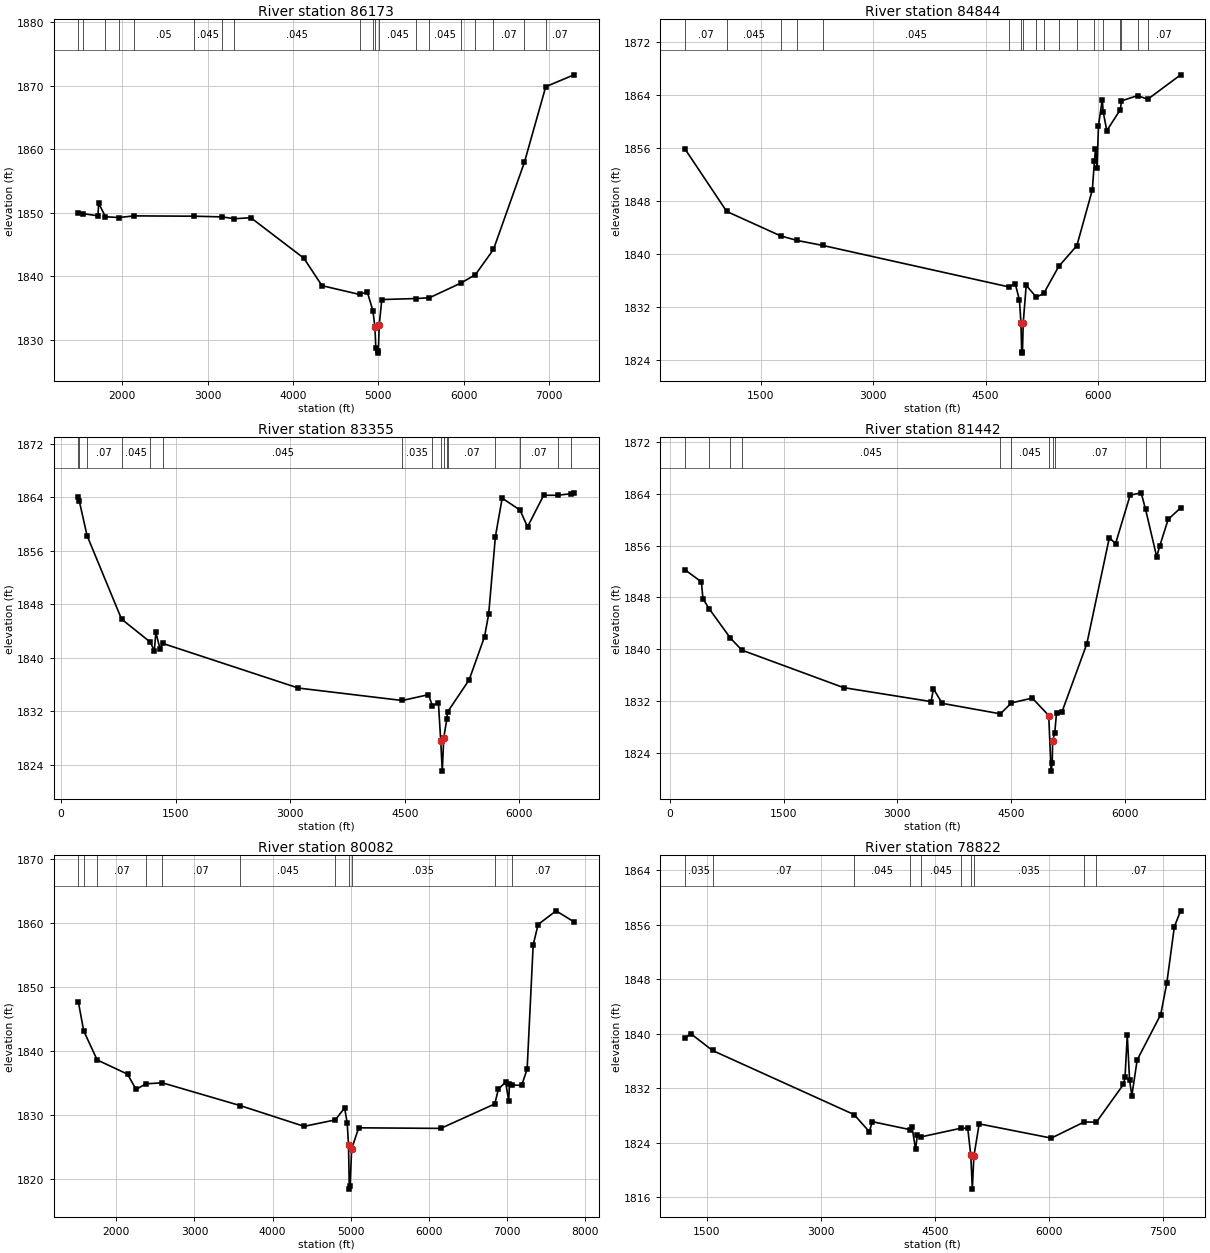
Type RM Length L Ch R = 1 ,86173   ,1329,1329,1329
BEGIN DESCRIPTION:
Mapping XS 9bf2404f
END DESCRIPTION:
XS GIS Cut Line= 4
      1477856.74      6886440.62      1479315.08      6887982.29
      1482815.08      6888121.18      1482960.42      6888224.99
#Sta/Elev= 30
  1487.4 1849.92  1541.7 1849.84  1717.8  1849.5  1724.8 1851.48  1805.5 1849.35
  1966.5 1849.23  2136.4 1849.49  2846.6 1849.44  3170.8 1849.33  3314.9 1849.04
  3507.3  1849.2  4128.4 1842.82    4340  1838.5  4780.3 1837.11  4870.5 1837.52
    4936 1834.56  4960.5 1831.95  4970.5 1828.62  4990.5 1827.87  5000.6 1828.26
  5010.6  1832.3  5040.6 1836.31  5443.1 1836.47  5597.9 1836.59  5967.8 1838.91
  6137.2 1840.24  6347.9  1844.2  6710.5 1857.93  6960.2 1869.84  7290.9 1871.71
#Mann= 19 ,-1 , 0
  1487.4     .07       0  1541.7    .035       0  1805.5    .045       0
  1966.5    .035       0  2136.4     .05       0  2846.6    .045       0
  3170.8     .05       0  3314.9    .045       0  4780.3    .035       0
    4936    .045       0  4960.5    .045       0  5010.6    .045       0
  5443.1    .035       0  5597.9    .045       0  5967.8    .035       0
  6137.2    .045       0  6347.9     .07       0  6710.5    .035       0
  6960.2     .07       0
Bank Sta=4960.5,5010.6
XS Rating Curve= 0 ,0
Exp/Cntr=0.3,0.1

Type RM Length L Ch R = 1 ,84844   ,1489,1489,1489
BEGIN DESCRIPTION:
Noodle Creek 45.0
END DESCRIPTION:
XS GIS Cut Line= 3
      1476467.84      6888412.84      1480426.19      6889176.73
      1482995.67      6889426.73
#Sta/Elev= 30
     488 1855.89  1044.5 1846.44  1762.9 1842.75  1983.3 1842.05  2325.5  1841.3
  4815.3 1835.01  4893.9 1835.54  4950.2 1833.04  4970.3 1829.64  4980.4 1825.14
  4990.4 1825.01  5001.3 1829.64  5040.6 1835.26  5175.4 1833.48  5274.6 1834.03
  5474.3 1838.12  5716.4 1841.26  5923.2 1849.71  5950.4    1854    5965 1855.88
  5985.1 1852.99  6005.2 1859.43  6055.4 1863.33  6068.3 1861.49  6115.7 1858.65
  6297.3 1861.85  6311.7 1863.16  6527.4 1863.96  6661.2  1863.4    7101  1867.1
#Mann= 18 ,-1 , 0
     488     .07       0  1044.5    .045       0  1762.9    .035       0
  1983.3     .05       0  2325.5    .045       0  4815.3    .035       0
  4970.3    .045       0  5001.3    .035       0  5175.4    .045       0
  5274.6     .07       0  5474.3    .045       0  5716.4     .07       0
  5950.4    .035       0  6068.3     .07       0  6297.3    .035       0
  6311.7     .07       0  6527.4    .035       0  6661.2     .07       0
Bank Sta=4970.3,5001.3
XS Rating Curve= 0 ,0
Exp/Cntr=0.3,0.1

Type RM Length L Ch R = 1 ,83355   ,1913,1913,1913
BEGIN DESCRIPTION:
Noodle Creek 44.0
END DESCRIPTION:
XS GIS Cut Line= 3
      1476724.79      6889017.01      1480731.74      6889926.73
      1483099.81      6890183.68
#Sta/Elev= 30
   224.5 1864.06   236.3 1863.48   339.1 1858.26   790.4 1845.78    1168 1842.33
  1219.4 1841.03  1239.9  1843.8  1293.4 1841.36  1330.8 1842.14  3106.2 1835.47
    4467 1833.61  4809.5 1834.48  4860.8 1832.84  4940.2 1833.25  4970.4 1827.58
  4990.5 1823.05  5010.6 1828.07  5049.9 1830.81  5059.2 1831.88  5342.6  1836.7
  5543.7 1843.14  5597.9  1846.5  5686.2 1858.12  5775.1 1863.86  6008.6 1862.08
    6107 1859.57  6318.3 1864.29  6501.6  1864.3  6674.9 1864.52  6715.4 1864.66
#Mann= 16 ,-1 , 0
   224.5     .07       0   236.3    .035       0   339.1     .07       0
   790.4    .045       0    1168    .035       0  1330.8    .045       0
    4467    .035       0  4860.8     .07       0  4970.4    .045       0
  5010.6     .07       0  5049.9    .045       0  5059.2     .07       0
  5686.2    .035       0  6008.6     .07       0  6501.6    .035       0
  6674.9    .045       0
Bank Sta=4970.4,5010.6
XS Rating Curve= 0 ,0
Exp/Cntr=0.3,0.1

Type RM Length L Ch R = 1 ,81442   ,1360,1360,1360
BEGIN DESCRIPTION:
Noodle Creek 43.0
END DESCRIPTION:
XS GIS Cut Line= 4
      1476946.97      6889739.22      1480467.86      6890746.18
      1481988.69      6891128.12      1483181.61      6890607.95
#Sta/Elev= 30
   201.4 1852.27   417.8  1850.4   438.6 1847.78   520.1 1846.25   801.1 1841.69
   952.6 1839.84  2291.6 1834.05  3444.4 1831.89  3475.6 1833.87    3590 1831.62
  4357.6    1830  4503.6 1831.69  4778.1 1832.43  4994.7 1829.74  5025.6 1821.14
    5041 1822.41  5046.2 1825.85  5073.6 1826.99  5097.8 1830.19  5169.9 1830.32
  5496.4 1840.81  5793.8 1857.25  5874.9  1856.3  6067.7 1863.81    6213 1864.17
  6270.7 1861.62  6417.4 1854.29  6457.3 1855.94  6568.8 1860.07  6732.9 1861.84
#Mann= 11 ,-1 , 0
   201.4     .07       0   520.1    .045       0   801.1    .035       0
   952.6    .045       0  4357.6    .035       0  4503.6    .045       0
  4994.7    .045       0  5046.2    .045       0  5073.6     .07       0
  6270.7    .035       0  6457.3     .07       0
Bank Sta=4994.7,5046.2
XS Rating Curve= 0 ,0
Exp/Cntr=0.3,0.1

Type RM Length L Ch R = 1 ,80082   ,1260,1260,1260
BEGIN DESCRIPTION:
Noodle Creek 42.0
END DESCRIPTION:
XS GIS Cut Line= 3
      1477127.59      6891523.95      1480856.74      6891794.79
      1483431.53      6892169.55
#Sta/Elev= 30
  1513.9 1847.67  1582.6 1843.12  1754.8 1838.57    2143 1836.34  2253.3 1833.95
  2376.4 1834.83    2588 1834.99  3586.3 1831.42  4401.9 1828.18  4801.8 1829.19
  4920.3 1831.07  4953.7 1828.69  4970.4 1825.26  4980.4 1818.36  4990.4 1818.81
  5010.5 1824.67  5100.7 1827.95  6150.5 1827.86  6841.9 1831.69  6888.2 1834.04
  6980.2 1835.09  7019.6 1832.17  7029.7 1834.85  7059.5 1834.65  7185.4 1834.58
  7255.5 1837.15  7332.8 1856.56  7395.6 1859.75  7625.9 1861.89  7854.8 1860.16
#Mann= 11 ,-1 , 0
  1513.9     .07       0  1582.6    .035       0  1754.8     .07       0
  2376.4    .045       0    2588     .07       0  3586.3    .045       0
  4801.8    .035       0  4970.4    .045       0  5010.5    .035       0
  6841.9    .035       0  7059.5     .07       0
Bank Sta=4970.4,5010.5
XS Rating Curve= 0 ,0
Exp/Cntr=0.3,0.1

Type RM Length L Ch R = 1 ,78822   ,702,702,702
BEGIN DESCRIPTION:
Noodle Creek 41.0
END DESCRIPTION:
XS GIS Cut Line= 3
      1477030.34      6892461.45        1480805.        6892838.
      1483537.28      6892850.34
#Sta/Elev= 30
  1211.4 1839.29  1286.4 1839.99    1574 1837.51  3439.6 1828.09    3638 1825.59
  3678.2 1827.06  4174.6 1825.89  4200.8 1826.28  4247.6 1822.98  4271.2 1825.13
  4316.3 1824.82  4841.1 1826.09  4934.4 1826.09  4974.6  1822.1  4994.7 1817.16
  5014.8 1821.97  5084.8 1826.74  6034.8 1824.65  6467.3 1827.02    6628 1826.99
  6984.8 1832.54  7004.8 1833.59  7034.8 1839.78  7064.8 1833.18  7094.8 1830.87
  7164.8 1836.12  7474.8 1842.79  7554.8 1847.39  7654.8 1855.69  7737.1 1858.01
#Mann= 10 ,-1 , 0
  1211.4    .035       0    1574     .07       0  3439.6    .045       0
  4174.6     .07       0  4316.3    .045       0  4841.1    .035       0
  4974.6    .045       0  5014.8    .035       0  6467.3    .035       0
    6628     .07       0
Bank Sta=4974.6,5014.8
XS Rating Curve= 0 ,0
Exp/Cntr=0.3,0.1

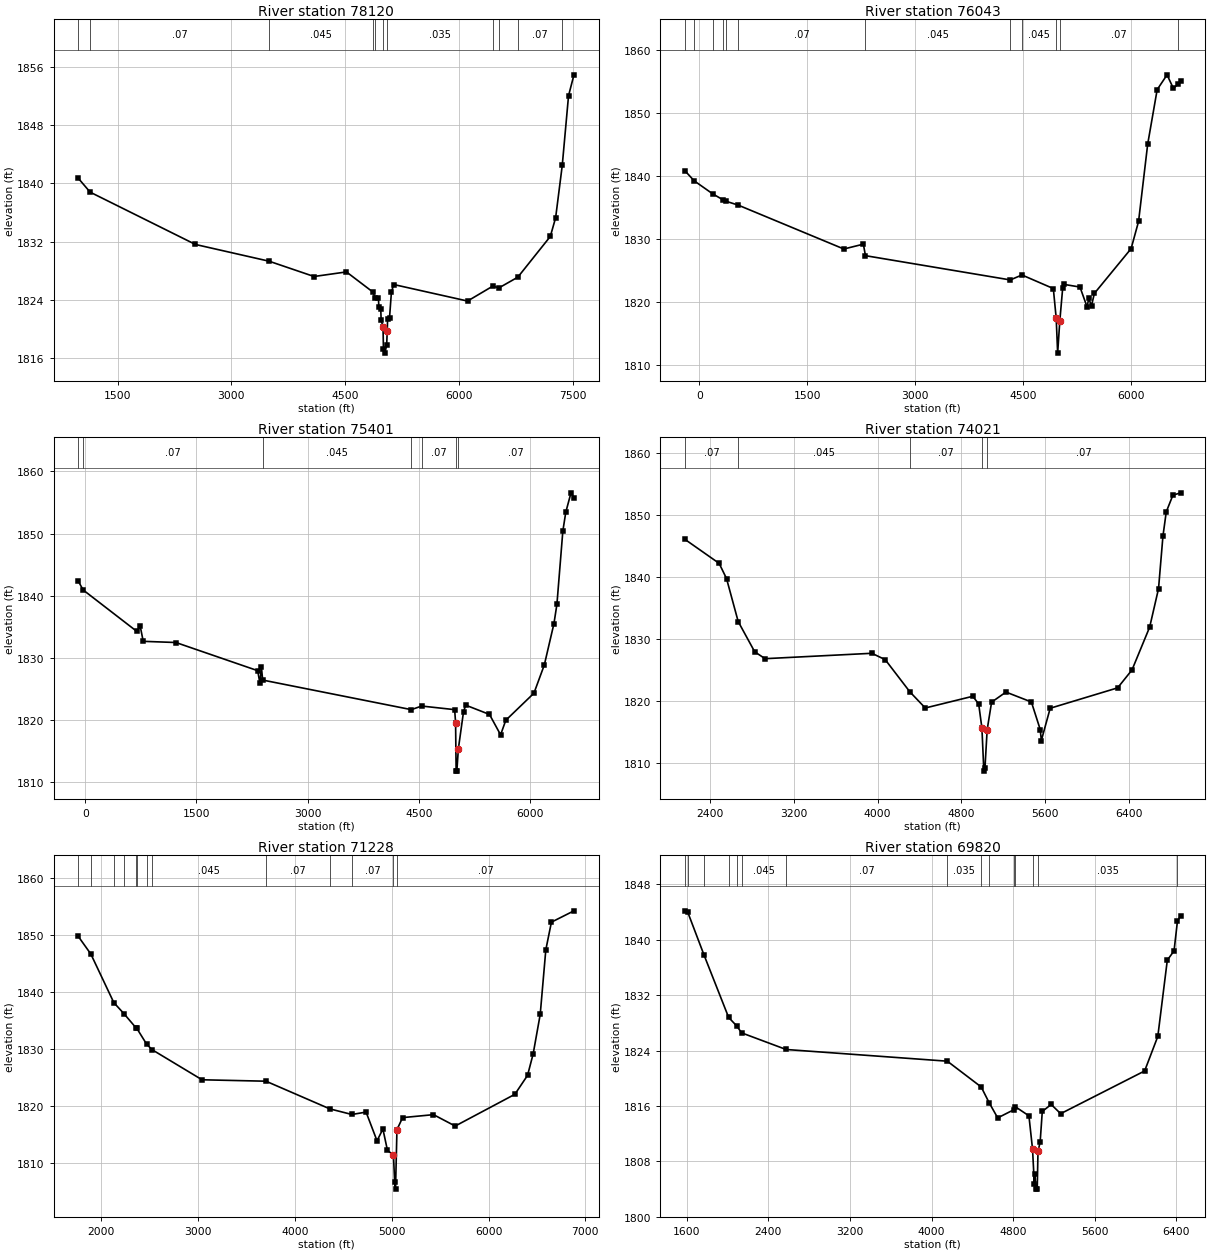
Type RM Length L Ch R = 1 ,78120   ,2077,2077,2077
BEGIN DESCRIPTION:
Mapping XS d7804fa5
END DESCRIPTION:
XS GIS Cut Line= 4
      1476815.04      6893301.73      1480294.24      6893558.68
      1481370.63       6893155.9      1483266.43      6893065.62
#Sta/Elev= 30
   981.9 1840.69  1137.9 1838.79  2526.1 1831.61  3497.8 1829.31  4090.3 1827.21
  4517.4 1827.84  4864.8 1825.09  4895.1  1824.3  4939.6 1824.27  4944.9 1822.99
  4969.9 1822.81  4975.2 1821.21  4999.9 1820.32  5005.5 1817.22  5025.1 1816.69
    5048 1817.81  5055.4 1819.71  5060.7 1821.42  5085.7 1821.55  5110.6 1825.06
  5140.9 1826.11  6114.8 1823.84  6444.4 1825.87  6532.2 1825.67  6777.7 1827.12
    7206 1832.71  7276.1 1835.28  7363.4 1842.46  7446.3 1852.03  7517.8  1854.9
#Mann= 11 ,-1 , 0
   981.9    .035       0  1137.9     .07       0  3497.8    .045       0
  4864.8     .07       0  4895.1    .035       0  4999.9    .045       0
  5055.4    .035       0  6444.4     .07       0  6532.2    .045       0
  6777.7     .07       0  7363.4    .035       0
Bank Sta=4999.9,5055.4
XS Rating Curve= 0 ,0
Exp/Cntr=0.3,0.1

Type RM Length L Ch R = 1 ,76043   ,642,642,642
BEGIN DESCRIPTION:
Mapping XS e2d2d4af
END DESCRIPTION:
XS GIS Cut Line= 4
      1476780.35      6893607.29      1480717.86      6894023.95
      1483217.86      6893926.73      1483634.52      6894010.06
#Sta/Elev= 30
  -199.3 1840.85   -72.4 1839.27   185.5 1837.19     335  1836.2   371.9 1836.01
   539.9  1835.4  2007.6 1828.42  2279.1 1829.19  2307.7 1827.36  4320.6  1823.5
  4482.1 1824.29  4918.2 1822.13  4958.2  1817.4  4978.3 1811.86  5008.3 1816.99
  5048.3 1822.22  5072.4 1822.78  5288.5 1822.37  5388.6 1819.16  5408.6 1820.58
  5448.6 1819.41  5488.6 1821.36    5999 1828.48  6102.4  1832.8  6229.2 1845.09
  6361.1 1853.77  6498.4 1856.12  6585.5 1853.97  6654.6 1854.66    6687 1855.11
#Mann= 12 ,-1 , 0
  -199.3    .035       0   -72.4     .07       0   185.5     .16       0
     335     .07       0   371.9     .16       0   539.9     .07       0
  2307.7    .045       0  4320.6    .035       0  4482.1    .045       0
  4958.2    .045       0  5008.3     .07       0  6654.6    .035       0
Bank Sta=4958.2,5008.3
XS Rating Curve= 0 ,0
Exp/Cntr=0.3,0.1

Type RM Length L Ch R = 1 ,75401   ,1380,1380,1380
BEGIN DESCRIPTION:
Noodle Creek 40.0
END DESCRIPTION:
XS GIS Cut Line= 3
      1476731.79      6894142.01        1481805.        6894538.
      1483404.96        6894538.
#Sta/Elev= 30
   -93.3 1842.34   -27.9 1840.93   693.9 1834.29   742.4 1835.07   782.6 1832.67
  1223.9 1832.48  2327.3 1827.95  2356.7 1825.94  2377.4  1828.5  2394.6 1826.44
  4400.7 1821.68  4539.5 1822.26  4985.3 1821.68  4997.8  1819.6  5005.3 1811.79
  5015.3 1811.87  5035.3 1815.38  5105.3 1821.37  5135.3  1822.4  5455.3 1820.91
  5605.3 1817.63  5675.3 1819.97  6055.3 1824.33  6195.3 1828.87  6325.3 1835.53
  6365.3 1838.62  6445.3 1850.41  6485.3 1853.46  6555.3 1856.56  6595.3 1855.78
#Mann= 7 ,-1 , 0
   -93.3    .035       0   -27.9     .07       0  2394.6    .045       0
  4400.7    .035       0  4539.5     .07       0  4997.8    .045       0
  5035.3     .07       0
Bank Sta=4997.8,5035.3
XS Rating Curve= 0 ,0
Exp/Cntr=0.3,0.1

Type RM Length L Ch R = 1 ,74021   ,2793,2793,2793
BEGIN DESCRIPTION:
Noodle Creek 39.0
END DESCRIPTION:
XS GIS Cut Line= 3
        1479605.        6897188.        1481605.        6895188.
      1483405.01        6894588.
#Sta/Elev= 30
  2164.2 1846.06  2489.5  1842.2  2560.2 1839.74  2671.4  1832.8  2828.9 1827.92
  2927.9 1826.81  3946.1 1827.68  4073.4 1826.65  4308.7 1821.45  4455.2 1818.85
  4907.8 1820.74  4964.3 1819.51  4995.3  1815.6  5013.7 1808.66  5024.2 1809.16
  5045.3 1815.35  5087.5 1819.79  5224.5 1821.42    5467 1819.82  5551.3 1815.37
  5561.8  1813.6  5646.2 1818.81  6289.2  1822.1  6426.2 1824.99  6594.8 1831.91
  6679.2 1838.11  6721.3 1846.59    6753 1850.51  6816.2  1853.2    6890 1853.58
#Mann= 5 ,-1 , 0
  2164.2     .07       0  2671.4    .045       0  4308.7     .07       0
  4995.3    .045       0  5045.3     .07       0
Bank Sta=4995.3,5045.3
XS Rating Curve= 0 ,0
Exp/Cntr=0.3,0.1

Type RM Length L Ch R = 1 ,71228   ,1408,1408,1408
BEGIN DESCRIPTION:
Noodle Creek 38.0
END DESCRIPTION:
XS GIS Cut Line= 3
      1479604.95      6897438.02        1482605.        6896238.
      1483604.98      6894638.04
#Sta/Elev= 30
  1764.2 1849.69  1893.4 1846.61  2130.8 1838.08    2235 1836.15  2361.6 1833.62
  2368.7 1833.55  2469.5 1830.79    2526 1829.82  3041.9 1824.54  3701.9 1824.29
  4361.7 1819.43  4588.9 1818.45  4735.5 1818.87  4848.6 1813.83  4909.2  1815.9
  4956.3 1812.15  5018.3 1811.33  5030.7 1806.56  5039.6 1805.35  5054.3 1815.78
  5112.7  1817.9  5431.7 1818.42  5655.7 1816.42  6271.9 1821.99  6402.8 1825.31
  6460.6 1829.07  6533.7 1836.01  6591.5 1847.35  6649.2  1852.2  6882.1 1854.19
#Mann= 13 ,-1 , 0
  1764.2     .07       0  1893.4    .035       0  2130.8     .07       0
    2235    .045       0  2361.6     .07       0  2368.7    .045       0
  2469.5     .07       0    2526    .045       0  3701.9     .07       0
  4361.7    .035       0  4588.9     .07       0  5018.3    .045       0
  5054.3     .07       0
Bank Sta=5018.3,5054.3
XS Rating Curve= 0 ,0
Exp/Cntr=0.3,0.1

Type RM Length L Ch R = 1 ,69820   ,1459,1459,1459
BEGIN DESCRIPTION:
Noodle Creek 37.0
END DESCRIPTION:
XS GIS Cut Line= 3
        1480255.        6897838.        1483455.        6896638.
      1484654.98      6895838.01
#Sta/Elev= 30
  1582.9 1844.19  1608.7 1844.04  1769.9 1837.79  2010.8 1828.79  2090.1 1827.56
  2138.4 1826.56  2574.4 1824.16  4155.2 1822.47    4487 1818.75  4566.6 1816.43
    4649 1814.28  4805.8 1815.45  4822.2 1815.89  4955.1 1814.58  4990.7 1809.75
    5008  1804.8    5014 1806.23    5023 1803.99  5036.6 1804.03  5044.1 1809.46
  5065.1 1810.77  5086.1 1815.21  5173.3 1816.22  5266.4 1814.89  6089.7 1821.06
  6218.9 1826.05    6312 1837.06  6378.1 1838.41  6411.1 1842.66  6442.7 1843.51
#Mann= 15 ,-1 , 0
  1582.9     .07       0  1608.7    .035       0  1769.9     .07       0
  2010.8    .045       0  2090.1     .07       0  2138.4    .045       0
  2574.4     .07       0  4155.2    .035       0    4487     .07       0
  4566.6    .035       0  4805.8     .07       0  4822.2    .035       0
  4990.7    .035       0  5044.1    .035       0  6411.1    .035       0
Bank Sta=4990.7,5044.1
XS Rating Curve= 0 ,0
Exp/Cntr=0.3,0.1

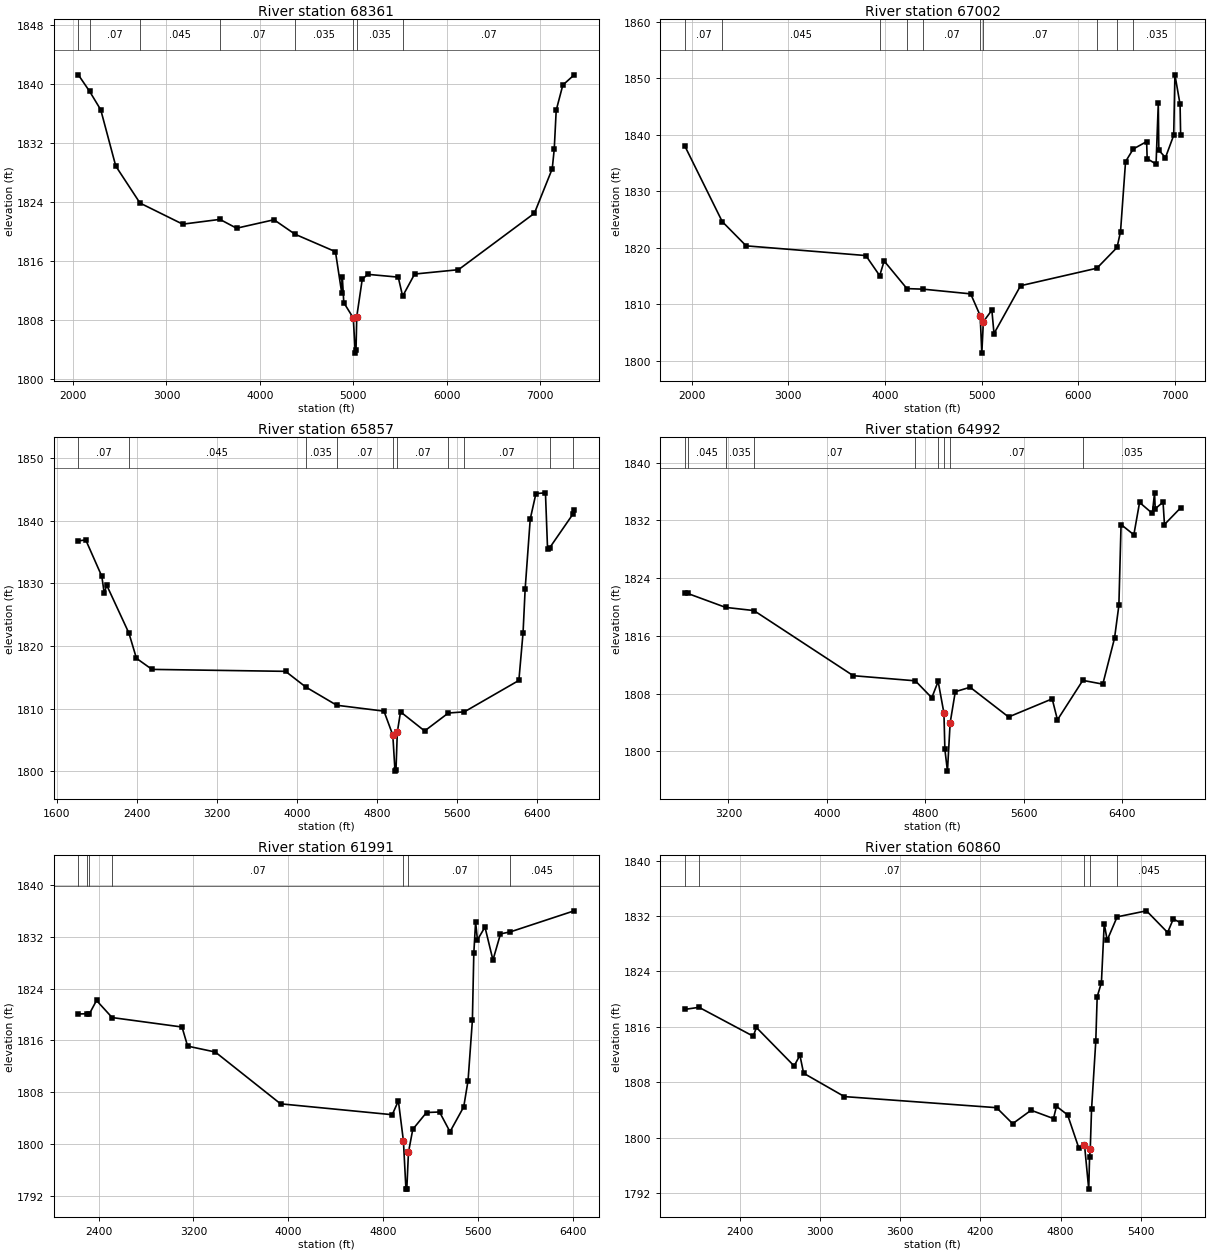
Type RM Length L Ch R = 1 ,68361   ,1359,1359,1359
BEGIN DESCRIPTION:
Mapping XS b55feacf
END DESCRIPTION:
XS GIS Cut Line= 4
      1480821.99      6898968.42      1481676.19      6898510.06
       1484724.8      6896725.34      1485273.44      6896135.04
#Sta/Elev= 30
  2056.5 1841.29  2177.9 1839.03  2296.6 1836.53  2457.1 1828.89  2716.6 1823.86
  3173.9 1820.99  3572.3 1821.64  3750.6 1820.44  4151.3 1821.59  4376.6 1819.62
    4809 1817.25  4876.7  1811.6  4882.5 1813.84  4898.2 1810.32  4999.8 1808.24
  5021.3 1803.46  5029.2 1803.92    5037 1808.41  5095.7 1813.49  5154.3 1814.17
  5481.1 1813.79  5528.2  1811.2  5656.7 1814.21  6125.9  1814.8  6938.7 1822.47
  7129.7 1828.52  7151.2 1831.19  7172.2 1836.47  7243.1  1839.9  7364.4 1841.28
#Mann= 8 ,-1 , 0
  2056.5    .045       0  2177.9     .07       0  2716.6    .045       0
  3572.3     .07       0  4376.6    .035       0  4999.8    .035       0
    5037    .035       0  5528.2     .07       0
Bank Sta=4999.8,5037
XS Rating Curve= 0 ,0
Exp/Cntr=0.3,0.1

Type RM Length L Ch R = 1 ,67002   ,1145,1145,1145
BEGIN DESCRIPTION:
Mapping XS 2160877c
END DESCRIPTION:
XS GIS Cut Line= 3
      1481433.17       6899440.6      1482801.19       6898655.9
      1486030.15      6897176.82
#Sta/Elev= 30
  1930.5 1838.01  2317.8 1824.62  2564.9 1820.33    3803 1818.61  3946.5 1815.05
  3992.5 1817.65  4228.1 1812.76  4397.1 1812.66  4887.7 1811.83  4985.7 1807.99
  5002.8 1801.34  5018.7  1806.9  5106.7 1808.95  5128.8  1804.8  5403.7 1813.27
    6193 1816.37  6401.6 1820.04  6437.6 1822.86  6489.6 1835.24  6569.1 1837.47
  6707.6 1838.78  6713.1 1835.77  6805.1 1834.79  6828.2 1845.57  6833.7 1837.24
  6902.7 1835.96  6987.5  1839.9  7000.2  1850.6  7053.5 1845.37  7059.2 1839.95
#Mann= 10 ,-1 , 0
  1930.5     .07       0  2317.8    .045       0  3946.5     .07       0
  4228.1    .035       0  4397.1     .07       0  4985.7    .045       0
  5018.7     .07       0    6193    .035       0  6401.6     .07       0
  6569.1    .035       0
Bank Sta=4985.7,5018.7
XS Rating Curve= 0 ,0
Exp/Cntr=0.3,0.1

Type RM Length L Ch R = 1 ,65857   ,865,865,865
BEGIN DESCRIPTION:
Mapping XS 68211296
END DESCRIPTION:
XS GIS Cut Line= 4
      1481662.32      6900121.17      1483683.13      6899301.73
      1485558.13      6898433.68      1486139.24      6898032.43
#Sta/Elev= 30
  1814.1 1836.77  1888.1 1836.93  2048.9 1831.11    2073 1828.38  2097.1 1829.72
  2319.5 1822.05  2394.5 1818.04  2549.9 1816.27  3884.2 1815.96  4085.1 1813.47
  4395.5 1810.55  4867.1 1809.61  4955.5 1805.79  4977.5 1800.04  4987.2  1800.2
  5000.6 1806.26  5032.6  1809.5  5273.3 1806.45  5510.2 1809.31  5670.4  1809.5
  6214.8 1814.51  6256.7 1822.14  6277.6  1829.1  6328.3 1840.26  6385.2 1844.32
  6480.4 1844.44  6501.4 1835.47  6523.9  1835.7  6753.3 1841.01  6767.1 1841.69
#Mann= 10 ,-1 , 0
  1814.1     .07       0  2319.5    .045       0  4085.1    .035       0
  4395.5     .07       0  4955.5    .045       0  5000.6     .07       0
  5510.2    .035       0  5670.4     .07       0  6523.9    .035       0
  6753.3     .07       0
Bank Sta=4955.5,5000.6
XS Rating Curve= 0 ,0
Exp/Cntr=0.3,0.1

Type RM Length L Ch R = 1 ,64992   ,3001,3001,3001
BEGIN DESCRIPTION:
Mapping XS aca6c212
END DESCRIPTION:
XS GIS Cut Line= 4
      1483148.38      6900773.97      1484315.08      6900051.73
      1485891.47      6898676.73      1486405.33      6898447.58
#Sta/Elev= 30
  2845.6 1821.98  2867.9  1821.9  3177.3 1819.96  3406.9 1819.52  4213.6  1810.5
  4717.7 1809.79  4851.4 1807.44    4903 1809.71  4950.1 1805.31  4957.7 1800.29
  4978.6 1797.28  5000.4 1803.95  5042.2 1808.28  5162.7  1808.9  5475.1 1804.78
  5829.2 1807.29  5871.9 1804.38  6077.7 1809.85  6240.2 1809.33  6335.3 1815.68
  6370.7 1820.23  6388.5 1831.44  6492.3 1830.02  6538.8  1834.5  6642.6 1832.98
  6660.4 1835.83  6665.9 1833.62  6729.5 1834.54    6741 1831.44  6872.2 1833.75
#Mann= 9 ,-1 , 0
  2845.6    .035       0  2867.9    .045       0  3177.3    .035       0
  3406.9     .07       0  4717.7    .035       0    4903     .07       0
  4950.1    .045       0  5000.4     .07       0  6077.7    .035       0
Bank Sta=4950.1,5000.4
XS Rating Curve= 0 ,0
Exp/Cntr=0.3,0.1

Type RM Length L Ch R = 1 ,61991   ,1131,1131,1131
BEGIN DESCRIPTION:
Mapping XS 54ba9cee
END DESCRIPTION:
XS GIS Cut Line= 3
      1483273.41      6900975.34      1485301.19      6900398.95
      1487064.05      6899302.37
#Sta/Elev= 30
  2228.6 1820.07  2302.5 1820.11  2322.2 1820.11  2382.2 1822.16  2513.7 1819.52
  3103.5 1818.06  3150.9 1815.11  3384.2  1814.2  3935.2  1806.2  4877.6 1804.52
  4929.5 1806.66    4972 1800.47  4993.2 1793.03  5000.7 1793.09  5014.5 1798.71
  5051.1 1802.27  5166.8 1804.86  5276.6 1804.94  5365.1 1801.89  5480.8 1805.73
  5517.4 1809.78    5554 1819.09    5566 1829.44  5581.1 1834.29  5596.5 1831.52
  5660.2 1833.49  5727.5  1828.4  5791.2 1832.44  5874.3 1832.75  6412.8    1836
#Mann= 7 ,-1 , 0
  2228.6    .035       0  2302.5    .045       0  2322.2    .035       0
  2513.7     .07       0    4972    .045       0  5014.5     .07       0
  5874.3    .045       0
Bank Sta=4972,5014.5
XS Rating Curve= 0 ,0
Exp/Cntr=0.3,0.1

Type RM Length L Ch R = 1 ,60860   ,951,951,951
BEGIN DESCRIPTION:
Mapping XS fd23dfcb
END DESCRIPTION:
XS GIS Cut Line= 3
      1483752.58      6901162.84       1485599.8      6900600.34
      1487287.25      6900037.86
#Sta/Elev= 30
  1987.7 1818.52  2094.1 1818.82  2499.7 1814.65  2523.4 1815.91  2805.6 1810.36
    2849  1811.9  2876.6 1809.31  3181.9 1805.94  4320.4 1804.34  4440.7 1802.03
  4578.6 1803.97  4746.3 1802.77  4768.4 1804.54  4851.8  1803.3  4936.1  1798.5
  4978.2 1798.97  5009.9 1792.59  5016.1 1797.16  5021.4 1798.42  5030.9 1804.08
  5062.6 1813.92  5073.1 1820.35  5104.7 1822.37  5125.8 1830.91  5147.9  1828.5
  5222.3 1831.87    5442 1832.74  5600.2 1829.61  5642.3 1831.56  5697.4 1831.02
#Mann= 5 ,-1 , 0
  1987.7    .035       0  2094.1     .07       0  4978.2    .045       0
  5021.4     .16       0  5222.3    .045       0
Bank Sta=4978.2,5021.4
XS Rating Curve= 0 ,0
Exp/Cntr=0.3,0.1