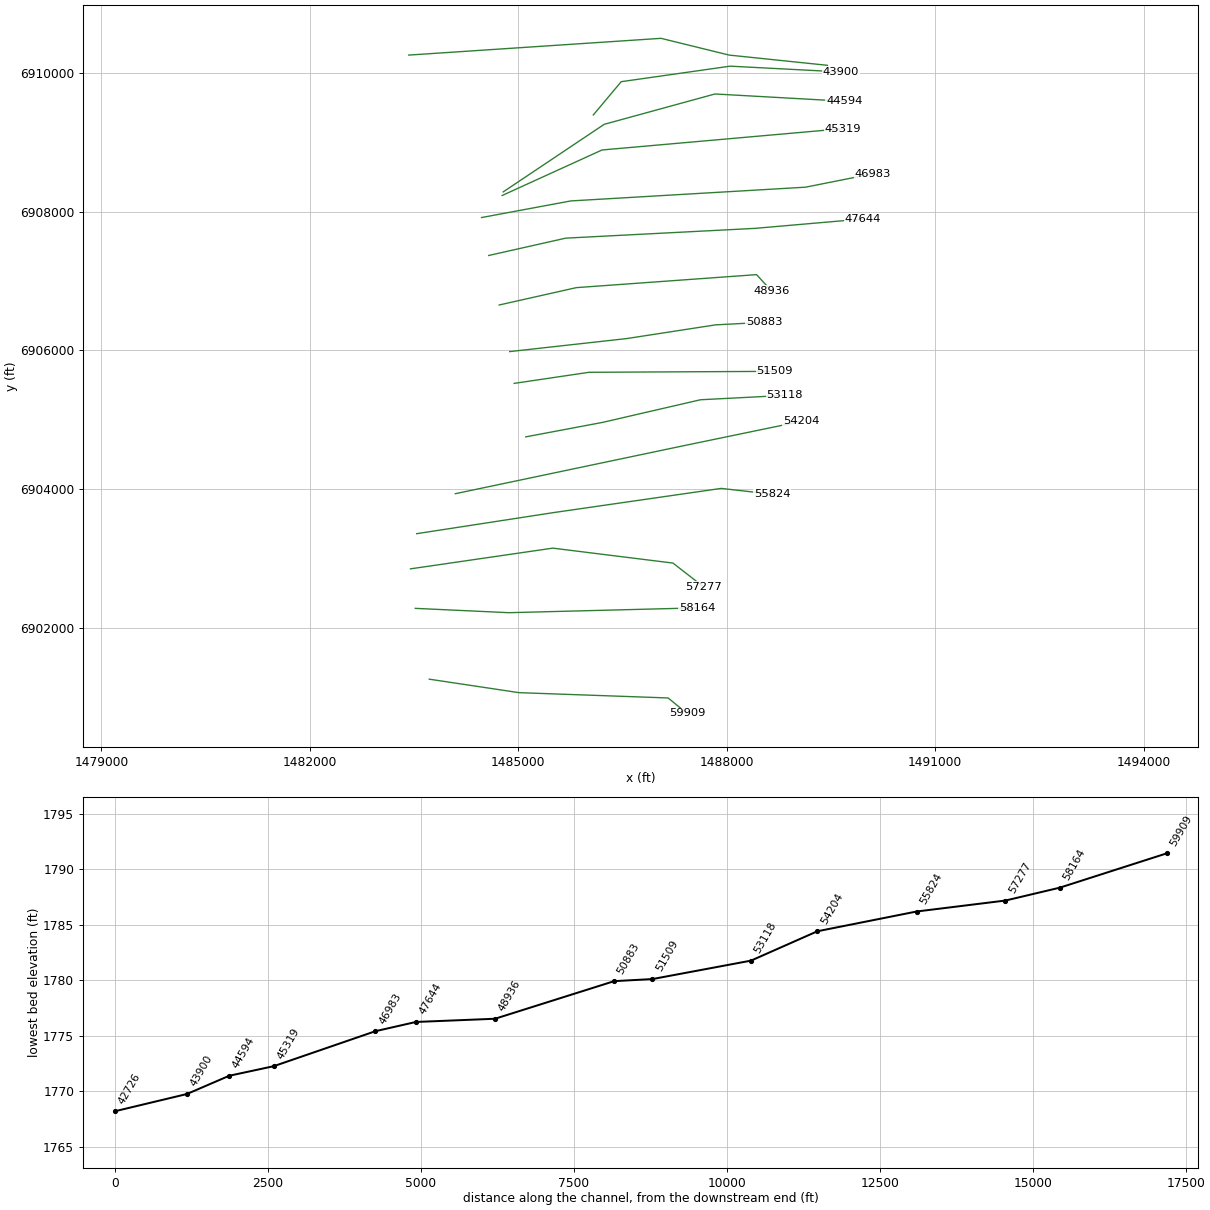
HEC-RAS study Noodle Creek.prj: Noodle Creek Base Level Engineering

--- Noodle Creek.g01 (geometry) --- (continued)

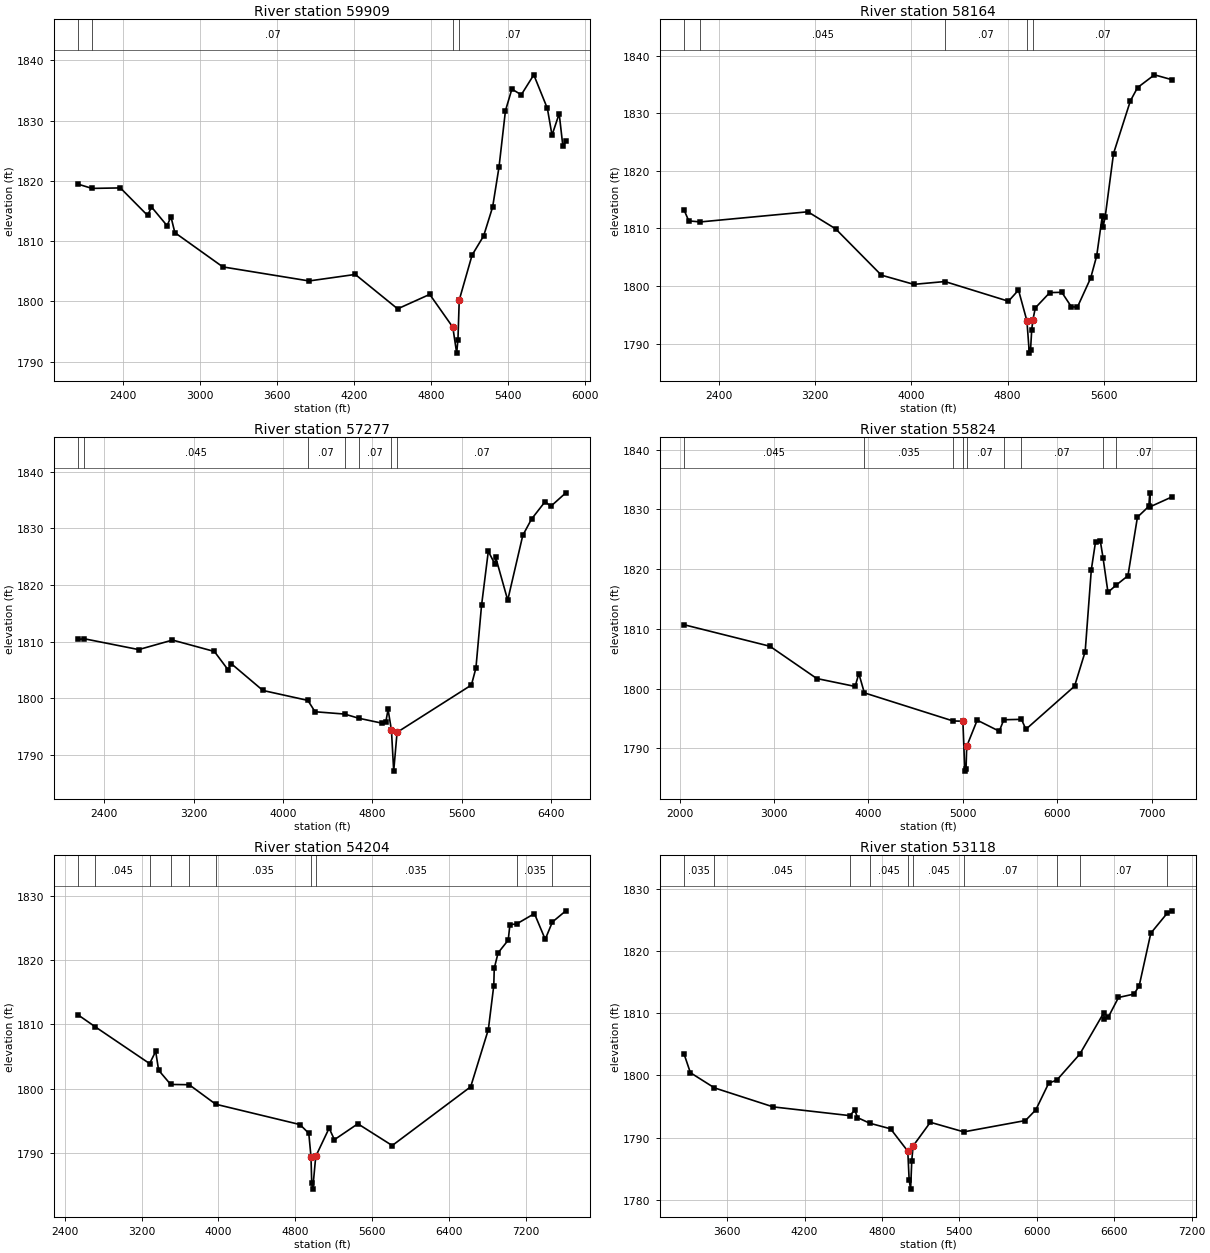
Type RM Length L Ch R = 1 ,59909   ,1745,1745,1745
BEGIN DESCRIPTION:
Mapping XS 8b41ee22
END DESCRIPTION:
XS GIS Cut Line= 4
      1483717.89      6901260.06      1485009.52      6901065.62
      1487155.36      6900989.23      1487426.18      6900767.02
#Sta/Elev= 30
  2047.7 1819.48  2157.4 1818.77  2378.5 1818.85  2590.9 1814.28  2621.2 1815.69
  2742.6 1812.58  2772.9 1814.06  2803.2 1811.43  3177.4 1805.74  3849.7 1803.41
  4209.9 1804.49  4540.1 1798.78  4790.3 1801.18  4970.4 1795.73  5000.4 1791.43
  5010.4 1793.69  5020.4 1800.24  5120.5  1807.7  5210.5 1810.88  5280.6 1815.67
  5330.6 1822.33  5380.6 1831.66  5430.7 1835.25  5504.1 1834.31  5601.6 1837.62
  5707.6 1832.04  5743.7  1827.6  5799.6 1831.18  5828.3 1825.79  5851.4 1826.58
#Mann= 4 ,-1 , 0
  2047.7    .035       0  2157.4     .07       0  4970.4    .045       0
  5020.4     .07       0
Bank Sta=4970.4,5020.4
XS Rating Curve= 0 ,0
Exp/Cntr=0.3,0.1

Type RM Length L Ch R = 1 ,58164   ,887,887,887
BEGIN DESCRIPTION:
Mapping XS 97bb3701
END DESCRIPTION:
XS GIS Cut Line= 3
      1483516.44       6902280.9      1484863.69       6902218.4
        1487571.      6902287.82
#Sta/Elev= 30
  2109.5 1813.18  2148.1  1811.3  2244.5 1811.12  3138.6 1812.88  3369.4 1809.92
  3749.6 1801.88  4019.7 1800.28  4278.1 1800.77  4806.5 1797.35    4890 1799.29
    4960 1793.94    4980 1788.34    4990 1788.85    5000  1792.4    5010 1794.14
    5030  1796.2  5150.1 1798.85  5250.1  1798.9  5330.1 1796.37  5380.1 1796.34
  5490.2 1801.38  5540.2 1805.23  5586.8 1812.15  5591.8 1810.19  5610.2  1811.9
  5680.2    1823  5820.3 1832.14  5880.3 1834.45  6020.4 1836.66  6166.4 1835.81
#Mann= 5 ,-1 , 0
  2109.5    .035       0  2244.5    .045       0  4278.1     .07       0
    4960    .045       0    5010     .07       0
Bank Sta=4960,5010
XS Rating Curve= 0 ,0
Exp/Cntr=0.3,0.1

Type RM Length L Ch R = 1 ,57277   ,1453,1453,1453
BEGIN DESCRIPTION:
Mapping XS bc753d03
END DESCRIPTION:
XS GIS Cut Line= 4
      1483447.02      6902850.34      1485495.63      6903148.95
       1487224.8      6902933.68      1487661.17      6902594.28
#Sta/Elev= 30
  2164.4 1810.41    2223 1810.51  2708.1 1808.61  3010.5 1810.29  3385.1 1808.28
  3506.4 1805.08  3536.7 1806.12  3819.7  1801.4  4221.6 1799.65  4286.1 1797.65
  4550.5 1797.24    4676 1796.51    4889 1795.62  4919.3 1795.86  4939.4 1798.06
  4969.7 1794.37  4989.8 1787.18    5020 1794.02  5685.1 1802.36  5725.5 1805.35
  5775.8  1816.4  5836.3 1825.94  5896.7 1823.63  5901.8 1824.92    6010 1817.32
  6144.8 1828.75  6223.5 1831.63  6344.8  1834.7  6395.5 1833.87    6530 1836.25
#Mann= 7 ,-1 , 0
  2164.4    .035       0    2223    .045       0  4221.6     .07       0
  4550.5    .035       0    4676     .07       0  4969.7    .045       0
    5020     .07       0
Bank Sta=4969.7,5020
XS Rating Curve= 0 ,0
Exp/Cntr=0.3,0.1

Type RM Length L Ch R = 1 ,55824   ,1620,1620,1620
BEGIN DESCRIPTION:
Mapping XS 7ed894a1
END DESCRIPTION:
XS GIS Cut Line= 4
      1483537.31      6903357.29      1485516.47      6903662.84
      1487919.24      6904010.06      1488648.45      6903926.73
#Sta/Elev= 30
  2048.3 1810.69  2956.6 1807.09  3452.4 1801.69  3858.8 1800.36  3897.6 1802.53
  3956.2 1799.29  4894.4 1794.59  4999.2 1794.54  5019.4 1786.19  5032.7 1786.61
  5039.6 1790.34  5150.7 1794.72  5384.3 1792.87  5432.1 1794.79  5619.5 1794.86
    5666 1793.19  6181.3 1800.41  6293.5 1806.19  6358.7 1819.92  6403.6 1824.61
  6454.1 1824.69  6483.4 1821.82  6534.8 1816.12  6618.4 1817.28  6746.1 1818.89
  6846.8  1828.7  6967.6 1830.51  6976.9 1832.77  6981.9 1830.44  7212.6 1832.09
#Mann= 9 ,-1 , 0
  2048.3    .045       0  3956.2    .035       0  4894.4     .07       0
  4999.2    .045       0  5039.6     .07       0  5432.1    .035       0
  5619.5     .07       0  6483.4    .035       0  6618.4     .07       0
Bank Sta=4999.2,5039.6
XS Rating Curve= 0 ,0
Exp/Cntr=0.3,0.1

Type RM Length L Ch R = 1 ,54204   ,1086,1086,1086
BEGIN DESCRIPTION:
Mapping XS 228bc139
END DESCRIPTION:
XS GIS Cut Line= 3
      1484092.89      6903933.68      1487391.47      6904628.12
      1489065.05      6904975.34
#Sta/Elev= 30
  2538.1 1811.49  2717.7 1809.63  3284.5 1803.91  3347.6 1805.81  3378.2 1802.88
  3503.8 1800.67  3696.5 1800.63  3972.5  1797.6  4849.8 1794.44  4941.8 1793.08
  4964.6 1789.46  4972.4 1785.39  4982.6 1784.41  5014.4  1789.5  5153.6 1793.88
  5208.6 1792.09  5452.7 1794.56  5810.4 1791.18  6627.5 1800.31  6811.3  1809.2
  6867.9 1816.01    6873 1818.71  6912.9 1821.11  7018.3 1823.09    7036  1825.5
  7105.5  1825.6  7291.3 1827.21  7403.7 1823.21  7477.9  1825.9  7618.2 1827.64
#Mann= 10 ,-1 , 0
  2538.1     .07       0  2717.7    .045       0  3284.5    .035       0
  3503.8    .045       0  3696.5     .07       0  3972.5    .035       0
  4964.6    .045       0  5014.4    .035       0  7105.5    .035       0
  7477.9     .07       0
Bank Sta=4964.6,5014.4
XS Rating Curve= 0 ,0
Exp/Cntr=0.3,0.1

Type RM Length L Ch R = 1 ,53118   ,1609,1609,1609
BEGIN DESCRIPTION:
Mapping XS c20c7304
END DESCRIPTION:
XS GIS Cut Line= 4
      1485106.79      6904753.13      1486210.91      6904961.45
      1487620.63      6905287.84        1488829.      6905350.34
#Sta/Elev= 30
  3266.6 1803.43  3315.2 1800.45  3501.8 1798.01  3956.8 1794.96  4549.9 1793.56
  4589.4 1794.44    4610 1793.24  4705.1 1792.34  4866.6 1791.44  4999.9 1787.85
  5010.3 1783.27  5021.7 1781.76  5030.8 1786.35  5041.1 1788.69  5174.5 1792.49
  5433.8 1790.95  5911.7 1792.77  5991.8 1794.48  6091.9 1798.77  6154.7 1799.26
  6332.4 1803.42  6517.7 1810.03  6522.7 1809.05  6552.5 1809.33  6632.6 1812.52
  6752.8 1813.07  6792.9 1814.39    6883 1822.84  7009.4 1826.03  7047.2 1826.43
#Mann= 10 ,-1 , 0
  3266.6    .035       0  3501.8    .045       0  4549.9     .16       0
  4705.1    .045       0  4999.9    .045       0  5041.1    .045       0
  5433.8     .07       0  6154.7    .035       0  6332.4     .07       0
  7009.4    .035       0
Bank Sta=4999.9,5041.1
XS Rating Curve= 0 ,0
Exp/Cntr=0.3,0.1

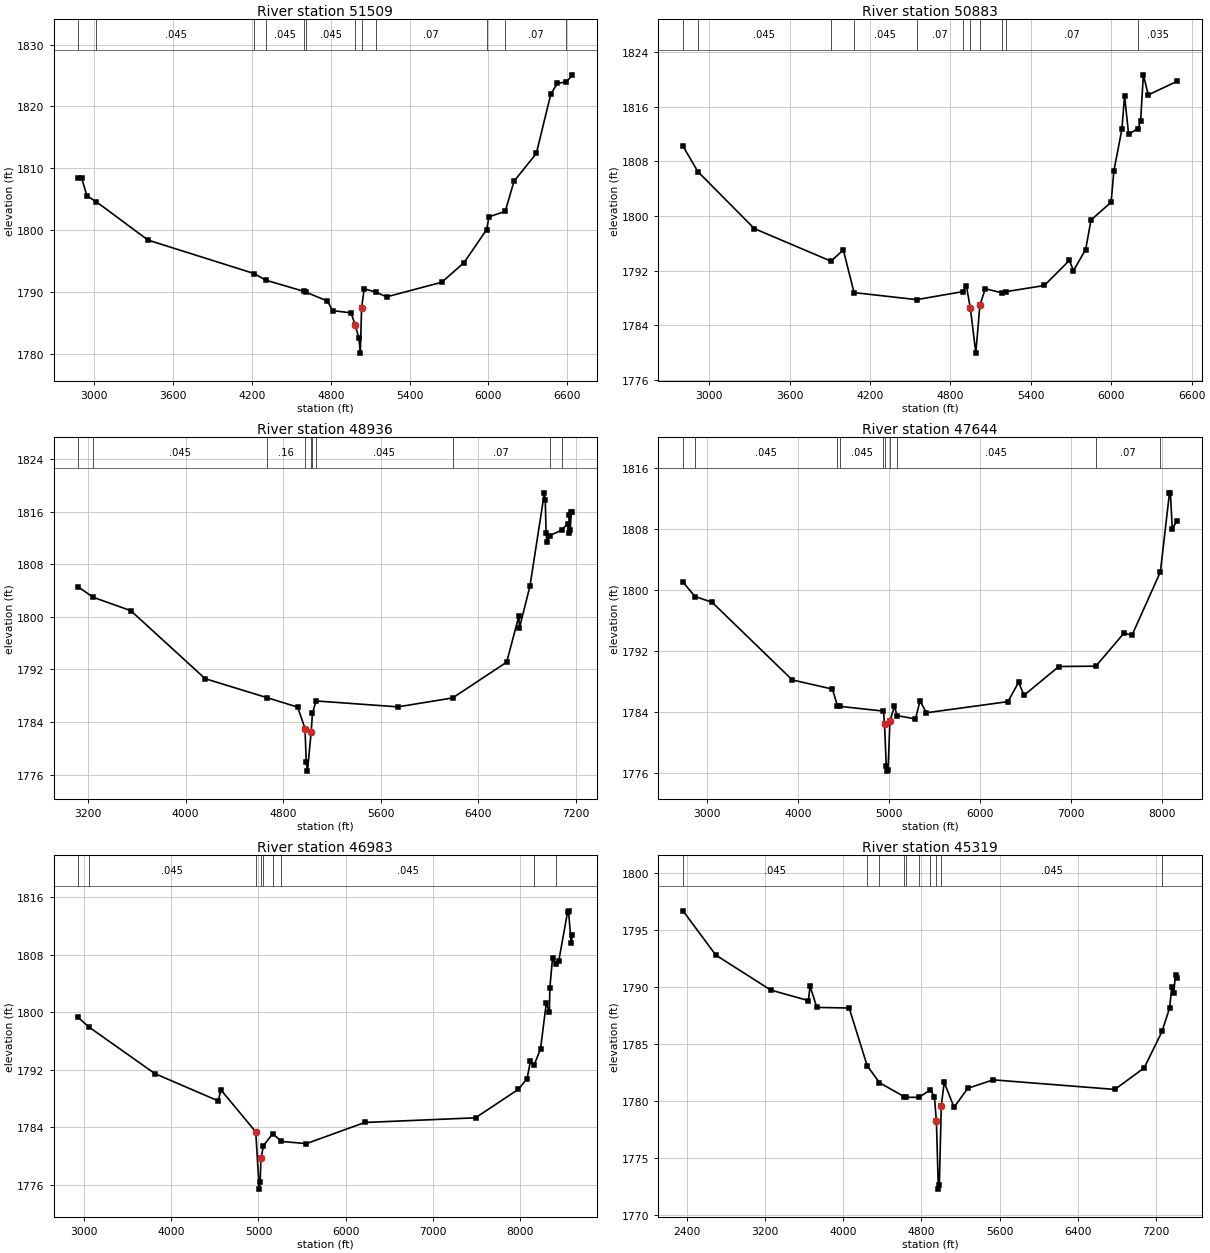
Type RM Length L Ch R = 1 ,51509   ,626,626,626
BEGIN DESCRIPTION:
Mapping XS b7b6d3cc
END DESCRIPTION:
XS GIS Cut Line= 3
      1484940.07      6905523.95      1486016.47      6905683.68
      1488690.05      6905697.56
#Sta/Elev= 30
    2878 1808.38  2903.2 1808.45  2944.2 1805.52  3016.7 1804.56  3408.7 1798.38
  4218.9 1792.95  4304.9  1791.9  4593.4  1790.1  4614.6 1789.93  4774.7 1788.52
  4814.7 1786.97  4954.7 1786.61  4984.7 1784.71  5014.7 1782.47  5024.7  1780.1
  5034.7 1787.47  5054.7  1790.5  5142.6 1789.97  5224.7  1789.2  5644.7 1791.56
  5814.7 1794.74  5985.9 1800.06  6004.7 1802.14  6127.9 1803.03  6194.7 1807.89
  6364.7 1812.39  6474.8 1821.99  6524.8 1823.71  6593.9 1823.96  6639.8  1825.1
#Mann= 12 ,-1 , 0
    2878    .035       0  3016.7    .045       0  4218.9     .07       0
  4304.9    .045       0  4593.4     .07       0  4614.6    .045       0
  4984.7    .045       0  5034.7    .045       0  5142.6     .07       0
  5985.9    .035       0  6127.9     .07       0  6593.9    .035       0
Bank Sta=4984.7,5034.7
XS Rating Curve= 0 ,0
Exp/Cntr=0.3,0.1

Type RM Length L Ch R = 1 ,50883   ,1947,1947,1947
BEGIN DESCRIPTION:
Mapping XS 407771d3
END DESCRIPTION:
XS GIS Cut Line= 4
      1484875.86      6905982.29      1486558.13      6906169.79
      1487839.38       6906367.7      1488537.29      6906404.16
#Sta/Elev= 30
  2804.2 1810.22    2915 1806.49  3336.6 1798.14  3908.9 1793.37  4000.7 1795.02
  4080.9 1788.77  4547.5 1787.74  4894.5 1788.92  4918.7 1789.79  4949.1 1786.45
  4989.5 1779.91  5019.9 1786.95  5060.4 1789.34  5185.8 1788.73  5215.3 1788.91
  5500.5 1789.81  5687.7 1793.48  5718.1 1791.98    5809 1795.07    5849  1799.4
  5999.2    1802  6019.3 1806.55  6079.3 1812.66  6099.4 1817.59  6129.4 1811.98
  6200.1 1812.78  6219.5 1813.95  6239.6 1820.65  6276.4 1817.71  6492.2 1819.71
#Mann= 11 ,-1 , 0
  2804.2    .035       0    2915    .045       0  3908.9     .07       0
  4080.9    .045       0  4547.5     .07       0  4894.5    .045       0
  4949.1    .045       0  5019.9    .045       0  5185.8    .045       0
  5215.3     .07       0  6200.1    .035       0
Bank Sta=4949.1,5019.9
XS Rating Curve= 0 ,0
Exp/Cntr=0.3,0.1

Type RM Length L Ch R = 1 ,48936   ,1292,1292,1292
BEGIN DESCRIPTION:
Mapping XS 1f60d705
END DESCRIPTION:
XS GIS Cut Line= 4
      1484724.84      6906654.17      1485834.18      6906904.16
      1488427.93      6907091.66       1488640.7      6906858.13
#Sta/Elev= 30
  3119.6 1804.54  3244.3 1802.96  3550.3 1800.94  4160.4 1790.59  4667.3  1787.7
  4919.3 1786.26  4979.5 1782.99  4989.5 1777.91  4999.5 1776.52  5029.6 1782.43
  5040.7 1785.31  5069.7  1787.2  5741.4  1786.3  6190.4 1787.66  6633.8 1793.11
  6733.1 1800.12  6738.1  1798.3  6824.3 1804.67    6943 1818.87  6949.8 1817.83
  6956.9 1812.69    6964 1811.42  6986.5 1812.37  7084.1 1813.19  7133.6 1814.17
    7141 1812.82  7147.8 1815.42  7155.2 1813.14    7162 1815.94  7173.2 1816.01
#Mann= 10 ,-1 , 0
  3119.6    .035       0  3244.3    .045       0  4667.3     .16       0
  4979.5    .045       0  5029.6     .16       0  5040.7     .07       0
  5069.7    .045       0  6190.4     .07       0  6986.5    .035       0
  7084.1     .07       0
Bank Sta=4979.5,5029.6
XS Rating Curve= 0 ,0
Exp/Cntr=0.3,0.1

Type RM Length L Ch R = 1 ,47644   ,661,661,661
BEGIN DESCRIPTION:
Mapping XS 64bcfc9d
END DESCRIPTION:
XS GIS Cut Line= 4
      1484573.77      6907367.71      1485683.13       6907617.7
      1488401.88      6907758.33      1489959.14      6907893.74
#Sta/Elev= 30
  2740.4 1801.06  2871.3 1799.15  3059.4  1798.4  3939.5  1788.2  4380.1    1787
  4435.9 1784.78    4461 1784.73  4940.4 1784.11    4952 1782.39  4970.9 1776.91
  4980.9 1776.23  4990.9 1776.43    5011 1782.78    5061 1784.76  5088.7 1783.52
  5291.3 1783.08  5341.4 1785.45  5411.5 1783.89  6305.5 1785.35  6422.8 1787.89
  6482.9 1786.19  6864.1 1789.96  7270.7 1790.01  7579.6 1794.35  7667.1 1794.07
  7978.2 1802.37  8078.6 1812.76  8088.7 1812.73  8108.8 1808.06  8163.1 1809.11
#Mann= 10 ,-1 , 0
  2740.4    .035       0  2871.3    .045       0  4435.9     .07       0
    4461    .045       0  4940.4     .16       0    4952    .045       0
    5011     .16       0  5088.7    .045       0  7270.7     .07       0
  7978.2    .035       0
Bank Sta=4952,5011
XS Rating Curve= 0 ,0
Exp/Cntr=0.3,0.1

Type RM Length L Ch R = 1 ,46983   ,1664,1664,1664
BEGIN DESCRIPTION:
Mapping XS 194cc712
END DESCRIPTION:
XS GIS Cut Line= 4
      1484469.62      6907914.58      1485756.05      6908154.16
      1489131.05      6908352.08      1490099.82      6908544.79
#Sta/Elev= 30
  2930.1 1799.25  3054.3 1797.91  3810.4 1791.45  4538.1 1787.66  4568.2  1789.2
  4968.9 1783.36  5008.9  1775.4  5018.9 1776.34    5029 1779.67  5056.9 1781.43
  5163.8 1783.11  5263.2 1782.03  5549.9 1781.72    6221 1784.66  7493.2 1785.31
  7984.2 1789.25  8086.4 1790.76  8123.1 1793.16  8164.3 1792.58  8239.8 1794.86
  8306.6 1801.28    8342 1800.02  8347.4 1803.38    8378 1807.52  8412.8 1806.71
  8449.4 1807.09  8551.6 1813.96  8561.5 1814.07  8592.1 1809.58  8607.2 1810.75
#Mann= 9 ,-1 , 0
  2930.1    .035       0  3054.3    .045       0  4968.9    .045       0
    5029    .045       0  5056.9     .16       0  5163.8     .07       0
  5263.2    .045       0  8164.3    .035       0  8412.8     .07       0
Bank Sta=4968.9,5029
XS Rating Curve= 0 ,0
Exp/Cntr=0.3,0.1

Type RM Length L Ch R = 1 ,45319   ,725,725,725
BEGIN DESCRIPTION:
Mapping XS 889082cf
END DESCRIPTION:
XS GIS Cut Line= 3
      1484766.46      6908232.28      1486203.97      6908888.54
      1489671.37      6909195.71
#Sta/Elev= 30
  2358.1 1796.64  2694.4 1792.76  3257.9 1789.69  3642.6 1788.77  3659.6 1790.04
  3728.7 1788.17  4059.8 1788.12  4244.7 1783.06  4370.6 1781.57  4621.5 1780.36
  4646.1 1780.29  4776.8 1780.29  4891.1 1780.95  4933.2 1780.34  4953.3 1778.18
  4973.4 1772.24  4983.4 1772.58  5003.5 1779.57  5033.6  1781.6    5134 1779.41
  5274.6 1781.08  5535.6 1781.82  6780.4 1780.98  7081.6 1782.87    7264 1786.07
  7342.6 1788.15  7362.7 1789.92  7382.8 1789.46  7402.9 1791.03  7419.3 1790.77
#Mann= 10 ,-1 , 0
  2358.1    .045       0  4244.7     .07       0  4370.6    .045       0
  4621.5    .035       0  4646.1    .045       0  4776.8    .035       0
  4891.1    .045       0  4953.3    .045       0  5003.5    .045       0
    7264    .035       0
Bank Sta=4953.3,5003.5
XS Rating Curve= 0 ,0
Exp/Cntr=0.3,0.1

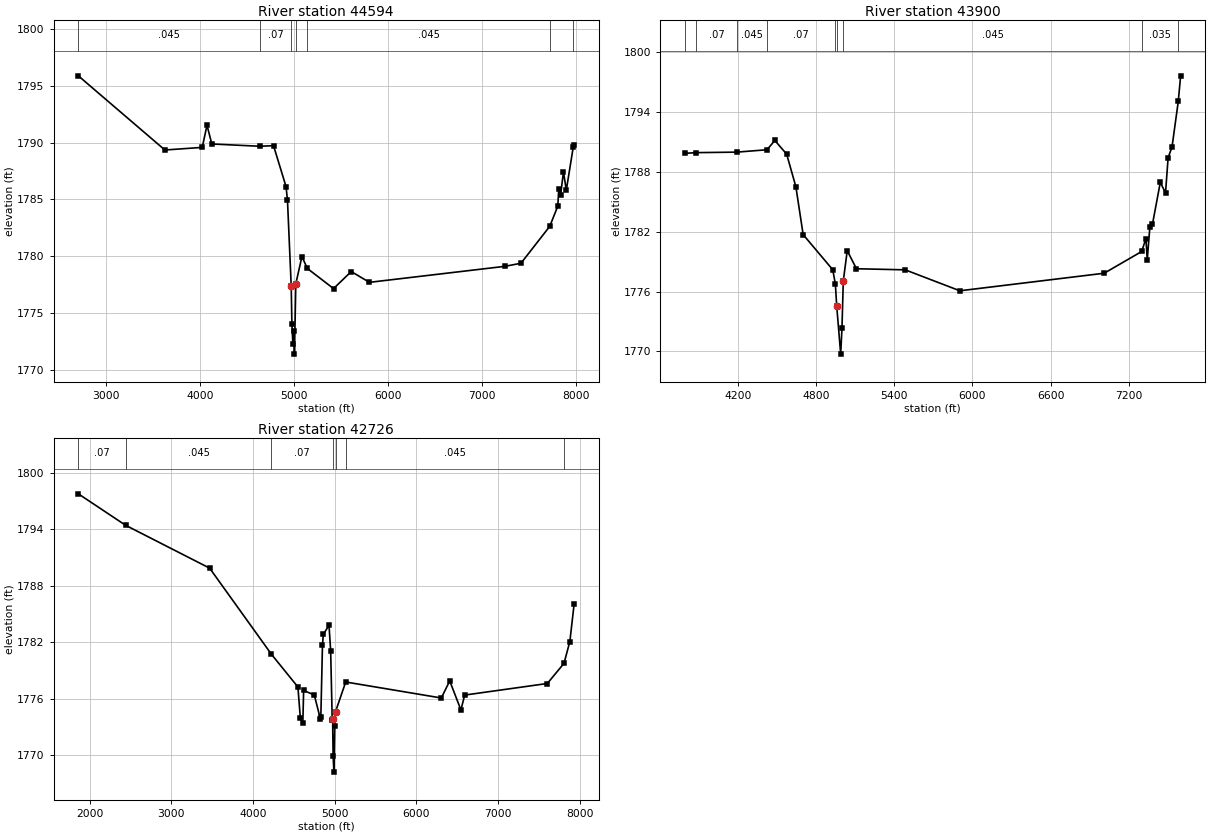
Type RM Length L Ch R = 1 ,44594   ,694,694,694
BEGIN DESCRIPTION:
Mapping XS 1b6a7542
END DESCRIPTION:
XS GIS Cut Line= 4
      1484782.13      6908284.39      1486235.22      6909258.33
      1487828.97      6909695.83      1489688.35      6909591.66
#Sta/Elev= 30
  2711.1 1795.88  3630.1 1789.35  4026.7 1789.58  4077.3 1791.53  4128.3 1789.88
  4637.2 1789.68  4783.5 1789.73  4916.4 1786.13  4931.7 1784.92  4971.3 1777.38
  4978.7    1774    4989 1772.29  4999.4  1773.4  5005.7 1771.38  5020.1 1777.57
    5085 1779.97  5142.6 1778.92  5420.9 1777.15  5608.7 1778.65  5801.6  1777.7
  7241.1 1779.11  7410.6 1779.38  7716.2 1782.63  7801.8 1784.41  7811.8 1785.93
  7831.8 1785.41  7861.9 1787.43  7891.9 1785.81  7965.2 1789.58  7975.4 1789.83
#Mann= 7 ,-1 , 0
  2711.1    .045       0  4637.2     .07       0  4971.3    .045       0
  5020.1     .07       0  5142.6    .045       0  7716.2    .035       0
  7965.2     .07       0
Bank Sta=4971.3,5020.1
XS Rating Curve= 0 ,0
Exp/Cntr=0.3,0.1

Type RM Length L Ch R = 1 ,43900   ,1174,1174,1174
BEGIN DESCRIPTION:
Mapping XS bcb1e39b
END DESCRIPTION:
XS GIS Cut Line= 4
      1486078.95      6909393.73      1486480.01      6909872.91
      1488047.72      6910096.87      1489640.74      6910013.57
#Sta/Elev= 30
  3794.2 1789.86  3882.8 1789.93  4192.9 1789.98  4425.2 1790.22  4484.7 1791.15
  4575.6 1789.78  4646.3 1786.51  4702.2 1781.71  4929.2 1778.19  4949.3 1776.75
  4959.5 1774.57  4990.1 1769.73  4999.9 1772.31    5010 1777.06  5040.3  1780.1
    5111 1778.29  5485.1 1778.18  5904.3 1776.08  7011.4 1777.84  7299.4 1780.02
  7331.8 1781.32  7341.8 1779.19  7361.8 1782.44  7381.9 1782.75  7441.9 1786.95
    7482  1785.9    7502 1789.42  7532.1 1790.51    7580 1795.08  7597.9 1797.63
#Mann= 9 ,-1 , 0
  3794.2    .045       0  3882.8     .07       0  4192.9    .045       0
  4425.2     .07       0  4949.3    .045       0  4959.5    .045       0
    5010    .045       0  7299.4    .035       0    7580     .07       0
Bank Sta=4959.5,5010
XS Rating Curve= 0 ,0
Exp/Cntr=0.3,0.1

Type RM Length L Ch R = 1 ,42726   ,207,207,207
BEGIN DESCRIPTION:
Noodle Creek 30.0
END DESCRIPTION:
XS GIS Cut Line= 4
      1483423.11      6910256.59      1487052.93      6910497.91
      1488032.53      6910256.59      1489447.44      6910109.02
#Sta/Elev= 30
  1861.2 1797.76  2439.2 1794.42  3468.5 1789.86  4225.6  1780.7    4549 1777.23
  4579.1 1773.88  4609.1 1773.39  4619.2 1776.86  4749.4 1776.38  4823.3 1773.87
  4829.6 1774.04  4849.7 1781.67  4859.7 1782.81  4929.8 1783.79  4949.9 1781.07
  4968.8 1773.76  4973.8 1773.82    4980 1769.89    4990 1768.18    5000  1773.1
    5010 1774.62    5134 1777.76  6304.5 1776.06  6407.5 1777.88  6544.1 1774.79
  6590.8 1776.37  7602.1  1777.6  7805.9 1779.74  7877.8 1782.06  7930.5 1786.08
#Mann= 7 ,-1 , 0
  1861.2     .07       0  2439.2    .045       0  4225.6     .07       0
  4973.8    .045       0    5010     .07       0    5134    .045       0
  7805.9    .035       0
Bank Sta=4973.8,5010
XS Rating Curve= 0 ,0
Exp/Cntr=0.3,0.1