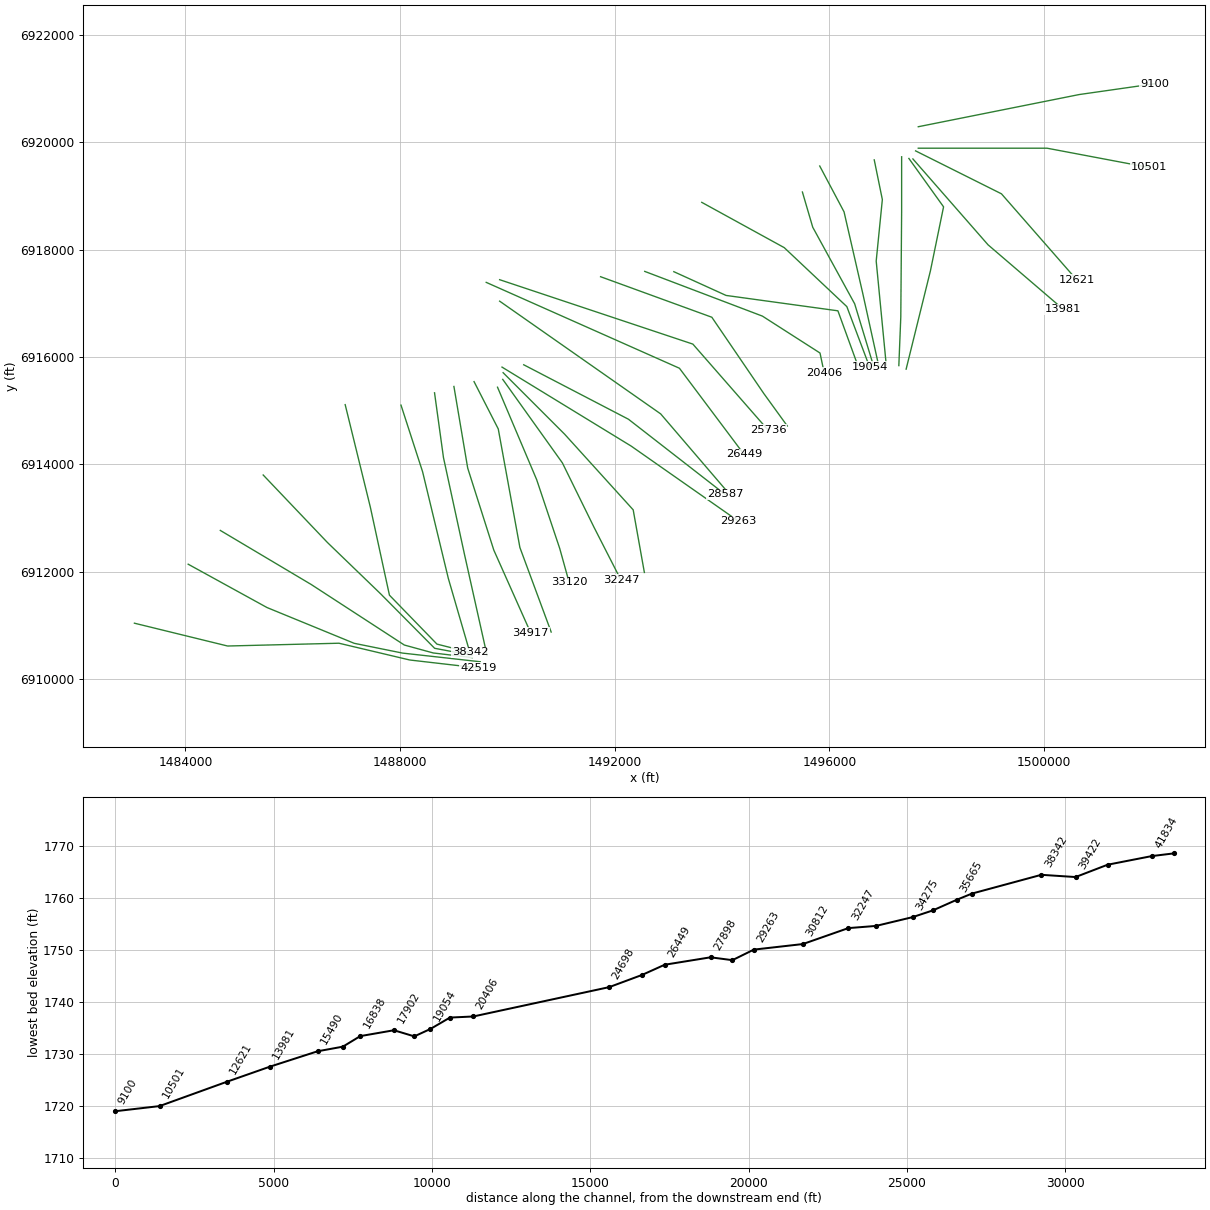
HEC-RAS study Noodle Creek.prj: Noodle Creek Base Level Engineering

--- Noodle Creek.g01 (geometry) --- (continued)

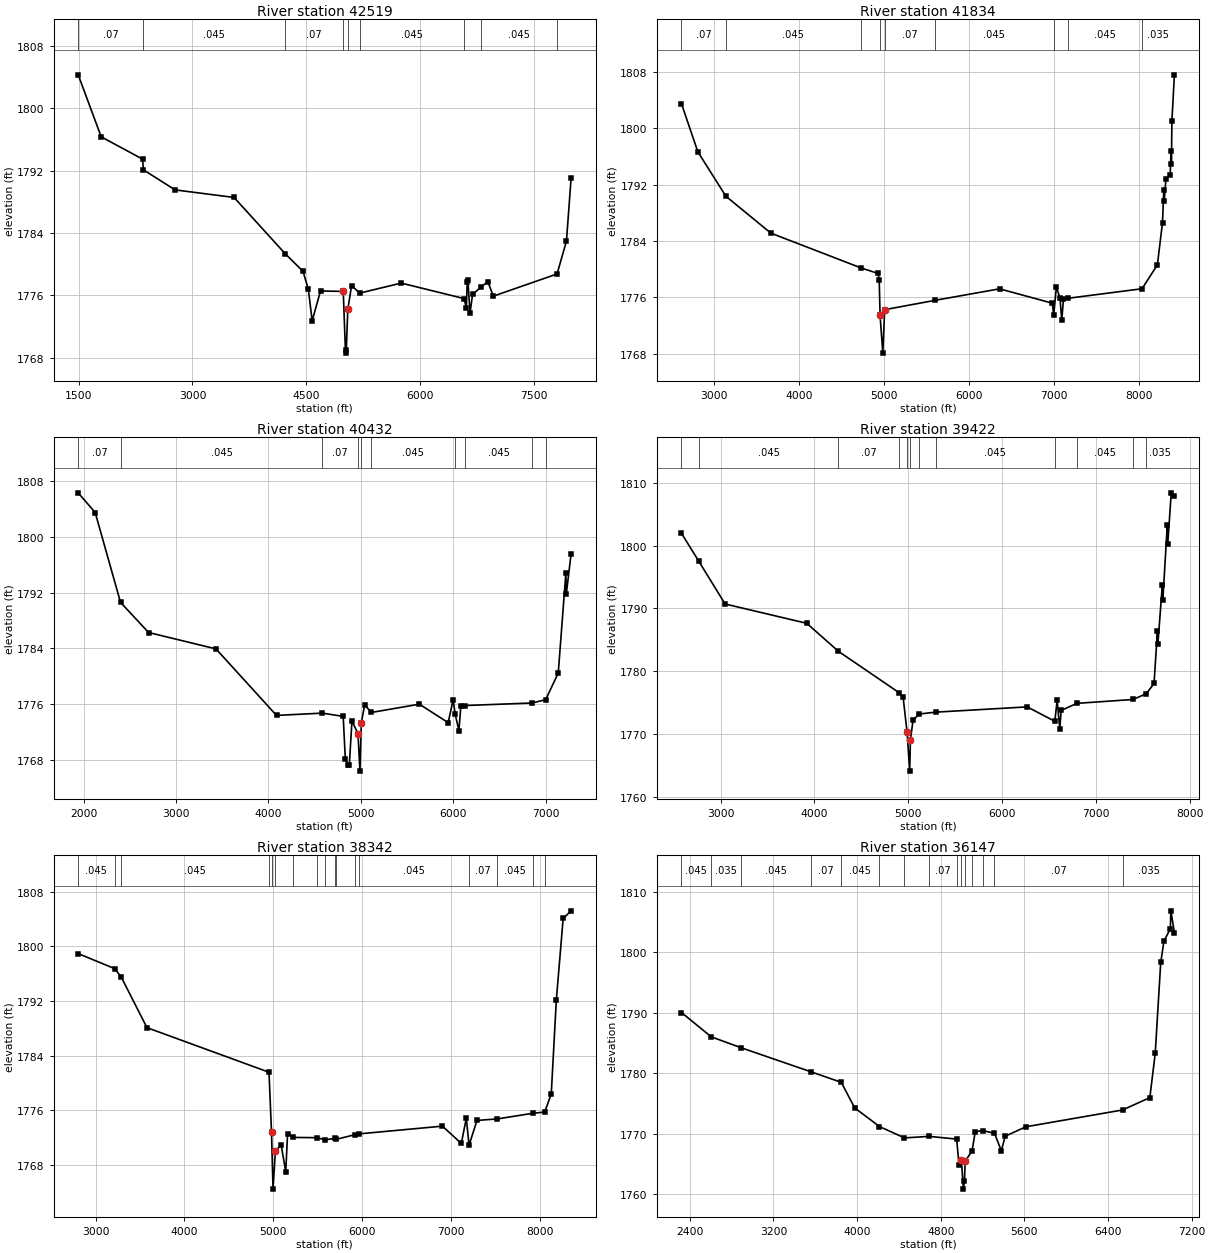
Type RM Length L Ch R = 1 ,42519   ,685,685,685
BEGIN DESCRIPTION:
Noodle Creek 29.0
END DESCRIPTION:
XS GIS Cut Line= 5
      1483049.92      6911037.83        1484786.      6910612.49
      1486860.65      6910664.58       1488180.1      6910352.08
      1489456.12      6910204.51
#Sta/Elev= 30
  1492.3 1804.32  1796.1 1796.36  2341.8  1793.5  2352.4 1792.13  2771.2 1789.55
  3548.8 1788.58  4222.4 1781.37  4459.1 1779.09  4529.1 1776.77  4579.1 1772.75
  4689.2 1776.58  4989.3 1776.52  5019.3  1768.6  5029.3 1768.98  5049.3  1774.2
  5099.3 1777.28  5205.6  1776.3  5753.8 1777.59  6583.9  1775.6  6613.2 1774.42
  6624.4 1777.68  6633.8 1777.98  6661.5 1773.74  6695.5 1776.14  6802.7 1777.04
  6897.1 1777.78  6968.3 1775.91    7810 1778.76    7934 1782.99  7995.5 1791.07
#Mann= 9 ,-1 , 0
  1492.3     .07       0  2352.4    .045       0  4222.4     .07       0
  4989.3    .045       0  5049.3     .07       0  5205.6    .045       0
  6583.9     .07       0  6802.7    .045       0    7810    .035       0
Bank Sta=4989.3,5049.3
XS Rating Curve= 0 ,0
Exp/Cntr=0.3,0.1

Type RM Length L Ch R = 1 ,41834   ,1402,1402,1402
BEGIN DESCRIPTION:
Mapping XS 7d757e28
END DESCRIPTION:
XS GIS Cut Line= 6
      1484051.66      6912136.78      1485520.37      6911329.51
      1487145.37      6910662.84      1488046.41      6910480.55
      1488749.54      6910402.43      1489494.35      6910319.09
#Sta/Elev= 30
  2614.2 1803.51  2807.6 1796.67  3137.3 1790.37  3667.8 1785.13  4729.9 1780.19
  4932.9  1779.4  4944.4 1778.45  4954.5 1773.44  4986.9 1768.09  5008.5 1774.26
  5599.7 1775.58  6362.5 1777.22  6984.6 1775.18  7000.1 1773.44  7032.1 1777.47
  7075.1 1775.89  7095.3 1772.73  7115.4 1775.74  7169.1 1775.88  8041.3 1777.23
  8222.2 1780.62  8282.6 1786.63  8297.7 1791.25  8302.7 1789.66  8322.8 1792.87
  8373.1 1793.33  8382.9 1796.81  8387.9 1794.98  8393.3 1801.04  8422.8 1807.61
#Mann= 9 ,-1 , 0
  2614.2     .07       0  3137.3    .045       0  4729.9     .07       0
  4954.5    .045       0  5008.5     .07       0  5599.7    .045       0
  7000.1     .07       0  7169.1    .045       0  8041.3    .035       0
Bank Sta=4954.5,5008.5
XS Rating Curve= 0 ,0
Exp/Cntr=0.3,0.1

Type RM Length L Ch R = 1 ,40432   ,1010,1010,1010
BEGIN DESCRIPTION:
Mapping XS 512f412e
END DESCRIPTION:
XS GIS Cut Line= 5
      1484650.55      6912766.16      1486343.29       6911759.2
       1488079.4      6910630.72       1488617.6      6910483.15
      1489346.74      6910396.35
#Sta/Elev= 30
  1942.5 1806.29  2126.4 1803.47  2400.5  1790.6    2704 1786.28  3433.2 1783.93
  4087.9  1774.4  4584.6 1774.73  4809.4 1774.26  4832.5 1768.13  4860.8 1767.36
  4875.9 1767.33  4904.1 1773.61  4969.5 1771.78  4990.6 1766.42  5005.8 1773.37
    5042 1775.95    5112 1774.82  5633.8 1776.01  5944.8 1773.37  5998.9 1776.65
  6021.3 1774.56  6061.1 1772.24  6081.9 1775.69  6130.9 1775.82  6851.4 1776.18
  6998.9 1776.65  7135.8 1780.46  7218.4 1794.83  7223.4 1791.85  7275.1 1797.59
#Mann= 10 ,-1 , 0
  1942.5     .07       0  2400.5    .045       0  4584.6     .07       0
  4969.5    .045       0  5005.8     .07       0    5112    .045       0
  6021.3     .07       0  6130.9    .045       0  6851.4     .07       0
  6998.9    .035       0
Bank Sta=4969.5,5005.8
XS Rating Curve= 0 ,0
Exp/Cntr=0.3,0.1

Type RM Length L Ch R = 1 ,39422   ,1080,1080,1080
BEGIN DESCRIPTION:
Mapping XS 35a039d1
END DESCRIPTION:
XS GIS Cut Line= 5
      1485449.18      6913799.14      1486647.11      6912540.45
      1487636.69      6911585.59      1488643.64      6910569.96
      1489338.08      6910439.75
#Sta/Elev= 30
  2583.6 1801.96  2765.5 1797.57  3048.3 1790.69  3918.3 1787.61  4255.5 1783.14
  4904.5 1776.52  4943.7 1775.89  4986.1 1770.27  5014.4 1764.05  5021.6 1769.02
  5049.9 1772.16  5113.7 1773.15  5290.4 1773.45  6266.2 1774.29  6559.5 1771.99
  6584.4 1775.33  6612.7 1770.76  6626.8 1773.72  6793.7 1774.85  7391.9 1775.47
    7534 1776.39  7616.3 1778.02  7652.3 1786.35  7657.4 1784.37  7704.9 1793.78
    7710 1791.35  7757.4  1803.3  7762.5  1800.3  7799.4 1808.41  7833.1 1807.95
#Mann= 12 ,-1 , 0
  2583.6     .07       0  2765.5    .045       0  4255.5     .07       0
  4904.5    .045       0  4986.1    .045       0  5021.6    .045       0
  5113.7     .07       0  5290.4    .045       0  6559.5     .07       0
  6793.7    .045       0  7391.9     .07       0    7534    .035       0
Bank Sta=4986.1,5021.6
XS Rating Curve= 0 ,0
Exp/Cntr=0.3,0.1

Type RM Length L Ch R = 1 ,38342   ,2195,2195,2195
BEGIN DESCRIPTION:
Mapping XS 58df3407
END DESCRIPTION:
XS GIS Cut Line= 5
      1486976.98      6915109.87      1487445.72      6913200.17
      1487801.62      6911559.54      1488687.04      6910648.09
      1489301.71      6910492.25
#Sta/Elev= 30
    2805 1798.96  3214.1 1796.77  3288.4 1795.56  3579.2 1788.12  4953.5 1781.59
  4981.8 1772.77  4998.7 1764.48  5025.9  1770.1  5090.8 1770.91    5142 1767.02
  5162.4 1772.53  5223.9 1772.05  5488.7 1772.01  5585.7 1771.71  5694.2  1771.9
  5710.8 1771.77    5923 1772.46    5968 1772.57  6906.3  1773.7  7118.5 1771.17
    7175 1774.87  7205.8 1770.91  7295.2 1774.54  7520.1 1774.75  7921.9 1775.58
    8058 1775.76  8131.4 1778.43  8188.7 1792.22  8265.5  1804.1    8355 1805.22
#Mann= 17 ,-1 , 0
    2805    .045       0  3214.1    .035       0  3288.4    .045       0
  4953.5     .07       0  4981.8    .045       0  5025.9     .07       0
  5223.9    .045       0  5488.7     .07       0  5585.7    .045       0
  5694.2     .07       0  5710.8    .045       0    5923     .07       0
    5968    .045       0  7205.8     .07       0  7520.1    .045       0
  7921.9     .07       0    8058    .035       0
Bank Sta=4981.8,5025.9
XS Rating Curve= 0 ,0
Exp/Cntr=0.3,0.1

Type RM Length L Ch R = 1 ,36147   ,482,482,482
BEGIN DESCRIPTION:
Mapping XS 8f32cc18
END DESCRIPTION:
XS GIS Cut Line= 4
      1488016.89      6915101.26      1488419.68      6913858.15
      1488898.85      6911872.04       1489279.9      6910562.59
#Sta/Elev= 30
  2320.8 1790.02  2606.2    1786  2891.8  1784.2  3559.5 1780.23  3848.5  1778.5
  3977.4 1774.27  4214.4 1771.19  4453.3 1769.32    4691 1769.57  4952.2 1769.12
  4975.3 1764.78  4997.2 1765.75  5016.4 1760.86  5026.7 1762.17  5033.9 1765.48
  5099.7 1767.17  5129.6 1770.32  5199.7 1770.54  5314.1 1770.07  5379.3 1767.21
  5416.1 1769.59  5613.1 1771.15  6538.7 1773.93  6799.6 1775.97  6851.2 1783.31
  6903.8 1798.32    6935 1801.84  6995.6 1803.83  7000.8 1806.81  7034.4 1803.17
#Mann= 15 ,-1 , 0
  2320.8    .045       0  2606.2    .035       0  2891.8    .045       0
  3559.5     .07       0  3848.5    .045       0  4214.4     .07       0
  4453.3    .035       0    4691     .07       0  4952.2    .045       0
  4997.2    .045       0  5033.9    .045       0  5099.7     .07       0
  5199.7    .045       0  5314.1     .07       0  6538.7    .035       0
Bank Sta=4997.2,5033.9
XS Rating Curve= 0 ,0
Exp/Cntr=0.3,0.1

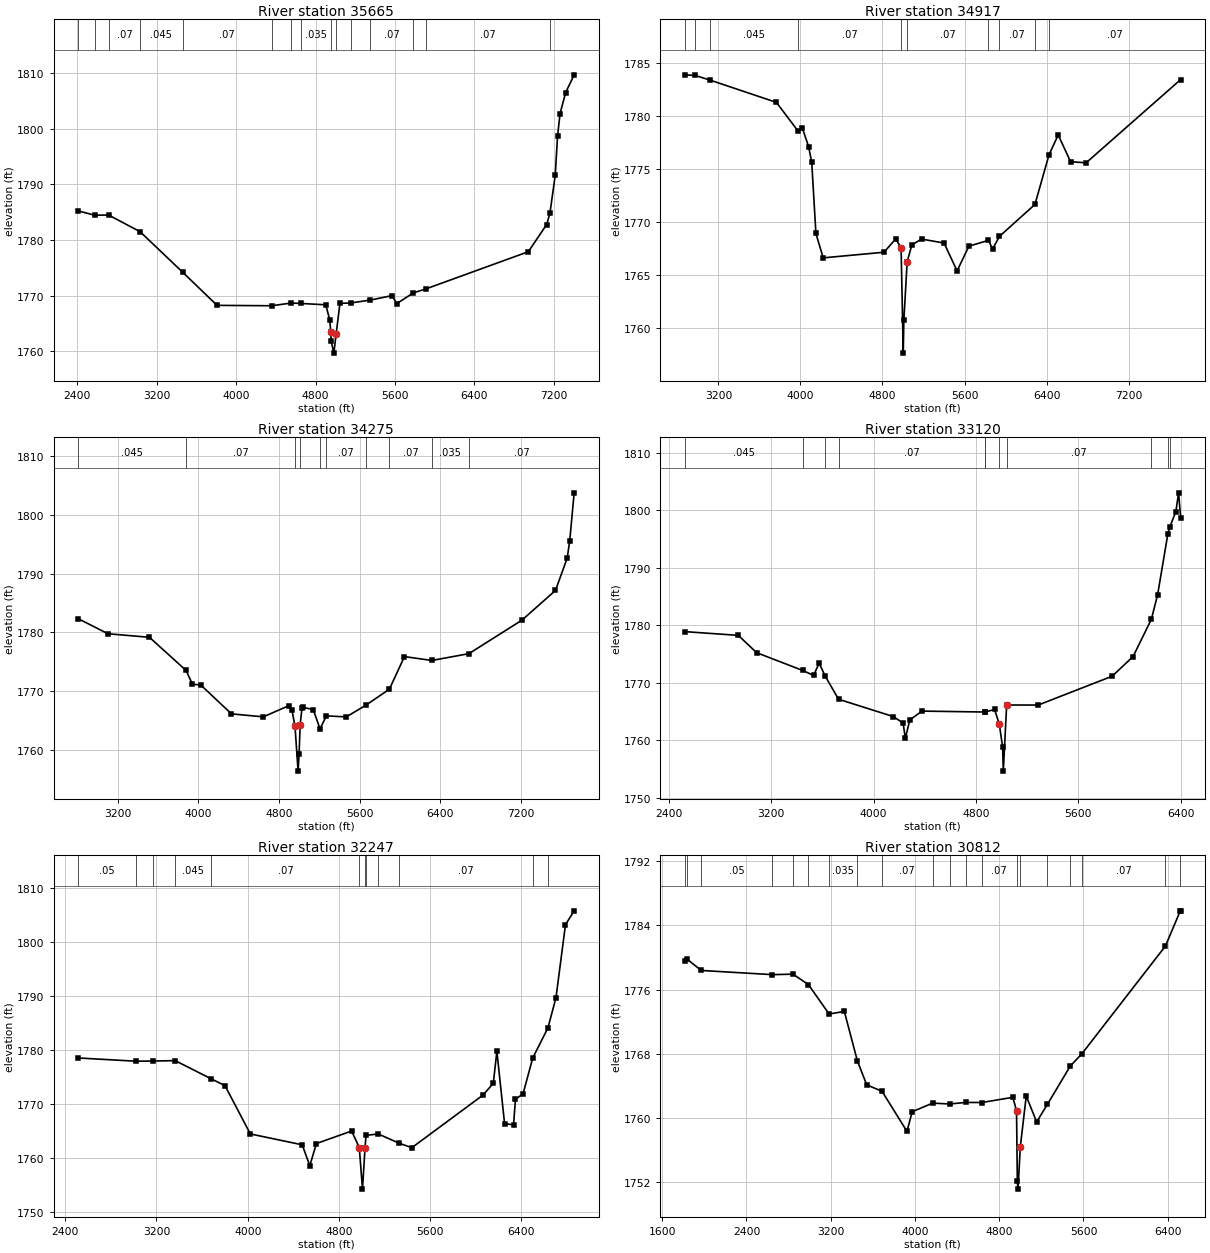
Type RM Length L Ch R = 1 ,35665   ,748,748,748
BEGIN DESCRIPTION:
Mapping XS 57f19635
END DESCRIPTION:
XS GIS Cut Line= 4
       1488641.9      6915330.35      1488808.57      6914122.04
      1489197.46      6912330.38      1489621.06      6910434.56
#Sta/Elev= 30
  2409.4  1785.2  2576.1 1784.43  2714.3 1784.47  3031.6 1781.47  3461.4 1774.18
  3807.2 1768.24  4356.4 1768.17  4555.5 1768.66  4655.1 1768.58  4902.2 1768.34
  4943.1  1765.6  4952.1 1763.54  4957.2 1761.81    4984 1759.66  5006.3 1763.02
  5045.3  1768.6    5153 1768.67  5352.2 1769.19  5569.2 1769.99  5618.7 1768.57
  5784.9 1770.48  5908.6 1771.18  6943.6 1777.88  7127.6 1782.75    7161  1784.8
  7214.4 1791.61  7237.6 1798.58  7262.9 1802.68  7319.6 1806.47  7405.1 1809.65
#Mann= 15 ,-1 , 0
  2409.4    .035       0  2576.1    .045       0  2714.3     .07       0
  3031.6    .045       0  3461.4     .07       0  4356.4    .035       0
  4555.5     .07       0  4655.1    .035       0  4952.1    .045       0
  5006.3     .07       0    5153    .035       0  5352.2     .07       0
  5784.9    .035       0  5908.6     .07       0    7161    .035       0
Bank Sta=4952.1,5006.3
XS Rating Curve= 0 ,0
Exp/Cntr=0.3,0.1

Type RM Length L Ch R = 1 ,34917   ,642,642,642
BEGIN DESCRIPTION:
Mapping XS 6a4d63e6
END DESCRIPTION:
XS GIS Cut Line= 4
      1489003.02      6915448.38      1489259.96       6913927.6
      1489746.07      6912399.82      1490433.57      6910858.16
#Sta/Elev= 30
  2872.7 1783.89  2974.2 1783.83  3119.5 1783.39  3765.6 1781.29  3976.2 1778.59
  4019.1 1778.85    4080 1777.11  4110.2 1775.62  4150.9 1768.92  4221.9 1766.62
  4814.8 1767.15  4928.8 1768.41  4981.3 1767.56  5002.3 1757.63  5008.2 1760.73
  5040.4 1766.25  5086.2 1767.84  5180.7 1768.39  5400.2 1768.02    5527 1765.39
  5642.4 1767.72  5832.8 1768.27  5873.3 1767.46  5940.5 1768.65  6286.1 1771.66
  6423.5 1776.35    6513 1778.22  6633.4 1775.69  6785.2 1775.59  7706.3 1783.44
#Mann= 10 ,-1 , 0
  2872.7    .045       0  2974.2    .035       0  3119.5    .045       0
  3976.2     .07       0  4981.3    .045       0  5040.4     .07       0
  5832.8    .035       0  5940.5     .07       0  6286.1    .035       0
  6423.5     .07       0
Bank Sta=4981.3,5040.4
XS Rating Curve= 0 ,0
Exp/Cntr=0.3,0.1

Type RM Length L Ch R = 1 ,34275   ,1155,1155,1155
BEGIN DESCRIPTION:
Mapping XS b89e3099
END DESCRIPTION:
XS GIS Cut Line= 4
        1489378.      6915538.74       1489829.4      6914656.77
      1490232.18      6912448.43      1490815.34      6910872.51
#Sta/Elev= 30
  2810.2  1782.3  3104.3 1779.74    3515 1779.14  3878.3 1773.49    3942 1771.13
  4022.8 1771.03  4328.3 1766.09  4644.4 1765.58  4897.5 1767.49    4928 1766.77
  4958.5 1763.94    4989 1756.33  4999.2 1759.31  5009.4 1764.23  5027.5 1767.04
  5039.8 1767.19  5139.2 1766.82  5206.3 1763.53  5269.6 1765.75  5466.8 1765.57
  5660.6 1767.56  5893.9 1770.29  6043.4 1775.85  6314.9 1775.19  6682.6 1776.35
  7208.4 1782.06  7541.1 1787.13  7657.3 1792.66  7682.4 1795.63  7726.1 1803.76
#Mann= 10 ,-1 , 0
  2810.2    .045       0  3878.3     .07       0  4958.5    .045       0
  5009.4     .07       0  5206.3    .035       0  5269.6     .07       0
  5660.6    .035       0  5893.9     .07       0  6314.9    .035       0
  6682.6     .07       0
Bank Sta=4958.5,5009.4
XS Rating Curve= 0 ,0
Exp/Cntr=0.3,0.1

Type RM Length L Ch R = 1 ,33120   ,873,873,873
BEGIN DESCRIPTION:
Mapping XS 1749f99f
END DESCRIPTION:
XS GIS Cut Line= 4
       1489815.5      6915434.57      1490544.68      6913712.32
      1490975.23       6912427.6       1491148.8      6911802.76
#Sta/Elev= 30
  2524.7  1778.9  2942.8 1778.25  3085.7 1775.24  3445.7 1772.15  3530.9 1771.28
  3574.3 1773.42  3620.7  1771.2  3725.8 1767.14  4153.7 1764.13  4230.2    1763
  4247.6 1760.36    4283 1763.55  4377.7 1765.08  4868.3 1764.92  4868.8  1764.9
  4944.7 1765.37  4981.5 1762.84  5007.8  1758.8  5013.1 1754.64  5039.3 1766.14
  5285.4 1766.13  5863.7 1771.15  6026.9 1774.57  6169.7 1781.04  6218.9 1785.34
  6299.1 1795.96  6312.8 1797.05  6361.1 1799.76  6382.6 1803.04  6398.4 1798.74
#Mann= 11 ,-1 , 0
  2524.7    .045       0  3445.7    .035       0  3620.7     .16       0
  3725.8     .07       0  4868.3    .035       0  4868.8     .07       0
  4981.5    .045       0  5039.3     .07       0  6169.7    .035       0
  6299.1     .07       0  6312.8    .035       0
Bank Sta=4981.5,5039.3
XS Rating Curve= 0 ,0
Exp/Cntr=0.3,0.1

Type RM Length L Ch R = 1 ,32247   ,1435,1435,1435
BEGIN DESCRIPTION:
Mapping XS 731eaf5f
END DESCRIPTION:
XS GIS Cut Line= 4
      1489912.71      6915580.41      1491023.85      6914024.82
      1491614.12      6912823.43      1492114.13      6911844.24
#Sta/Elev= 30
  2514.3 1778.51  3019.1 1777.91  3172.1 1777.94  3363.6 1778.02  3681.5 1774.63
  3800.7 1773.39  4023.2 1764.44  4478.1 1762.43    4545 1758.55  4602.5 1762.66
  4911.6 1764.98  4979.1 1761.92  5007.1 1754.22  5029.6 1761.91  5038.3 1764.19
    5146 1764.43  5323.4 1762.77  5439.8 1761.89  6065.7 1771.66  6154.6 1773.82
  6186.1 1779.75  6253.5 1766.36  6332.4 1766.12    6349 1770.86  6415.7 1771.87
  6500.7 1778.51  6634.3  1784.1  6704.6 1789.69  6787.9  1803.2    6864 1805.76
#Mann= 12 ,-1 , 0
  2514.3     .05       0  3019.1    .045       0  3172.1     .07       0
  3363.6    .045       0  3681.5     .07       0  4979.1    .045       0
  5029.6     .07       0  5038.3     .07       0    5146    .035       0
  5323.4     .07       0  6500.7    .035       0  6634.3     .07       0
Bank Sta=4979.1,5029.6
XS Rating Curve= 0 ,0
Exp/Cntr=0.3,0.1

Type RM Length L Ch R = 1 ,30812   ,1549,1549,1549
BEGIN DESCRIPTION:
Mapping XS a6db85bd
END DESCRIPTION:
XS GIS Cut Line= 4
       1489919.7      6915705.36      1491065.51      6914559.54
      1492343.29      6913149.82      1492551.62      6911983.14
#Sta/Elev= 30
  1814.4 1779.59  1836.9 1779.78  1971.6 1778.39  2645.3 1777.87  2842.1 1777.93
  2988.4 1776.63  3184.3 1772.97  3329.5 1773.28    3453 1767.13  3541.9 1764.14
  3687.2 1763.34  3923.8 1758.35  3973.8 1760.79  4167.2 1761.86  4330.9 1761.76
  4483.1 1761.95  4635.3 1761.94  4929.4 1762.59  4964.5 1760.91    4972 1752.12
  4978.7 1751.15  5000.4 1756.44  5056.5 1762.74  5155.8 1759.52  5257.9 1761.72
  5474.3 1766.47  5585.6 1768.02  6378.1 1781.43  6519.7 1785.82  6522.6 1785.82
#Mann= 20 ,-1 , 0
  1814.4    .035       0  1836.9    .045       0  1971.6     .05       0
  2645.3     .07       0  2842.1    .045       0  2988.4    .045       0
  3184.3    .035       0    3453     .07       0  3687.2     .07       0
  4167.2     .07       0  4330.9    .035       0  4483.1     .07       0
  4635.3     .07       0  4964.5    .045       0  5000.4     .07       0
  5257.9     .07       0  5474.3    .035       0  5585.6     .07       0
  6378.1    .035       0  6519.7     .07       0
Bank Sta=4964.5,5000.4
XS Rating Curve= 0 ,0
Exp/Cntr=0.3,0.1

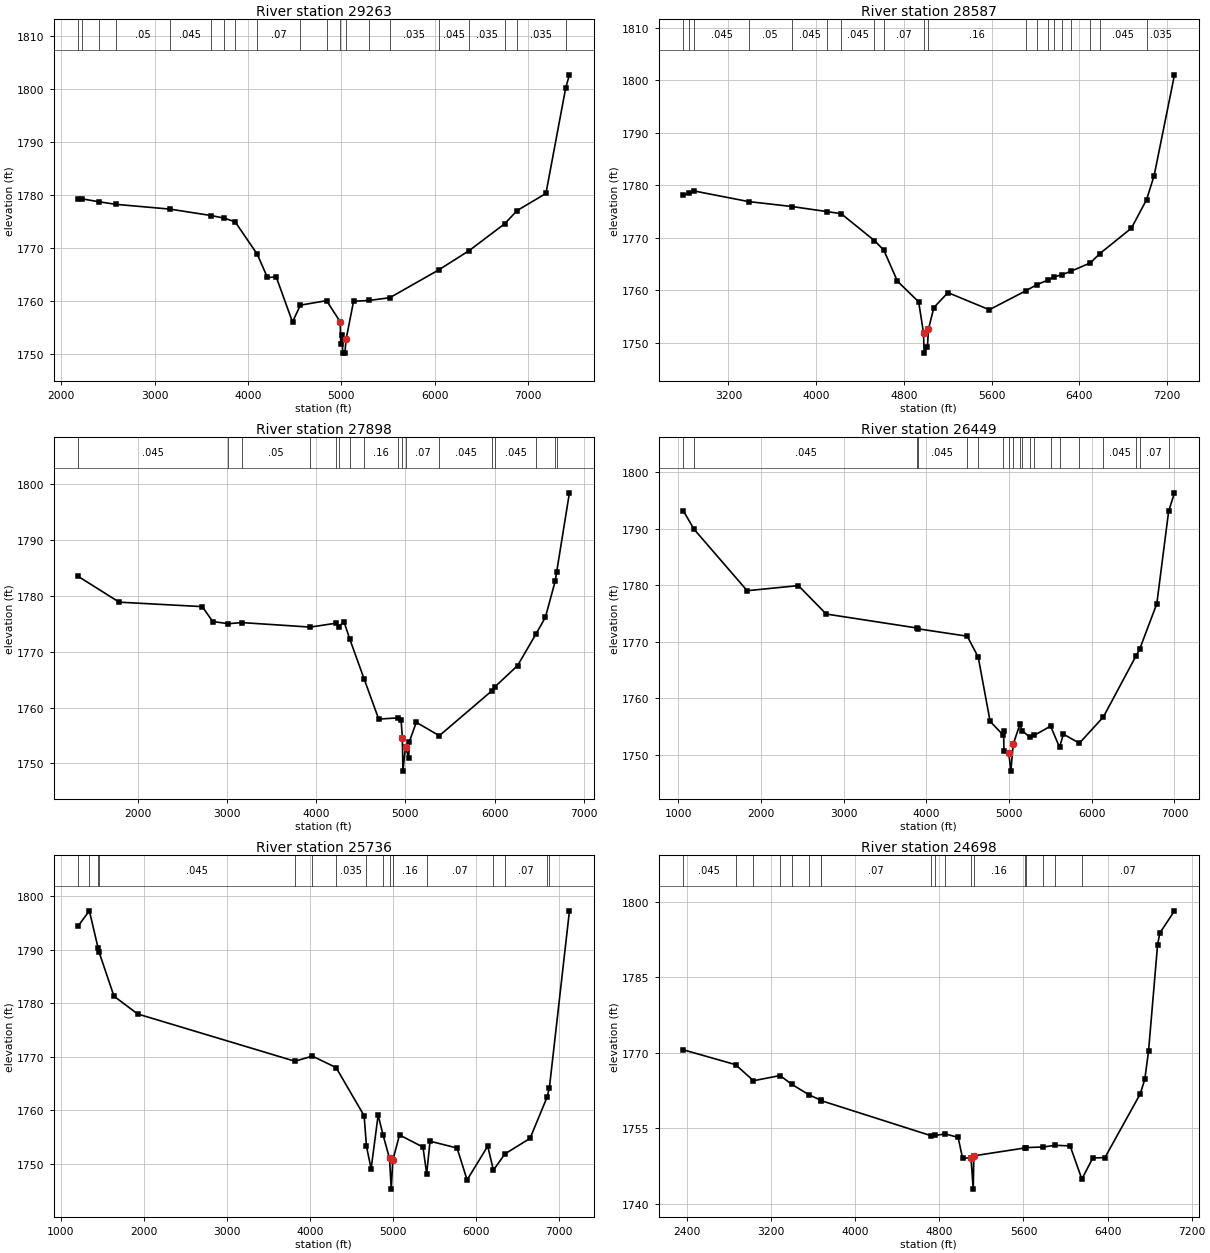
Type RM Length L Ch R = 1 ,29263   ,676,676,676
BEGIN DESCRIPTION:
Noodle Creek 20.0
END DESCRIPTION:
XS GIS Cut Line= 3
      1489898.87      6915809.53        1492305.        6914338.
      1494305.04      6912937.97
#Sta/Elev= 30
  2180.2 1779.24  2222.7 1779.25  2402.3 1778.71  2581.9 1778.22  3161.9 1777.32
  3604.3  1776.1  3747.5  1775.6  3862.4  1774.9  4099.4 1768.77  4207.3 1764.39
  4302.1 1764.48  4476.3 1755.96  4560.4 1759.15  4841.3    1760  4987.1    1756
  4992.9 1751.84  5008.1 1753.49  5014.2 1750.14  5037.3 1750.08  5049.9 1752.67
  5130.1 1759.88  5300.7 1760.05  5518.3 1760.56  6041.6 1765.81  6369.1 1769.48
  6748.4 1774.54    6881 1777.03  7190.4 1780.28  7402.7 1800.29    7442 1802.71
#Mann= 20 ,-1 , 0
  2180.2    .045       0  2222.7    .035       0  2402.3    .045       0
  2581.9     .05       0  3161.9    .045       0  3604.3     .05       0
  3747.5    .045       0  3862.4    .035       0  4099.4     .07       0
  4560.4     .07       0  4841.3     .07       0  4987.1    .045       0
  5049.9     .07       0  5300.7    .035       0  5518.3    .035       0
  6041.6    .045       0  6369.1    .035       0  6748.4    .045       0
    6881    .035       0  7402.7     .07       0
Bank Sta=4987.1,5049.9
XS Rating Curve= 0 ,0
Exp/Cntr=0.3,0.1

Type RM Length L Ch R = 1 ,28587   ,689,689,689
BEGIN DESCRIPTION:
Noodle Creek 19.0
END DESCRIPTION:
XS GIS Cut Line= 3
      1490303.38      6915852.94        1492255.        6914838.
      1494054.99        6913438.
#Sta/Elev= 30
  2787.5 1778.11  2837.5 1778.47  2889.4 1778.91  3383.8  1776.9  3778.6 1775.96
  4103.3 1774.98  4227.7  1774.6  4531.8 1769.47  4617.2 1767.65  4741.5 1761.74
  4934.8 1757.81    4979 1751.92  4984.4 1748.05  5015.3 1749.23  5023.5 1752.55
  5073.2 1756.72  5201.7 1759.57  5579.1 1756.31  5914.6 1759.95  6011.9 1761.07
  6115.4 1761.98    6166 1762.51  6243.7 1763.01    6320  1763.6  6500.2 1765.23
  6587.2    1767  6874.9 1771.84  7013.3 1777.28  7082.1 1781.86  7267.6 1801.03
#Mann= 20 ,-1 , 0
  2787.5    .045       0  2837.5    .035       0  2889.4    .045       0
  3383.8     .05       0  3778.6    .045       0  4103.3     .05       0
  4227.7    .045       0  4531.8    .035       0  4617.2     .07       0
    4979    .045       0  5023.5     .16       0  5914.6    .045       0
  6011.9    .035       0  6115.4    .045       0    6166    .035       0
  6243.7    .045       0    6320    .035       0  6500.2    .035       0
  6587.2    .045       0  7013.3    .035       0
Bank Sta=4979,5023.5
XS Rating Curve= 0 ,0
Exp/Cntr=0.3,0.1

Type RM Length L Ch R = 1 ,27898   ,1449,1449,1449
BEGIN DESCRIPTION:
Noodle Creek 18.0
END DESCRIPTION:
XS GIS Cut Line= 3
      1489854.96      6917038.03        1492855.        6914938.
      1494054.99      6913538.01
#Sta/Elev= 30
  1333.5 1783.52  1793.5 1778.89  2725.5 1778.09  2841.5 1775.42  3017.1 1775.03
    3168 1775.23  3936.1 1774.42  4219.4 1775.11  4257.3 1774.51  4312.4 1775.41
  4378.8 1772.23  4537.9 1765.16  4702.1 1757.93  4914.4 1758.14  4952.4 1757.83
  4967.2  1754.6  4973.3  1748.6  5002.6 1752.98  5037.8 1750.96  5045.4 1753.89
  5123.4 1757.35  5381.4 1754.95  5973.5 1763.04  6008.3 1763.77  6258.3 1767.52
  6465.4 1773.21    6570 1776.17  6680.3 1782.69    6697 1784.36  6839.4 1798.49
#Mann= 17 ,-1 , 0
  1333.5    .045       0  3017.1    .035       0    3168     .05       0
  3936.1    .045       0  4219.4     .07       0  4257.3    .035       0
  4378.8     .07       0  4537.9     .16       0  4914.4     .07       0
  4967.2    .045       0  5002.6     .07       0  5381.4    .045       0
  5973.5     .07       0  6008.3    .045       0  6465.4    .035       0
  6680.3     .07       0    6697    .035       0
Bank Sta=4967.2,5002.6
XS Rating Curve= 0 ,0
Exp/Cntr=0.3,0.1

Type RM Length L Ch R = 1 ,26449   ,713,713,713
BEGIN DESCRIPTION:
Noodle Creek 17.0
END DESCRIPTION:
XS GIS Cut Line= 3
      1489604.96      6917388.02        1493205.        6915788.
      1494405.01      6914187.99
#Sta/Elev= 30
  1060.4  1793.2  1191.8  1789.9    1834 1779.04  2453.6 1779.94  2789.5 1774.92
  3887.1 1772.45  3894.7 1772.32  4494.6    1771  4627.3 1767.31  4770.9 1755.97
  4922.8 1753.63  4933.6 1754.19  4939.1 1750.72  4997.3 1750.35  5021.9 1747.17
    5050 1751.92  5130.9 1755.41  5159.3 1754.32  5250.8 1753.16  5302.1 1753.47
  5502.3 1755.12  5610.5 1751.38  5657.3 1753.71  5850.3  1752.1  6140.8 1756.75
  6531.4 1767.43  6577.6 1768.66  6786.4 1776.75  6929.4 1793.08    7000 1796.33
#Mann= 20 ,-1 , 0
  1060.4     .07       0  1191.8    .045       0  3887.1    .035       0
  3894.7    .045       0  4494.6    .035       0  4627.3     .07       0
  4922.8     .16       0  4997.3    .045       0    5050     .16       0
  5130.9     .07       0  5159.3    .035       0  5250.8     .07       0
  5302.1    .035       0  5502.3     .07       0  5610.5    .035       0
  5850.3    .035       0  6140.8    .045       0  6531.4    .035       0
  6577.6     .07       0  6929.4    .035       0
Bank Sta=4997.3,5050
XS Rating Curve= 0 ,0
Exp/Cntr=0.3,0.1

Type RM Length L Ch R = 1 ,25736   ,1038,1038,1038
BEGIN DESCRIPTION:
Noodle Creek 16.0
END DESCRIPTION:
XS GIS Cut Line= 3
      1489854.97      6917438.01        1493455.        6916238.
      1494855.01      6914637.99
#Sta/Elev= 30
  1209.1  1794.4  1344.8 1797.24  1450.2 1790.26  1462.2 1789.51  1641.3 1781.28
  1925.9 1777.96  3821.6 1769.12  4031.6 1770.08  4317.7 1767.94    4656 1758.92
    4684 1753.21  4740.3 1749.03  4824.7 1759.04  4884.8 1755.29  4961.7 1750.96
  4982.8 1745.21  5001.2 1750.59  5082.2 1755.34    5365 1753.07  5409.6 1748.09
  5450.4 1754.17    5776 1752.89  5896.5 1746.93  6145.2 1753.24    6214 1748.76
  6352.6  1751.8  6654.9 1754.69  6860.9 1762.41  6888.3 1764.15  7129.9  1797.2
#Mann= 16 ,-1 , 0
  1209.1     .07       0  1344.8     .16       0  1450.2     .07       0
  1462.2    .045       0  3821.6    .035       0  4031.6     .07       0
  4317.7    .035       0    4684     .07       0  4884.8     .16       0
  4961.7    .045       0  5001.2     .16       0  5409.6     .07       0
    6214     .16       0  6352.6     .07       0  6860.9    .035       0
  6888.3     .07       0
Bank Sta=4961.7,5001.2
XS Rating Curve= 0 ,0
Exp/Cntr=0.3,0.1

Type RM Length L Ch R = 1 ,24698   ,4292,4292,4292
BEGIN DESCRIPTION:
Mapping XS e2911bd1
END DESCRIPTION:
XS GIS Cut Line= 4
      1491735.65      6917493.57      1493808.57      6916738.36
      1494777.32      6915316.49      1495214.55       6914712.7
#Sta/Elev= 30
  2364.1 1770.59  2862.2 1767.63  3032.7 1764.43  3285.7 1765.46  3397.3 1763.71
  3565.2 1761.58  3671.7 1760.57  3674.4 1760.48  4718.5 1753.51    4760 1753.55
  4856.8 1753.84  4978.7 1753.16  5020.7 1749.05  5101.4 1749.04  5122.4 1742.86
  5128.4 1749.49  5610.1 1751.04  5620.5 1751.13  5787.4 1751.24  5901.1 1751.58
  6043.9 1751.46  6155.4 1744.85  6259.4 1749.06  6374.9 1749.13  6709.8 1761.78
  6753.9  1764.7  6789.4  1770.3  6875.3 1791.42  6896.1  1793.8  7036.3 1798.24
#Mann= 18 ,-1 , 0
  2364.1    .045       0  2862.2    .035       0  3032.7     .07       0
  3285.7    .035       0  3397.3     .07       0  3565.2    .035       0
  3671.7     .16       0  3674.4     .07       0  4718.5    .035       0
    4760     .07       0  4856.8     .16       0  5101.4    .045       0
  5128.4     .16       0  5610.1     .07       0  5620.5     .16       0
  5787.4     .07       0  5901.1     .16       0  6155.4     .07       0
Bank Sta=5101.4,5128.4
XS Rating Curve= 0 ,0
Exp/Cntr=0.3,0.1

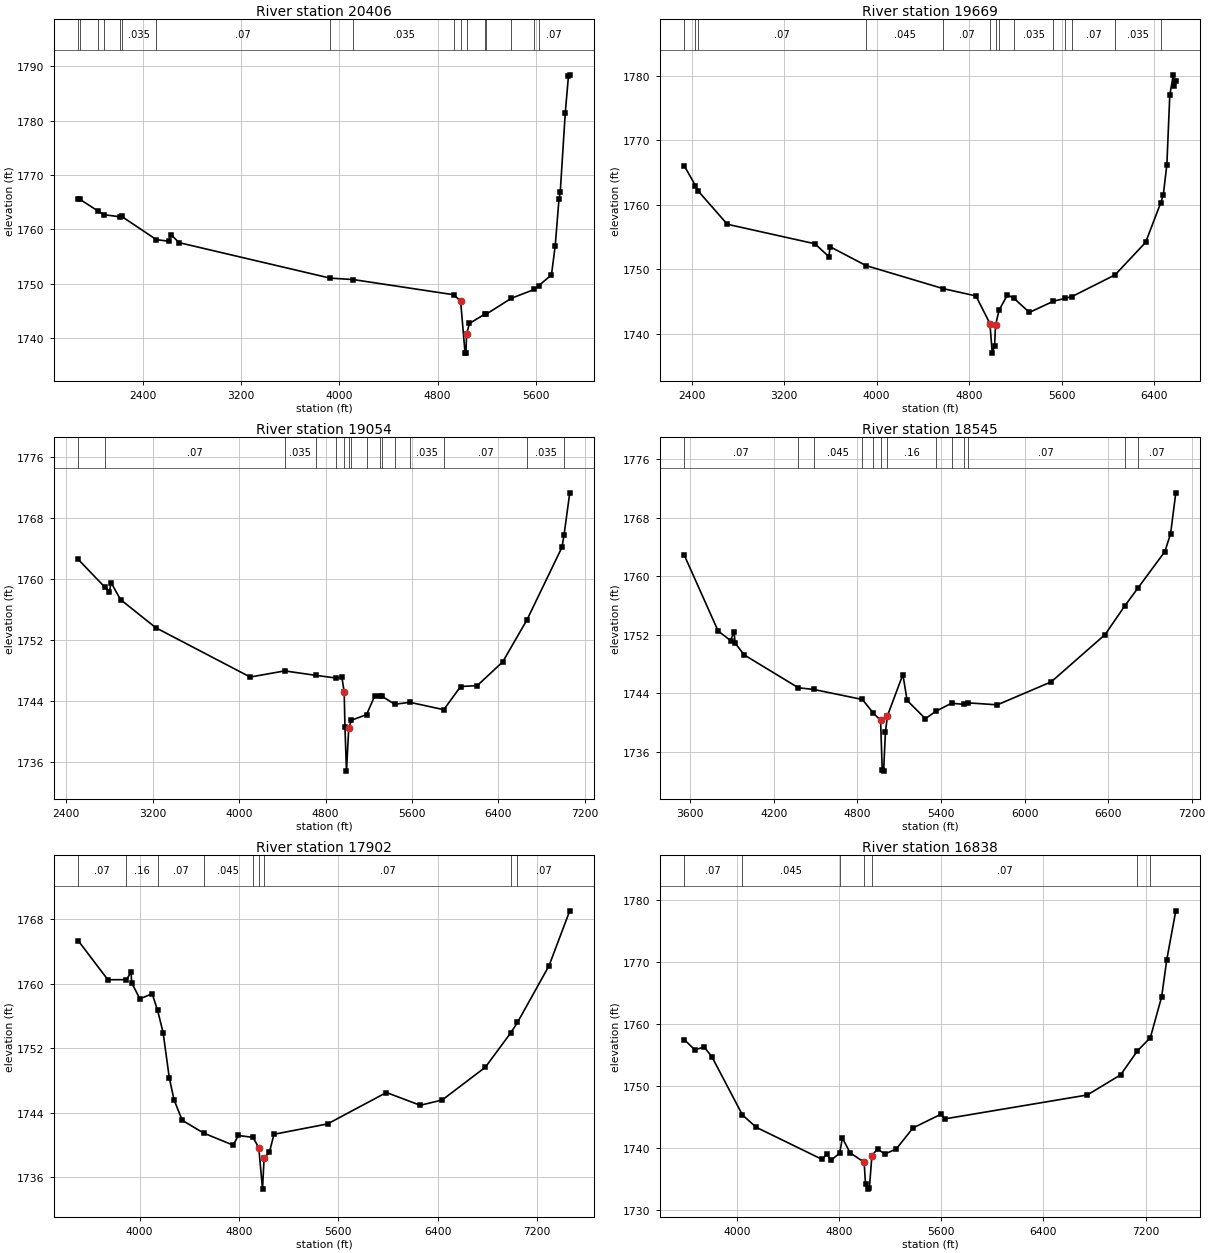
Type RM Length L Ch R = 1 ,20406   ,737,737,737
BEGIN DESCRIPTION:
Mapping XS a5660a28
END DESCRIPTION:
XS GIS Cut Line= 4
      1492558.61      6917592.51      1494751.28       6916759.2
      1495824.19       6916071.7      1495902.21      6915702.41
#Sta/Elev= 30
  1876.5  1765.5  1891.2  1765.5  2039.1 1763.34  2084.2 1762.69    2219 1762.28
  2229.6 1762.38  2512.6 1758.09  2611.6  1757.8    2631 1759.03  2696.6 1757.54
  3924.9 1751.01  4114.4 1750.74  4933.1 1747.94  4986.7 1746.73  5022.3 1737.31
  5029.5 1737.21  5035.4 1740.75    5058 1742.67  5184.6  1744.4  5193.3 1744.36
  5398.6 1747.29  5586.8 1748.94  5621.6 1749.63  5725.1 1751.59  5755.8 1756.98
  5786.4 1765.56  5796.6 1766.85  5837.5 1781.44  5863.1 1788.12  5873.9 1788.41
#Mann= 17 ,-1 , 0
  1876.5     .07       0  1891.2    .035       0  2039.1     .07       0
  2084.2    .035       0    2219     .07       0  2229.6    .035       0
  2512.6     .07       0  3924.9    .045       0  4114.4    .035       0
  4933.1     .07       0  4986.7    .045       0  5035.4     .07       0
  5184.6     .07       0  5193.3    .035       0  5398.6     .07       0
  5586.8    .035       0  5621.6     .07       0
Bank Sta=4986.7,5035.4
XS Rating Curve= 0 ,0
Exp/Cntr=0.3,0.1

Type RM Length L Ch R = 1 ,19669   ,615,615,615
BEGIN DESCRIPTION:
Mapping XS 100c25b2
END DESCRIPTION:
XS GIS Cut Line= 4
      1493100.25      6917587.31      1494074.19      6917144.61
      1496157.53      6916858.15      1496527.24      6915842.73
#Sta/Elev= 30
  2334.5  1766.1  2432.2    1763  2455.3 1762.17  2707.6    1757  3465.7 1753.97
  3586.8 1751.97  3596.9 1753.51  3907.5 1750.59  4577.1    1747  4858.7 1745.88
  4979.8 1741.59    5000    1737  5020.2 1738.14  5028.2 1741.32  5059.7 1743.69
  5131.2 1746.04  5186.7 1745.52  5321.4 1743.32  5527.7 1745.04  5630.9 1745.51
  5689.9 1745.78  6062.3 1749.14  6326.9 1754.19  6458.5 1760.37  6480.1 1761.59
  6510.7 1766.27    6536 1777.04  6566.5 1780.19  6571.9 1778.38  6587.9 1779.28
#Mann= 14 ,-1 , 0
  2334.5     .07       0  2432.2    .035       0  2455.3     .07       0
  3907.5    .045       0  4577.1     .07       0  4979.8    .045       0
  5028.2     .07       0  5059.7     .07       0  5186.7    .035       0
  5527.7     .07       0  5630.9     .16       0  5689.9     .07       0
  6062.3    .035       0  6458.5     .07       0
Bank Sta=4979.8,5028.2
XS Rating Curve= 0 ,0
Exp/Cntr=0.3,0.1

Type RM Length L Ch R = 1 ,19054   ,509,509,509
BEGIN DESCRIPTION:
Mapping XS e3ff1100
END DESCRIPTION:
XS GIS Cut Line= 4
      1493621.05        6918879.      1495157.53      6918035.24
      1496324.19      6916936.28      1496746.07      6915816.48
#Sta/Elev= 30
  2508.4  1762.6  2753.9 1758.97  2798.1 1758.33  2813.5 1759.54  2900.8 1757.32
  3226.6 1753.63  4102.1 1747.15  4420.7 1747.96  4711.5 1747.37  4899.6 1747.02
  4950.8 1747.14  4972.2 1745.16  4979.1  1740.6  4993.3 1734.81  5014.3 1740.49
  5039.4 1741.49  5179.1 1742.22  5255.1 1744.69  5302.2 1744.64  5318.9 1744.65
  5440.9 1743.58  5579.7 1743.84  5894.3 1742.87    6050 1745.91  6204.2 1746.03
  6439.3 1749.13  6665.1 1754.67  6988.2 1764.17  7007.5 1765.76  7060.7 1771.32
#Mann= 16 ,-1 , 0
  2508.4    .035       0  2753.9     .07       0  4420.7    .035       0
  4711.5    .045       0  4899.6     .07       0  4972.2    .045       0
  5014.3     .07       0  5039.4    .045       0  5179.1     .16       0
  5302.2     .07       0  5318.9     .16       0  5440.9     .07       0
  5579.7    .035       0  5894.3     .07       0  6665.1    .035       0
  7007.5     .07       0
Bank Sta=4972.2,5014.3
XS Rating Curve= 0 ,0
Exp/Cntr=0.3,0.1

Type RM Length L Ch R = 1 ,18545   ,643,643,643
BEGIN DESCRIPTION:
Mapping XS df10fb6c
END DESCRIPTION:
XS GIS Cut Line= 4
      1495496.08      6919071.66      1495688.78      6918415.45
      1496470.03      6916988.36      1496823.99      6915822.36
#Sta/Elev= 30
  3556.4 1762.93  3799.9 1752.54  3889.1 1751.23  3914.6 1752.42  3922.5 1750.86
  3987.5 1749.26  4376.5 1744.77  4486.4 1744.54    4836 1743.17    4913 1741.34
  4966.5 1740.32  4978.4 1733.47  4988.3 1733.38  5001.2 1738.71  5015.9 1740.95
  5126.6 1746.58  5157.1 1743.04    5288 1740.55    5366 1741.59    5476 1742.66
  5565.4  1742.5  5592.8 1742.71  5804.8 1742.44  6191.6 1745.58  6578.3 1752.04
  6718.6 1755.93  6813.3 1758.38  7007.6 1763.39  7048.6 1765.84  7085.8 1771.41
#Mann= 13 ,-1 , 0
  3556.4     .07       0  4376.5    .035       0  4486.4    .045       0
    4836     .07       0    4913     .16       0  4966.5    .045       0
  5015.9     .16       0    5366     .16       0    5476     .07       0
  5565.4     .16       0  5592.8     .07       0  6718.6    .035       0
  6813.3     .07       0
Bank Sta=4966.5,5015.9
XS Rating Curve= 0 ,0
Exp/Cntr=0.3,0.1

Type RM Length L Ch R = 1 ,17902   ,1064,1064,1064
BEGIN DESCRIPTION:
Mapping XS 14f9a066
END DESCRIPTION:
XS GIS Cut Line= 4
      1495818.98      6919556.08      1496272.11       6918701.9
      1496621.07      6917181.07      1496928.35      6915785.28
#Sta/Elev= 30
  3505.5 1765.33  3744.6 1760.48  3894.2 1760.49  3931.1  1761.4  3936.8 1760.09
  4002.8 1758.11  4101.4 1758.75  4144.9  1756.7  4189.4 1753.94  4239.1 1748.35
  4277.3 1745.62  4343.3 1743.08  4515.5  1741.5  4753.5    1740  4794.5  1741.2
  4911.7 1740.97  4959.3 1739.71  4989.4 1734.56  5002.2  1738.4  5045.1 1739.14
  5081.8 1741.35  5512.7 1742.63  5986.5 1746.52  6258.2 1744.94  6435.3 1745.59
  6783.4 1749.66  6987.3 1753.91  7041.2 1755.19  7295.4 1762.22    7462 1769.01
#Mann= 9 ,-1 , 0
  3505.5     .07       0  3894.2     .16       0  4144.9     .07       0
  4515.5    .045       0  4911.7     .07       0  4959.3    .045       0
  5002.2     .07       0  6987.3    .035       0  7041.2     .07       0
Bank Sta=4959.3,5002.2
XS Rating Curve= 0 ,0
Exp/Cntr=0.3,0.1

Type RM Length L Ch R = 1 ,16838   ,549,549,549
BEGIN DESCRIPTION:
Mapping XS f2a444f7
END DESCRIPTION:
XS GIS Cut Line= 4
      1496834.61      6919670.66      1496985.65      6918931.07
      1496871.07      6917785.24      1497058.56      6915847.79
#Sta/Elev= 30
  3584.1 1757.55  3668.5 1755.87  3739.9 1756.36  3801.1 1754.78  4040.6  1745.4
  4148.2 1743.41  4663.6 1738.24  4703.8 1739.09    4734 1738.06  4802.5 1739.23
  4824.4 1741.67  4884.7 1739.28  4994.5 1737.77  5005.3 1734.24  5025.4 1733.43
  5035.5 1733.55  5055.6 1738.85    5100 1739.91  5156.1 1739.08  5246.5 1739.91
  5377.2 1743.29  5598.2 1745.52  5628.4 1744.76  6743.6 1748.61  7004.8 1751.86
  7136.8 1755.73  7237.6 1757.85  7326.3 1764.45  7366.5 1770.44    7437  1778.3
#Mann= 7 ,-1 , 0
  3584.1     .07       0  4040.6    .045       0  4802.5     .07       0
  4994.5    .045       0  5055.6     .07       0  7136.8    .035       0
  7237.6     .07       0
Bank Sta=4994.5,5055.6
XS Rating Curve= 0 ,0
Exp/Cntr=0.3,0.1

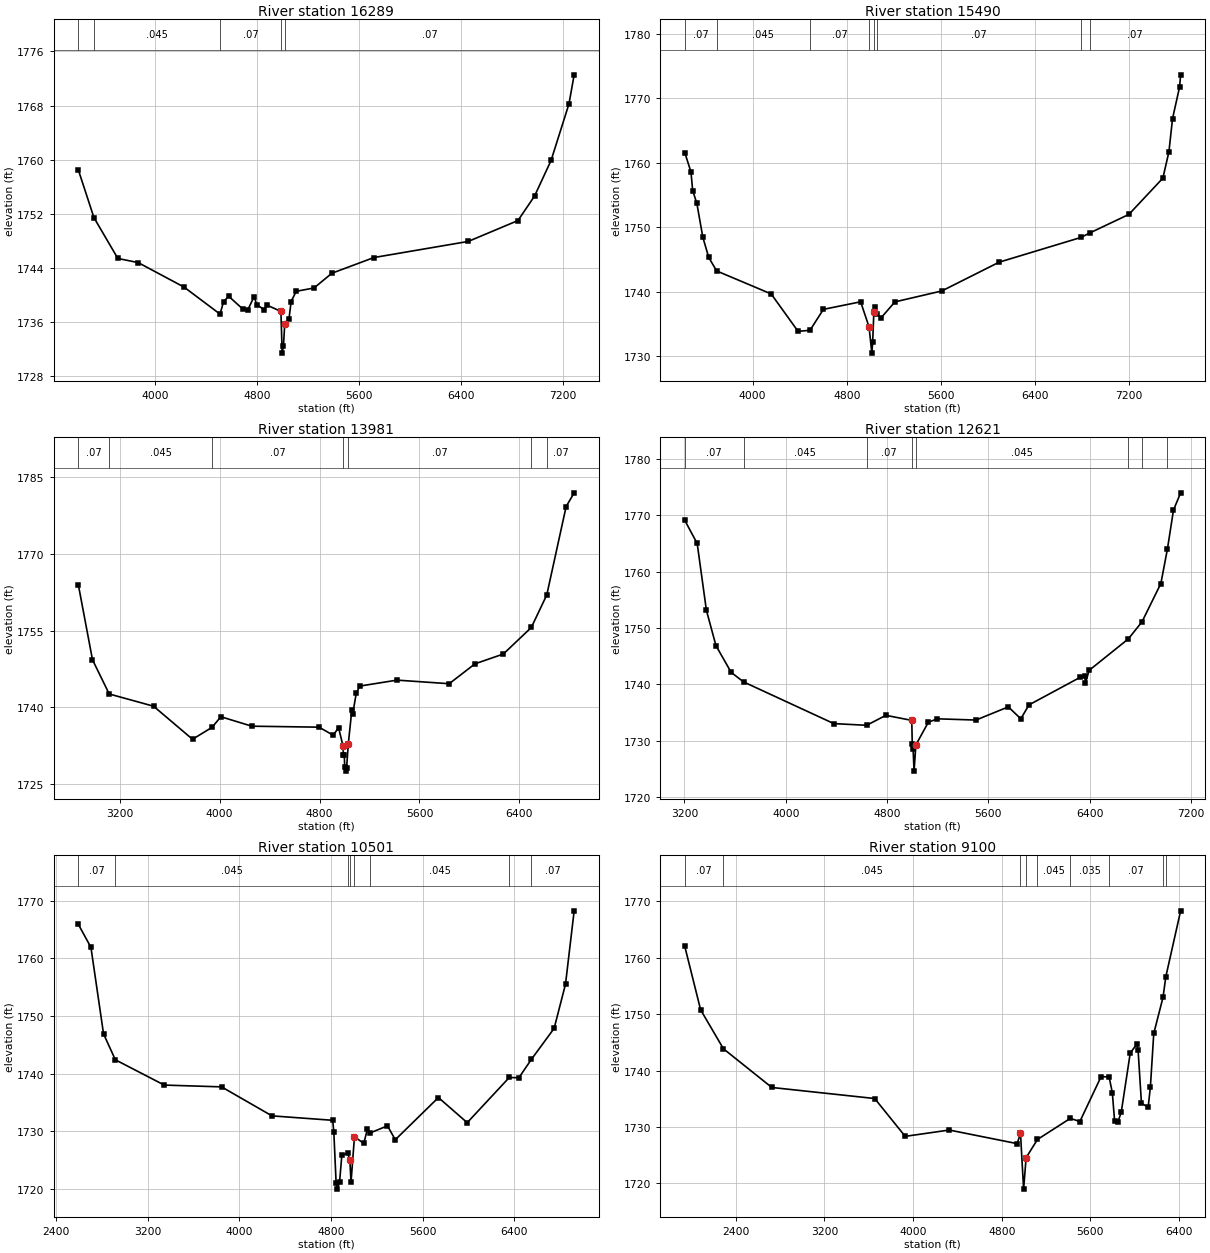
Type RM Length L Ch R = 1 ,16289   ,799,799,799
BEGIN DESCRIPTION:
Mapping XS bc456ef1
END DESCRIPTION:
XS GIS Cut Line= 4
      1497345.03      6919727.91      1497345.03      6918707.11
       1497329.4      6916743.57      1497292.94      6915837.31
#Sta/Elev= 30
  3394.6 1758.49  3517.1 1751.43  3704.5  1745.4  3864.5 1744.78  4224.5 1741.16
  4506.6 1737.17  4534.5    1739  4574.5 1739.81  4684.5 1737.93  4724.5  1737.8
  4774.5 1739.77  4794.5 1738.55  4854.5 1737.83  4874.5  1738.5  4984.5 1737.57
  4994.5  1731.4  5004.5 1732.45  5014.5 1735.73  5048.3 1736.51  5064.5 1739.02
  5104.5 1740.54  5244.5 1741.03  5384.5 1743.21  5714.6 1745.53  6454.6 1747.91
    6845    1751  6975.1 1754.62  7105.2  1759.9  7245.3 1768.25    7286 1772.54
#Mann= 5 ,-1 , 0
  3394.6     .07       0  3517.1    .045       0  4506.6     .07       0
  4984.5    .045       0  5014.5     .07       0
Bank Sta=4984.5,5014.5
XS Rating Curve= 0 ,0
Exp/Cntr=0.3,0.1

Type RM Length L Ch R = 1 ,15490   ,1509,1509,1509
BEGIN DESCRIPTION:
Mapping XS a9026387
END DESCRIPTION:
XS GIS Cut Line= 4
      1497480.45      6919696.68      1498126.28      6918795.65
      1497881.48      6917602.95      1497428.78      6915771.31
#Sta/Elev= 30
    3424 1761.56  3476.2 1758.59    3491  1755.7  3526.6 1753.69  3576.9 1748.49
  3627.3 1745.33  3694.9 1743.24  4157.9 1739.68  4386.3 1733.89  4487.6 1734.04
  4601.6 1737.29  4918.1 1738.46  4989.6 1734.56  5013.3 1730.51  5020.2 1732.17
  5030.4 1736.86  5040.6 1737.64  5053.3  1736.6  5091.6 1735.98  5209.7 1738.45
  5607.7 1740.14  6095.2  1744.6    6790 1748.43  6863.4 1749.11  7197.4    1752
  7485.8 1757.61  7537.3 1761.68  7568.2 1766.84  7628.3 1771.76  7636.9 1773.62
#Mann= 8 ,-1 , 0
    3424     .07       0  3694.9    .045       0  4487.6     .07       0
  4989.6    .045       0  5030.4     .07       0  5053.3     .07       0
    6790    .035       0  6863.4     .07       0
Bank Sta=4989.6,5030.4
XS Rating Curve= 0 ,0
Exp/Cntr=0.3,0.1

Type RM Length L Ch R = 1 ,13981   ,1360,1360,1360
BEGIN DESCRIPTION:
Noodle Creek 9.0
END DESCRIPTION:
XS GIS Cut Line= 3
      1497555.03      6919687.96        1498955.        6918088.
      1500355.01      6916887.99
#Sta/Elev= 30
  2868.8    1764  2982.2 1749.32  3116.1 1742.63    3471 1740.24  3783.2 1733.77
  3939.5 1736.11  4010.1 1738.18  4257.8 1736.33  4795.9 1736.14  4909.8 1734.56
  4952.5 1736.04  4987.7  1732.5  4991.5 1730.65  4998.1 1730.65  5001.9 1728.25
  5008.5 1727.54  5016.2 1728.07  5030.5 1732.91    5059 1739.59  5065.6 1738.73
  5094.1 1742.79  5122.6 1744.18  5420.1 1745.34  5838.3 1744.64  6044.6 1748.53
  6271.8 1750.45  6495.6 1755.64  6619.4    1762  6774.5  1779.3  6838.7 1781.98
#Mann= 7 ,-1 , 0
  2868.8     .07       0  3116.1    .045       0  3939.5     .07       0
  4987.7    .045       0  5030.5     .07       0  6495.6     .16       0
  6619.4     .07       0
Bank Sta=4987.7,5030.5
XS Rating Curve= 0 ,0
Exp/Cntr=0.3,0.1

Type RM Length L Ch R = 1 ,12621   ,2120,2120,2120
BEGIN DESCRIPTION:
Noodle Creek 8.0
END DESCRIPTION:
XS GIS Cut Line= 3
      1497605.04      6919837.98        1499205.        6919038.
      1500604.98      6917438.03
#Sta/Elev= 30
  3203.2 1769.11    3301 1765.02  3373.7 1753.17  3449.1  1746.9  3569.3 1742.15
  3666.9 1740.46  4379.9 1733.06  4639.1 1732.76  4790.8 1734.53  4995.3 1733.63
  4999.1 1729.41  5005.8 1728.54  5013.4 1724.63  5027.6 1729.28  5126.3 1733.31
  5197.5 1733.91  5502.2 1733.69  5757.5 1736.03  5856.2 1733.91  5920.7 1736.38
  6324.1 1741.26  6360.2 1741.51  6366.8 1740.26  6395.3  1742.5  6705.2 1748.09
  6812.8 1751.11  6961.9 1757.91    7014 1764.06  7061.6 1770.94    7118    1774
#Mann= 8 ,-1 , 0
  3203.2     .07       0  3666.9    .045       0  4639.1     .07       0
  4995.3    .045       0  5027.6    .045       0  6705.2     .16       0
  6812.8     .07       0    7014    .035       0
Bank Sta=4995.3,5027.6
XS Rating Curve= 0 ,0
Exp/Cntr=0.3,0.1

Type RM Length L Ch R = 1 ,10501   ,1401,1401,1401
BEGIN DESCRIPTION:
Noodle Creek 7.0
END DESCRIPTION:
XS GIS Cut Line= 3
      1497654.99        6919888.        1500055.        6919888.
      1501949.17      6919530.03
#Sta/Elev= 30
  2595.2  1765.9  2705.2  1761.9  2815.2  1746.9  2918.2  1742.4  3345.2 1738.01
  3845.2  1737.7  4285.2 1732.67  4815.2  1731.9  4825.2 1729.89  4845.2 1721.01
  4855.2 1719.96  4875.2 1721.16  4895.2 1725.83  4946.1 1726.21  4965.2    1725
  4975.2 1721.11  5005.4 1729.05  5086.8 1727.88  5117.3 1730.31  5144.6 1729.73
  5293.4 1730.94  5361.6 1728.53  5738.1 1735.85  5989.5 1731.49  6356.7 1739.33
  6440.3 1739.28  6549.2 1742.46  6748.1 1747.85  6847.4 1755.52  6922.9 1768.24
#Mann= 8 ,-1 , 0
  2595.2     .07       0  2918.2    .045       0  4946.1     .07       0
  4965.2    .045       0  5005.4     .07       0  5144.6    .045       0
  6356.7    .035       0  6549.2     .07       0
Bank Sta=4965.2,5005.4
XS Rating Curve= 0 ,0
Exp/Cntr=0.3,0.1

Type RM Length L Ch R = 1 ,9100    ,2108,2108,2108
BEGIN DESCRIPTION:
Noodle Creek 6.0
END DESCRIPTION:
XS GIS Cut Line= 3
      1497655.01        6920288.        1500655.        6920888.
      1502054.99        6921088.
#Sta/Elev= 30
  1940.7 1762.01  2083.5 1750.77  2289.4 1743.86  2725.9    1737    3654 1735.04
  3929.3 1728.33    4327 1729.45  4938.9 1727.04  4969.5 1728.84  4997.6 1718.97
  5020.3 1724.55  5122.9 1727.78  5419.1 1731.52  5505.2 1730.96  5697.1 1738.94
  5769.2 1738.85  5798.1 1736.08  5818.3 1731.13  5848.6 1730.86  5878.9 1732.66
  5959.7  1743.1  6020.4 1744.72  6030.5 1743.62  6060.8 1734.22  6121.4 1733.49
  6141.6 1737.11  6171.9 1746.58  6255.5 1752.99    6281 1756.67  6414.3 1768.33
#Mann= 9 ,-1 , 0
  1940.7     .07       0  2289.4    .045       0  4969.5    .045       0
  5020.3    .045       0  5122.9    .045       0  5419.1    .035       0
  5769.2     .07       0  6255.5    .035       0    6281     .07       0
Bank Sta=4969.5,5020.3
XS Rating Curve= 0 ,0
Exp/Cntr=0.3,0.1