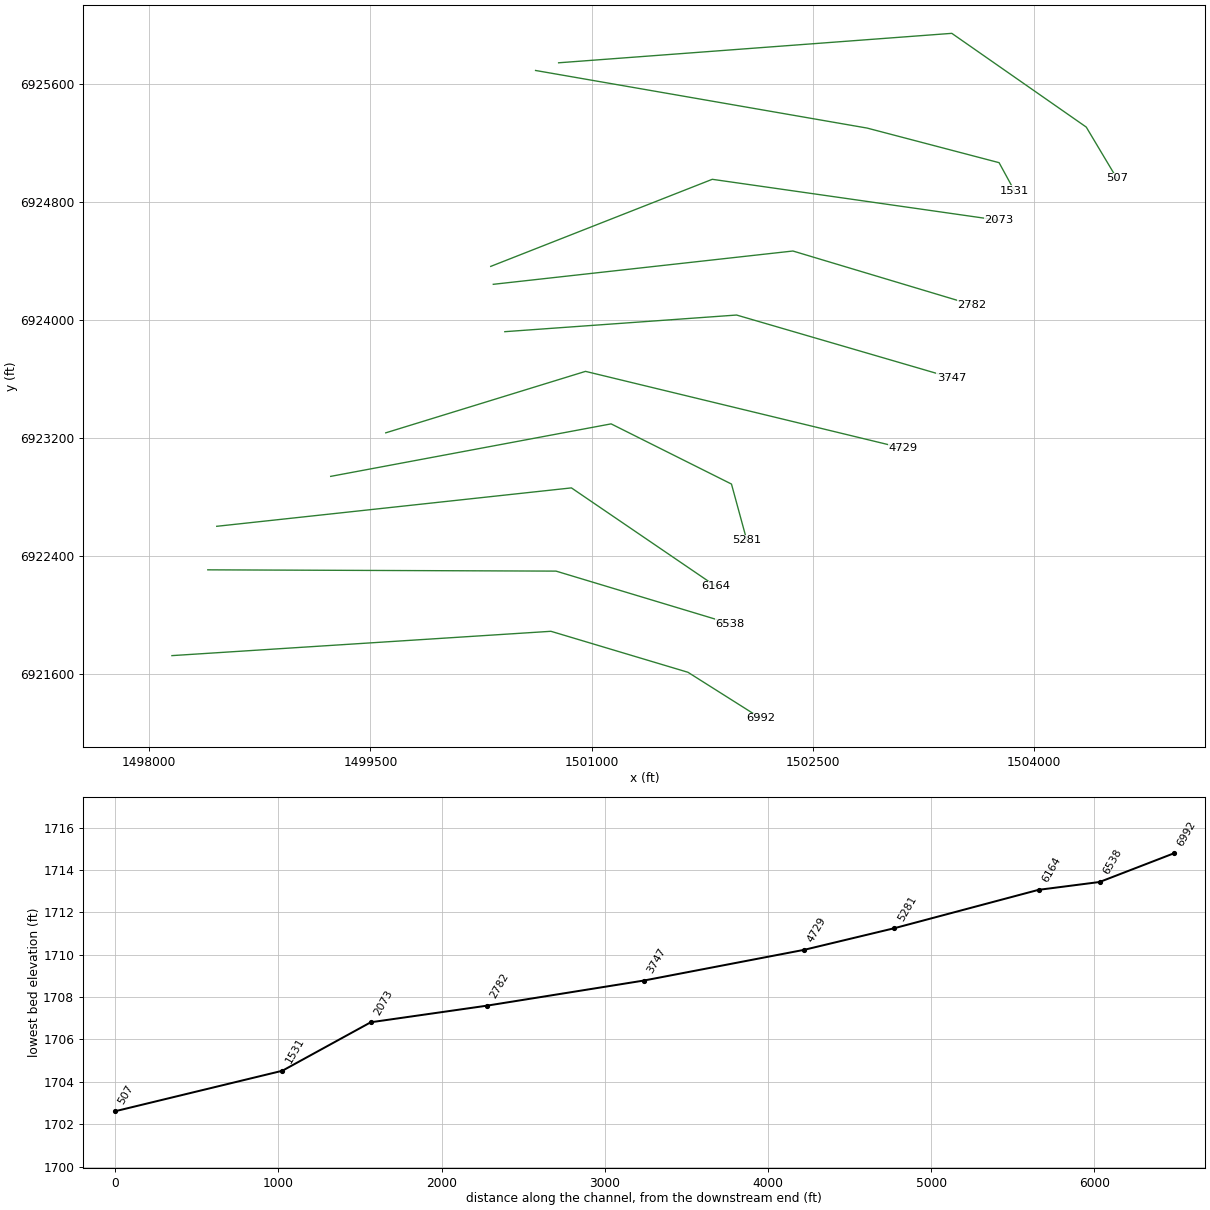
HEC-RAS study Noodle Creek.prj: Noodle Creek Base Level Engineering

--- Noodle Creek.g01 (geometry) --- (continued)

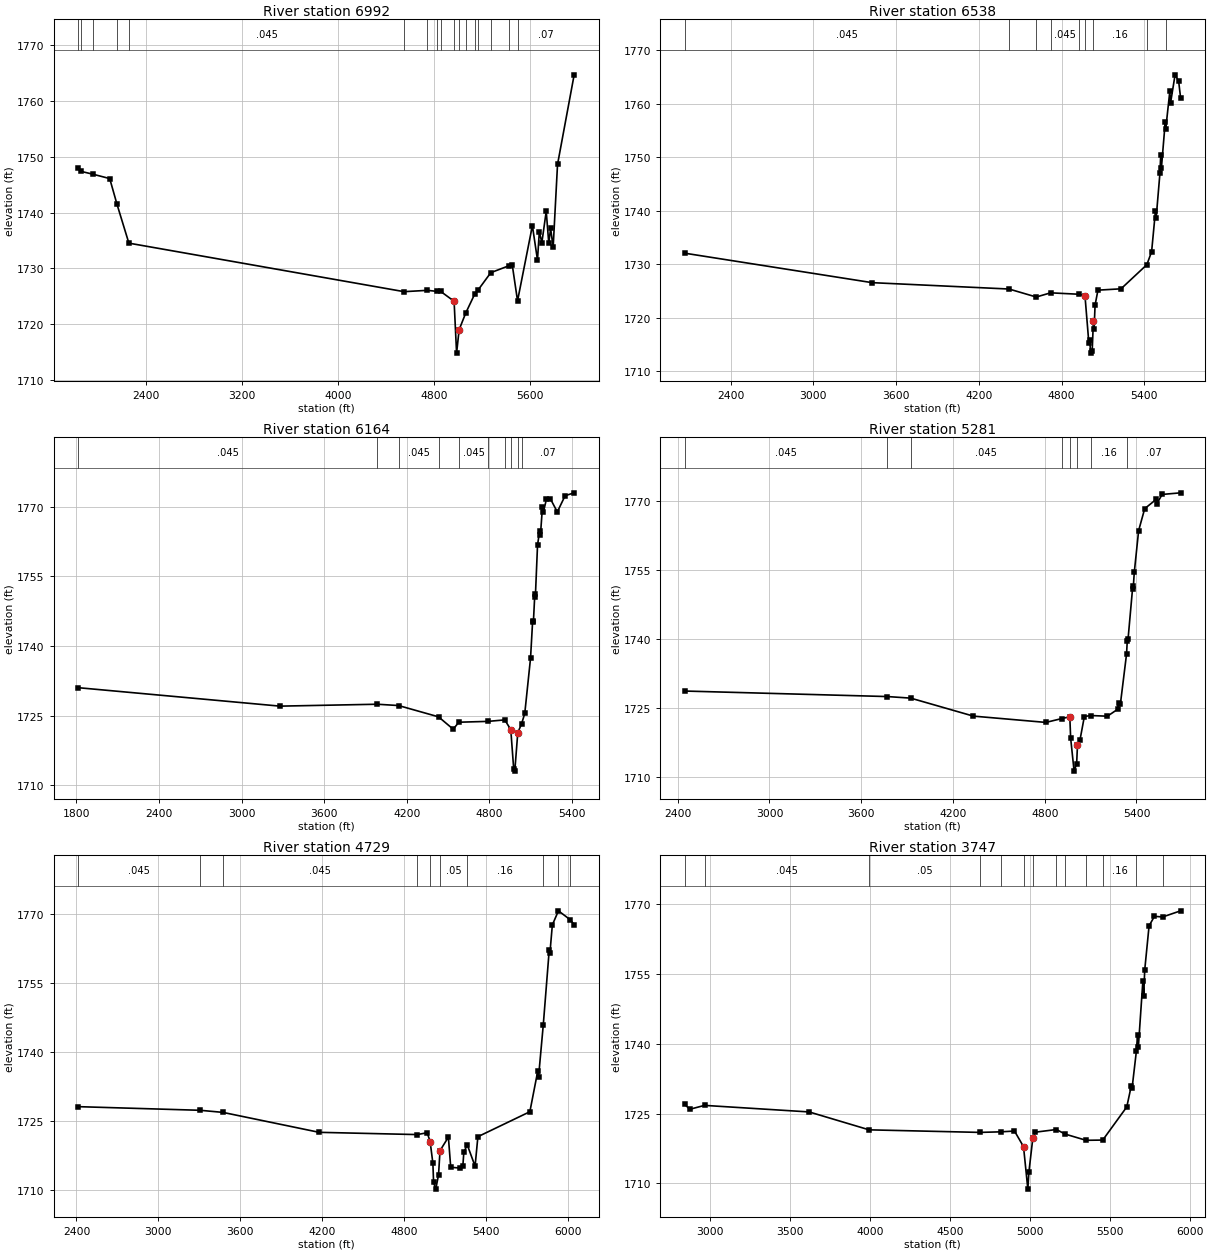
Type RM Length L Ch R = 1 ,6992    ,454,454,454
BEGIN DESCRIPTION:
Mapping XS b5373365
END DESCRIPTION:
XS GIS Cut Line= 4
      1498154.09      6921724.48       1500723.5       6921889.4
      1501652.32      6921611.63      1502147.13      6921299.11
#Sta/Elev= 30
  1836.9 1747.97  1861.6 1747.39  1960.6 1746.88  2098.3 1746.11  2158.7 1741.51
  2257.8 1734.52  4550.1 1725.81  4744.1 1726.05  4824.9 1725.86    4855 1725.85
  4966.4 1724.09  4987.2 1714.78  5008.1 1718.97  5063.5 1721.99  5137.9 1725.37
  5167.8 1726.16    5272 1729.22  5420.2 1730.44  5451.3 1730.53  5494.8 1724.16
  5618.4 1737.66  5660.8 1731.49  5676.1 1736.56  5697.3 1734.62  5733.7 1740.25
  5754.9 1734.51  5770.2 1737.15  5791.4 1733.78  5827.8 1748.64  5966.3 1764.73
#Mann= 17 ,-1 , 0
  1836.9     .07       0  1861.6     .16       0  1960.6    .045       0
  2158.7     .16       0  2257.8    .045       0  4550.1    .035       0
  4744.1    .045       0  4824.9     .07       0    4855    .045       0
  4966.4    .045       0  5008.1    .045       0  5063.5     .16       0
  5137.9     .07       0  5167.8     .16       0    5272     .07       0
  5420.2    .035       0  5494.8     .07       0
Bank Sta=4966.4,5008.1
XS Rating Curve= 0 ,0
Exp/Cntr=0.3,0.1

Type RM Length L Ch R = 1 ,6538    ,374,374,374
BEGIN DESCRIPTION:
Mapping XS dfc739c6
END DESCRIPTION:
XS GIS Cut Line= 3
      1498397.15      6922306.07      1500758.22      6922297.39
      1501938.75       6921941.5
#Sta/Elev= 30
  2068.3 1732.09  3426.2 1726.59  4418.8  1725.4  4615.8 1723.91  4720.1 1724.69
  4928.7 1724.42  4969.3 1724.08  4997.1 1715.35  5002.3 1715.94  5010.9 1713.43
  5021.4 1713.83  5030.1  1719.4  5035.3 1718.01  5042.3  1722.4  5063.1 1725.19
  5230.3 1725.44  5417.4 1729.94  5452.1 1732.37  5479.8 1739.93  5485.1  1738.7
  5512.3 1746.99    5518 1750.37  5523.3 1748.05    5551 1756.66  5554.6 1755.32
    5584 1762.31  5589.2 1760.12  5622.2  1765.4    5648 1764.22  5662.4 1761.05
#Mann= 9 ,-1 , 0
  2068.3    .045       0  4418.8    .035       0  4615.8     .07       0
  4720.1    .045       0  4928.7     .16       0  4969.3    .045       0
  5030.1     .16       0  5417.4     .07       0  5554.6    .035       0
Bank Sta=4969.3,5030.1
XS Rating Curve= 0 ,0
Exp/Cntr=0.3,0.1

Type RM Length L Ch R = 1 ,6164    ,883,883,883
BEGIN DESCRIPTION:
Mapping XS 81af2620
END DESCRIPTION:
XS GIS Cut Line= 3
      1498457.86      6922601.21      1500862.39      6922861.63
      1501841.66      6922194.34
#Sta/Elev= 30
  1813.9 1731.02  3279.6 1727.05    3986 1727.46  4140.9 1727.18  4431.6 1724.75
  4538.2 1722.09  4579.7 1723.59  4791.3 1723.77  4913.5 1724.09  4956.9 1721.98
  4977.9 1713.59  4985.9 1713.06  5007.7 1721.32  5035.7 1723.27  5058.5 1725.48
  5100.5 1737.38  5115.5 1745.26  5121.5 1745.32  5130.4  1750.5  5136.5 1751.28
  5151.4 1761.76  5166.3 1764.66  5172.4 1763.86  5187.3    1770  5193.3 1768.75
  5215.8 1771.57  5244.2 1771.71    5295 1768.86  5351.9 1772.35  5417.5 1772.97
#Mann= 10 ,-1 , 0
  1813.9    .045       0    3986    .035       0  4140.9    .045       0
  4431.6     .07       0  4579.7    .045       0  4791.3     .07       0
  4913.5     .16       0  4956.9    .045       0  5007.7     .16       0
  5035.7     .07       0
Bank Sta=4956.9,5007.7
XS Rating Curve= 0 ,0
Exp/Cntr=0.3,0.1

Type RM Length L Ch R = 1 ,5281    ,552,552,552
BEGIN DESCRIPTION:
Mapping XS d3b6f29f
END DESCRIPTION:
XS GIS Cut Line= 4
      1499230.41      6922939.74      1501131.48      6923295.65
      1501947.46      6922887.67      1502051.63      6922505.71
#Sta/Elev= 30
  2446.4 1728.66  3771.4 1727.46  3923.4 1727.12  4333.2 1723.21  4807.5 1721.84
  4913.3 1722.69    4964 1723.06  4969.6 1718.42    4992 1711.25  5008.7 1712.87
  5014.3  1716.9  5031.1 1718.11  5059.1 1723.11  5099.4 1723.34    5210 1723.19
  5277.1  1724.7  5282.7 1726.12  5295.2 1725.94    5335 1736.68  5339.8 1739.59
    5345 1739.99  5374.3 1750.92  5379.5 1751.41  5385.7 1754.49  5414.1 1763.54
  5453.8 1768.31  5528.1  1770.3  5533.3 1769.38  5567.8  1771.4  5688.7 1771.75
#Mann= 8 ,-1 , 0
  2446.4    .045       0  3771.4    .035       0  3923.4    .045       0
  4913.3     .07       0    4964    .045       0  5014.3     .07       0
  5099.4     .16       0    5335     .07       0
Bank Sta=4964,5014.3
XS Rating Curve= 0 ,0
Exp/Cntr=0.3,0.1

Type RM Length L Ch R = 1 ,4729    ,982,982,982
BEGIN DESCRIPTION:
Mapping XS cf3b26e9
END DESCRIPTION:
XS GIS Cut Line= 3
      1499603.74       6923234.9      1500957.87      6923651.56
      1503110.29      6923130.81
#Sta/Elev= 30
  2413.8 1728.16  3306.3 1727.37  3471.8 1726.92  4177.4 1722.58  4895.7 1722.09
  4968.6 1722.49  4990.2 1720.58  5010.4 1715.87  5015.6 1711.68  5031.4 1710.23
    5052 1713.36  5062.6 1718.59    5124 1721.54  5141.1 1714.98  5206.3 1714.82
  5229.9 1715.26  5237.2 1718.28  5262.4 1719.84  5319.5 1715.21    5340 1721.63
  5720.7 1727.06    5779 1735.97  5784.1 1734.56    5819 1745.97  5862.7 1762.27
  5867.8 1761.62  5885.3 1767.67  5929.9 1770.74  6015.3 1768.83  6045.1 1767.75
#Mann= 10 ,-1 , 0
  2413.8    .045       0  3306.3    .035       0  3471.8    .045       0
  4895.7     .05       0  4990.2    .045       0  5062.6     .05       0
  5262.4     .16       0    5819     .07       0  5929.9    .035       0
  6015.3     .07       0
Bank Sta=4990.2,5062.6
XS Rating Curve= 0 ,0
Exp/Cntr=0.3,0.1

Type RM Length L Ch R = 1 ,3747    ,965,965,965
BEGIN DESCRIPTION:
Mapping XS 94ec5282
END DESCRIPTION:
XS GIS Cut Line= 3
      1500410.96      6923920.65      1501982.18       6924033.5
      1503440.26      6923608.23
#Sta/Elev= 30
  2845.2 1726.99  2876.1 1725.95  2968.4 1726.79  3621.2 1725.38  3995.6 1721.53
  4685.9 1720.98  4815.9  1721.1  4902.6 1721.27  4958.9 1717.92  4985.9 1708.78
  4992.4 1712.43  5017.2 1719.81  5031.1 1721.02  5164.2  1721.6  5218.2 1720.62
  5349.2 1719.28  5453.3 1719.33  5603.3 1726.46  5631.5 1731.01  5636.7  1730.6
  5663.5 1738.54  5670.2 1741.87  5675.4 1739.27  5703.7 1753.53  5708.9 1750.32
  5715.1 1755.85  5742.4 1765.39  5775.9 1767.45  5826.7 1767.31  5939.3 1768.63
#Mann= 13 ,-1 , 0
  2845.2    .035       0  2968.4    .045       0  3995.6     .05       0
  4685.9    .045       0  4815.9     .05       0  4958.9     .05       0
  5017.2     .05       0  5164.2     .07       0  5218.2     .05       0
  5349.2     .07       0  5453.3     .16       0  5663.5     .07       0
  5826.7    .035       0
Bank Sta=4958.9,5017.2
XS Rating Curve= 0 ,0
Exp/Cntr=0.3,0.1

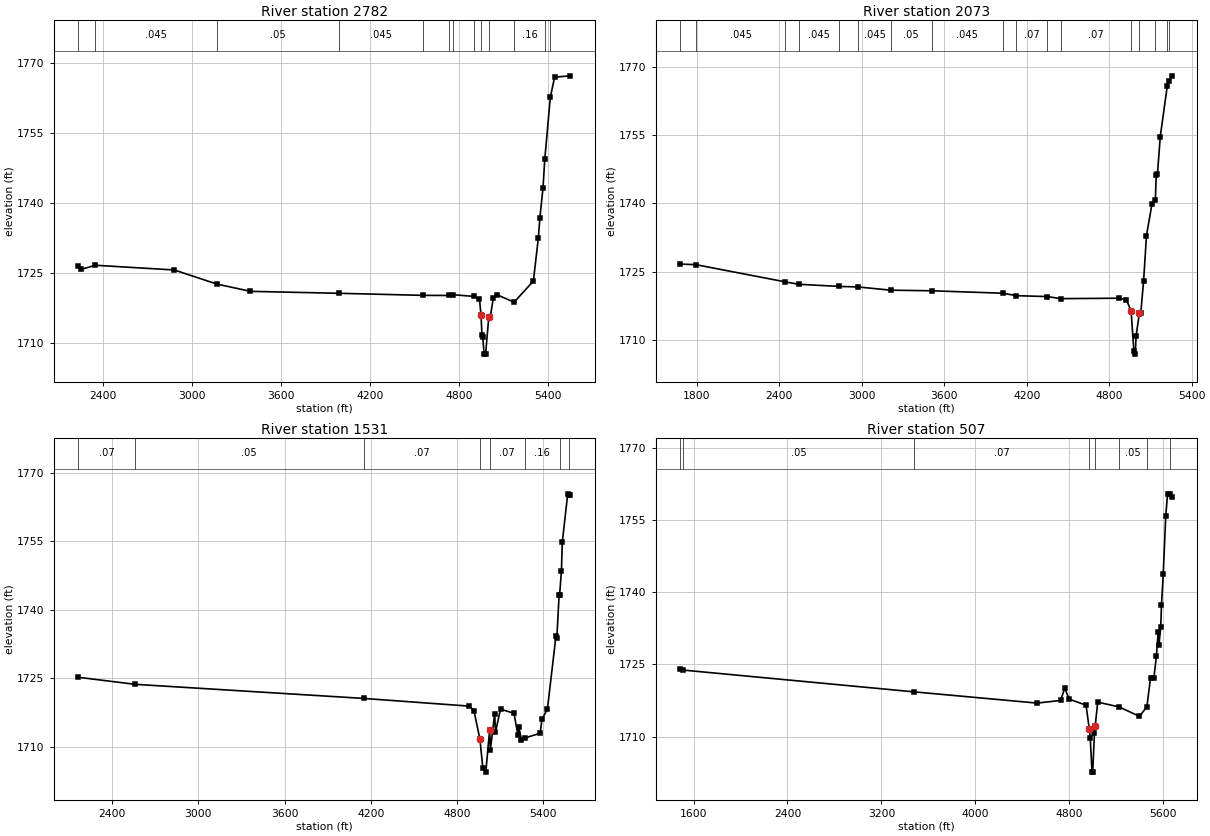
Type RM Length L Ch R = 1 ,2782    ,709,709,709
BEGIN DESCRIPTION:
Mapping XS a5c5a63b
END DESCRIPTION:
XS GIS Cut Line= 3
      1500332.83      6924241.83      1502364.12      6924467.53
      1503579.32      6924102.97
#Sta/Elev= 30
  2235.4 1726.58  2257.7 1725.77  2351.1 1726.64  2883.2 1725.63  3168.7 1722.62
  3394.7 1721.05  3993.5 1720.63  4554.9 1720.19  4730.3 1720.16  4757.8 1720.33
  4899.4 1719.97  4937.9 1719.41  4948.3 1716.01  4954.8 1711.71  4960.1 1711.21
  4969.2 1707.59  4979.6  1707.7  5000.5 1715.46  5010.9  1715.6  5031.8 1719.71
  5052.7 1720.37  5170.7 1718.72  5301.1 1723.24  5334.2 1732.43    5345 1736.86
  5365.9 1743.24  5377.7 1749.35  5415.1 1762.62  5443.8 1766.96  5547.9 1767.25
#Mann= 13 ,-1 , 0
  2235.4    .035       0  2351.1    .045       0  3168.7     .05       0
  3993.5    .045       0  4554.9     .05       0  4730.3     .07       0
  4757.8     .05       0  4899.4     .07       0  4948.3    .045       0
  5000.5     .16       0  5170.7     .16       0  5377.7     .07       0
  5415.1    .035       0
Bank Sta=4948.3,5000.5
XS Rating Curve= 0 ,0
Exp/Cntr=0.3,0.1

Type RM Length L Ch R = 1 ,2073    ,542,542,542
BEGIN DESCRIPTION:
Mapping XS 8b73e784
END DESCRIPTION:
XS GIS Cut Line= 3
      1500315.55      6924363.38      1501817.25      6924953.64
      1503760.88      6924675.98
#Sta/Elev= 30
  1681.5 1726.64  1794.2 1726.51  2444.8 1722.72  2542.4 1722.19  2838.2 1721.72
  2975.3  1721.6  3211.4 1720.89  3510.2 1720.76  4027.6 1720.22  4125.4 1719.68
  4347.1 1719.49  4450.6 1719.03  4868.6 1719.12    4925 1718.81  4959.5 1716.34
  4979.7 1707.53  4989.8 1706.81  4995.8 1710.72  5020.1 1715.94  5030.2 1715.97
  5050.4 1722.86  5071.5 1732.92    5111  1739.8  5136.2 1740.82  5142.2 1746.17
  5151.4 1746.52  5171.7 1754.72  5223.1 1765.92  5235.6  1766.9  5258.4 1768.09
#Mann= 17 ,-1 , 0
  1681.5    .035       0  1794.2    .045       0  2444.8     .05       0
  2542.4    .045       0  2838.2     .05       0  2975.3    .045       0
  3211.4     .05       0  3510.2    .045       0  4027.6     .05       0
  4125.4     .07       0  4347.1     .05       0  4450.6     .07       0
  4959.5    .045       0  5020.1     .07       0  5136.2     .16       0
  5223.1     .07       0  5235.6    .035       0
Bank Sta=4959.5,5020.1
XS Rating Curve= 0 ,0
Exp/Cntr=0.3,0.1

Type RM Length L Ch R = 1 ,1531    ,1024,1024,1024
BEGIN DESCRIPTION:
Mapping XS 4abcca16
END DESCRIPTION:
XS GIS Cut Line= 4
      1500619.34      6925691.49       1502867.6      6925300.86
      1503761.69      6925066.49      1503865.87       6924875.5
#Sta/Elev= 30
  2162.8 1725.25  2558.4 1723.71  4149.3 1720.63  4886.6 1718.94  4917.6 1717.97
    4959 1711.79  4979.6 1705.48  5000.3 1704.52    5027 1713.68  5032.2 1709.44
  5062.2 1717.31  5067.4 1713.27  5102.6 1718.29  5196.7 1717.37  5223.8  1712.6
    5229 1714.44  5248.4 1711.65  5272.2 1711.98  5378.7 1713.02  5391.1 1716.07
  5429.1 1718.29  5488.9 1734.36  5494.6  1733.8  5510.7 1743.26  5513.8 1743.15
  5526.8 1748.55  5532.5 1754.72  5570.5 1765.34  5580.9 1765.04  5586.6 1765.13
#Mann= 8 ,-1 , 0
  2162.8     .07       0  2558.4     .05       0  4149.3     .07       0
    4959    .045       0    5027     .07       0  5272.2     .16       0
  5513.8     .05       0  5580.9     .07       0
Bank Sta=4959,5027
XS Rating Curve= 0 ,0
Exp/Cntr=0.3,0.1

Type RM Length L Ch R = 1 ,507     ,0,0,0
BEGIN DESCRIPTION:
Noodle Creek 1.0
END DESCRIPTION:
XS GIS Cut Line= 4
      1500775.56      6925743.57      1503441.21      6925943.22
      1504352.66      6925307.81      1504560.48      6924959.72
#Sta/Elev= 30
  1487.3 1724.12  1511.5 1723.81    3476 1719.29  4526.3 1716.95  4726.1  1717.5
  4762.4 1720.07  4798.9 1717.78  4943.4 1716.51  4970.4 1711.66  4979.2 1709.64
    4994 1702.61  5000.1 1702.74  5014.9 1710.72    5021 1712.16  5042.7 1717.15
  5225.5 1716.15  5398.2 1714.19  5461.4  1716.2  5492.6 1722.22  5520.8 1722.16
  5542.2 1726.65  5557.8 1731.66  5563.6 1728.92  5579.2 1732.75  5585.7 1737.34
  5600.6 1743.69    5622 1755.77  5637.5 1760.42    5658 1760.39  5676.9 1759.75
#Mann= 8 ,-1 , 0
  1487.3     .07       0  1511.5     .05       0    3476     .07       0
  4970.4    .045       0    5021     .07       0  5225.5     .05       0
  5461.4     .07       0    5658    .035       0
Bank Sta=4970.4,5021
XS Rating Curve= 0 ,0
Exp/Cntr=0.3,0.1

Chan Stop Cuts=-1
Use User Specified Reach Order=0
Composite Channel Slope=5