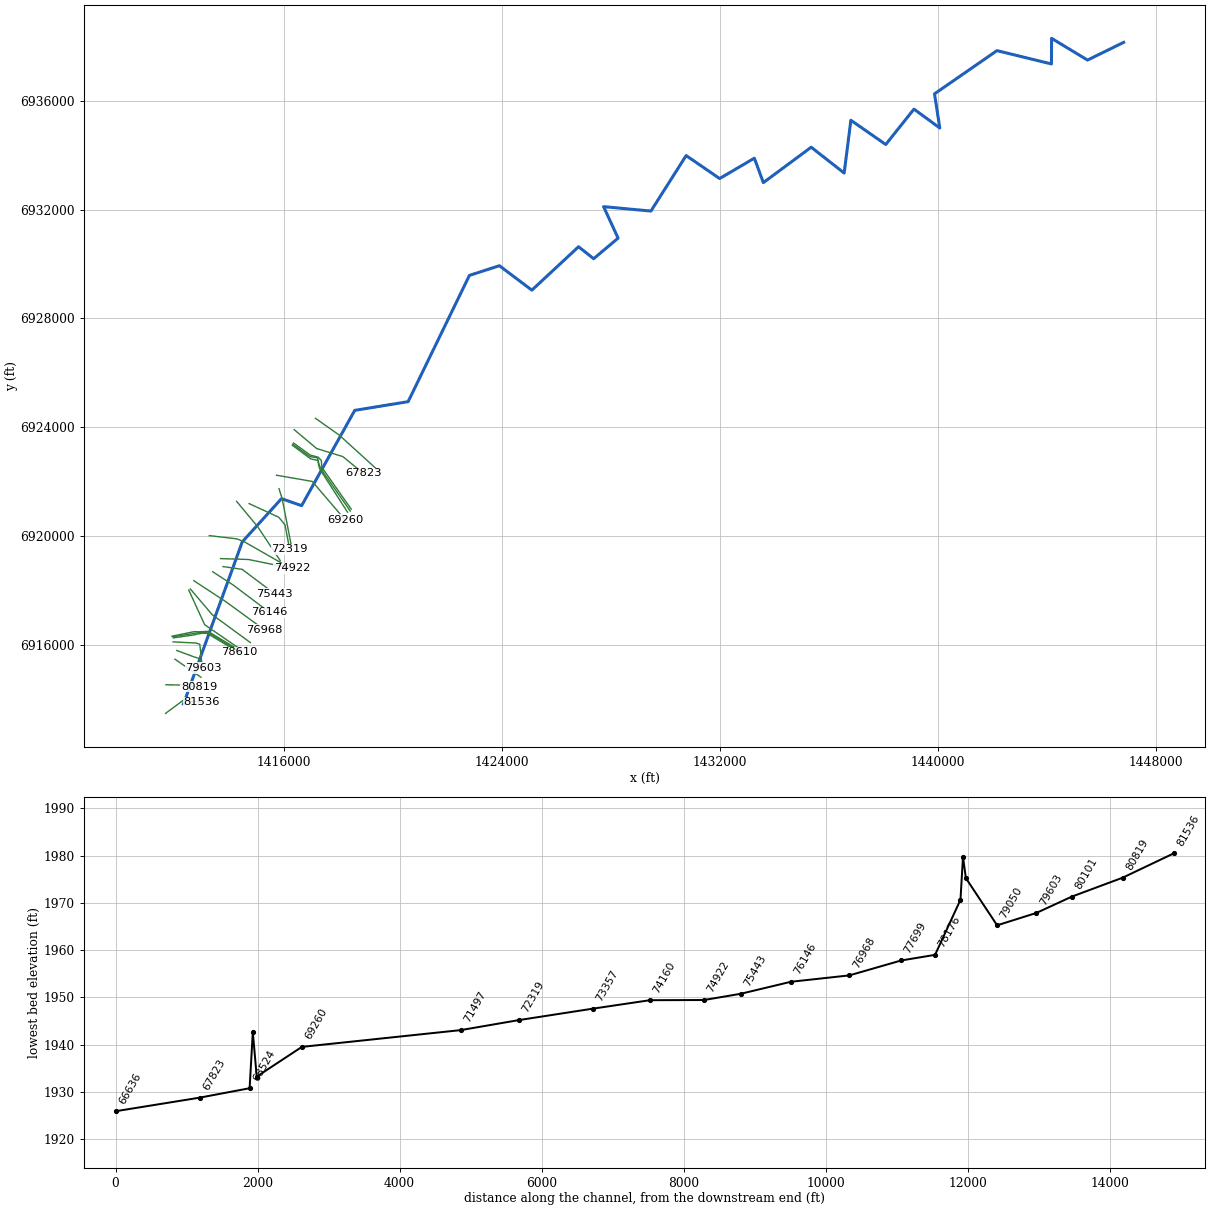
--- China Creek.prj (project) ---

Proj Title=China Creek Base Level Engineering
Current Plan=p01
Default Exp/Contr=0.3,0.1
English Units
Geom File=g01
Flow File=f01
Plan File=p01
Y Axis Title=Elevation
X Axis Title(PF)=Main Channel Distance
X Axis Title(XS)=Station
BEGIN DESCRIPTION:
China Creek
END DESCRIPTION:
DSS Export Rating Curves= 0
DSS Export Rating Curve Sorted= 0
DSS Export Volume Flow Curves= 0
DXF OffsetX= 0
DXF OffsetY= 0
DXF ScaleX= 1
DXF ScaleY= 10

--- China Creek.p01 (plan) ---

Plan Title=Multiple Run
Short Identifier=Multiple
Geom File=g01
Flow File=f01
Subcritical Flow
K Sum by GR= 0
Std Step Tol= 0.01
Critical Tol= 0.01
Num of Std Step Trials= 20
Max Error Tol= 0.3
Flow Tol Ratio= 0.001
Split Flow NTrial= 30
Split Flow Tol= 0.02
Split Flow Ratio= 0.02
Log Output Level= 0
Friction Slope Method= 1
Unsteady Friction Slope Method= 2
Unsteady Bridges Friction Slope Method= 1
Parabolic Critical Depth
Global Vel Dist=  1 , 1 , 1
Global Log Level= 0
CheckData=True
Encroach Param= -1, 0, 0, 0
BEGIN DESCRIPTION:
Multiple Run
END DESCRIPTION:

--- China Creek.f01 (steady flow) ---

Flow Title=Multiple
Program Version=4.10
Number of Profiles= 7
Profile Names=10-year,25-year,50-year,1pct_min,100-year,1pct_plu,500-year
River Rch & RM=China Creek,Reach-1         ,81536
     217     303     374     230     460     918     702
River Rch & RM=China Creek,Reach-1         ,80819
     363     522     657     412     822    1639    1301
River Rch & RM=China Creek,Reach-1         ,78610
     549     807    1032     655    1307    2608    2125
River Rch & RM=China Creek,Reach-1         ,77699
     863    1281    1648    1050    2094    4178    3430
River Rch & RM=China Creek,Reach-1         ,68624
     922    1368    1759    1120    2234    4458    3654
River Rch & RM=China Creek,Reach-1         ,59517
     984    1463    1883    1200    2395    4779    3927
River Rch & RM=China Creek,Reach-1         ,56839
    1058    1577    2033    1297    2588    5165    4254
River Rch & RM=China Creek,Reach-1         ,53740
    1054    1563    2008    1276    2547    5082    4153
River Rch & RM=China Creek,Reach-1         ,36168
    1126    1673    2152    1370    2733    5453    4469
River Rch & RM=China Creek,Reach-1         ,35033
    1171    1742    2242    1428    2849    5685    4663
River Rch & RM=China Creek,Reach-1         ,31104
    1208    1797    2314    1473    2940    5865    4809
River Rch & RM=China Creek,Reach-1         ,25257
    1249    1858    2392    1523    3038    6061    4969
River Rch & RM=China Creek,Reach-1         ,19295
    1262    1877    2415    1537    3067    6119    5013
River Rch & RM=China Creek,Reach-1         ,16240
    2422    3653    4750    3051    6087   12144   10118
River Rch & RM=China Creek,Reach-1         ,1895
    2413    3637    4728    3035    6055   12082   10057
Boundary for River Rch & Prof#=China Creek,Reach-1         , 1
Up Type= 0
Dn Type= 3
Dn Slope=0.00112
Boundary for River Rch & Prof#=China Creek,Reach-1         , 2
Up Type= 0
Dn Type= 3
Dn Slope=0.00112
Boundary for River Rch & Prof#=China Creek,Reach-1         , 3
Up Type= 0
Dn Type= 3
Dn Slope=0.00112
Boundary for River Rch & Prof#=China Creek,Reach-1         , 4
Up Type= 0
Dn Type= 3
Dn Slope=0.00112
Boundary for River Rch & Prof#=China Creek,Reach-1         , 5
Up Type= 0
Dn Type= 3
Dn Slope=0.00112
Boundary for River Rch & Prof#=China Creek,Reach-1         , 6
Up Type= 0
Dn Type= 3
Dn Slope=0.00112
Boundary for River Rch & Prof#=China Creek,Reach-1         , 7
Up Type= 0
Dn Type= 3
Dn Slope=0.00112
DSS Import GetInterval= 0
DSS Import GetPeak= 0
DSS Import FillOption= 0

--- China Creek.g01 (geometry) ---

Geom Title=Existing Conditions
Program Version=4.10

River Reach=China Creek     ,Reach-1
Reach XY= 30
        1412305.        6913838.      1414462.47      6919794.07
      1415902.56      6921382.61      1416641.81      6921124.26
      1418590.96      6924624.39      1420549.39      6924943.59
      1422798.63      6929580.67      1423899.23      6929936.16
      1425089.89       6929038.2      1426802.54       6930632.6
      1427357.44      6930193.39      1428253.97      6930948.43
      1427721.43      6932105.69      1429457.57      6931942.95
      1430751.29      6933980.33      1431979.78      6933137.66
      1433253.75      6933884.64      1433584.73       6932987.6
      1435339.78      6934287.48      1436549.17      6933339.53
      1436795.29      6935277.82      1438074.94      6934387.73
      1439111.32       6935686.7      1440057.62      6934993.44
      1439865.39      6936248.22       1442156.5      6937834.39
       1444155.3       6937345.2      1444160.85      6938285.96
      1445479.96      6937487.49        1446805.        6938138.

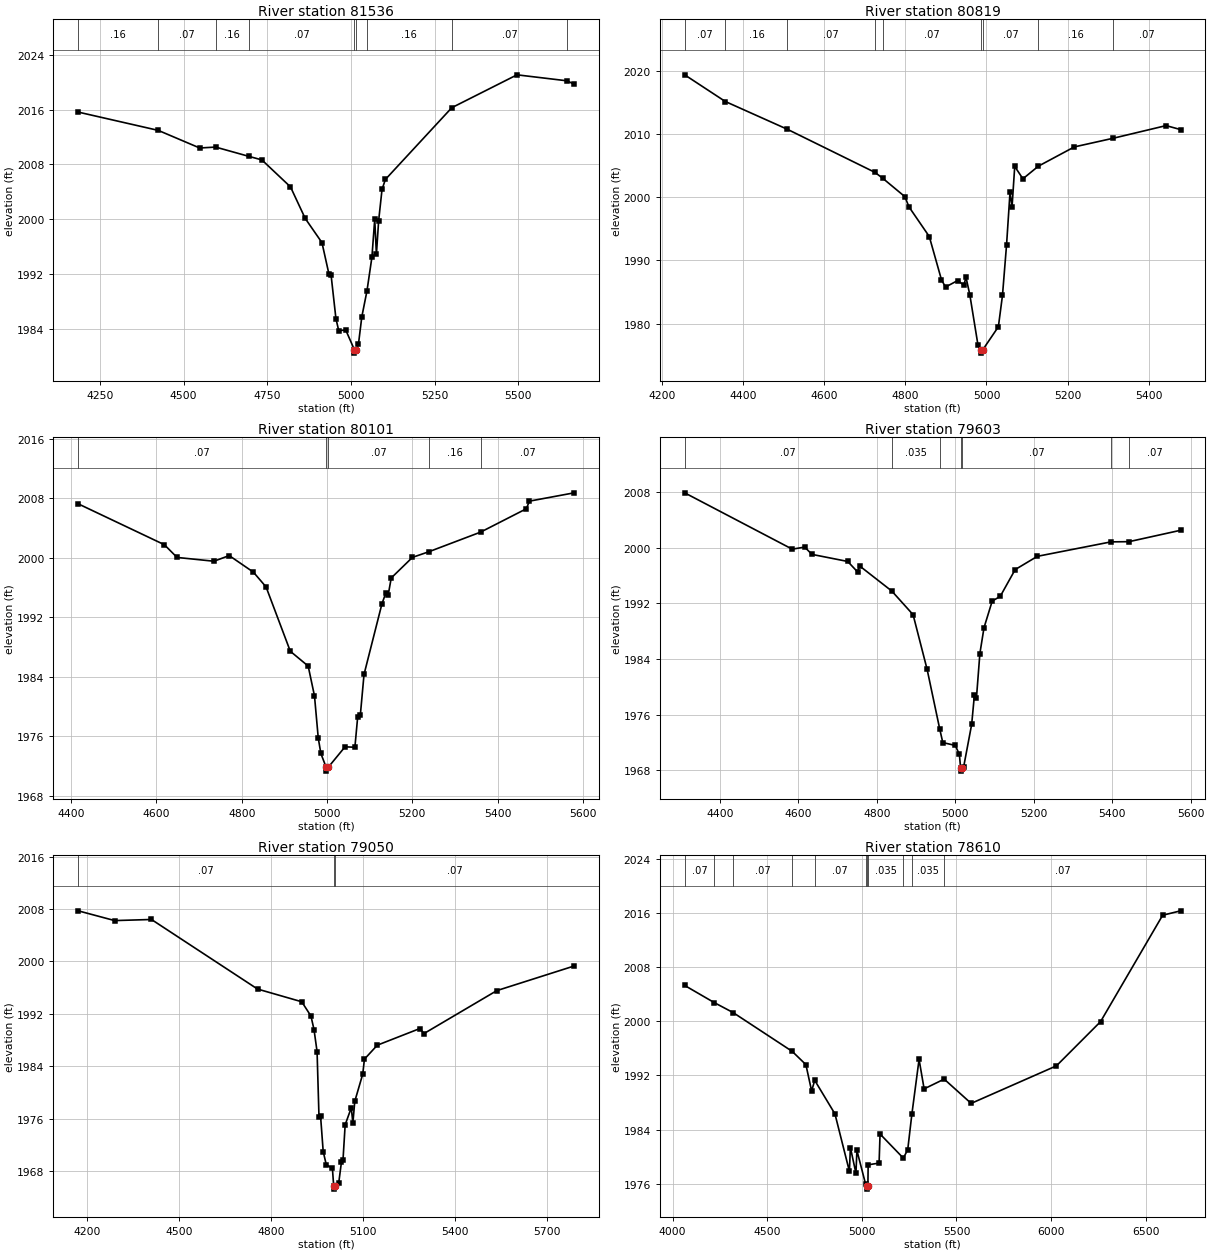
Type RM Length L Ch R = 1 ,81536   ,717,717,717
BEGIN DESCRIPTION:
China Creek 70.0
END DESCRIPTION:
XS GIS Cut Line= 3
      1411648.38      6913497.16      1412302.98      6913982.16
      1412964.39      6913899.93
#Sta/Elev= 30
  4185.3 2015.65  4424.3 2012.98  4548.1 2010.41  4595.7 2010.54  4695.4 2009.18
  4733.8 2008.67  4819.3 2004.73  4863.2 2000.13  4913.3 1996.59  4934.1 1992.01
  4940.4 1991.91    4955  1985.5  4963.4 1983.73  4984.2 1983.85  5010.1 1980.96
  5010.4 1980.46  5014.1 1980.96  5022.2 1981.73  5032.3 1985.76  5047.7 1989.54
  5062.5 1994.47  5070.9 2000.02  5075.9 1994.87  5082.6  1999.8  5092.7 2004.36
  5102.8 2005.82    5301 2016.29  5495.8 2021.09  5646.2 2020.21  5666.5  2019.7
#Mann= 9 ,-1 , 0
  4185.3     .16       0  4424.3     .07       0  4595.7     .16       0
  4695.4     .07       0  5010.1     .07       0  5014.1     .07       0
  5047.7     .16       0    5301     .07       0  5646.2     .16       0
Bank Sta=5010.1,5014.1
XS Rating Curve= 0 ,0
Exp/Cntr=0.3,0.1

Type RM Length L Ch R = 1 ,80819   ,718,718,718
BEGIN DESCRIPTION:
Mapping XS fc20bb88
END DESCRIPTION:
XS GIS Cut Line= 3
      1411662.32      6914549.24      1412398.38      6914531.88
      1412880.48      6914469.45
#Sta/Elev= 30
  4256.2 2019.34  4356.4 2015.12  4509.6 2010.72    4725 2003.92  4744.4 2002.98
    4799 2000.07    4809 1998.46  4859.1 1993.77  4889.1 1986.94  4899.1 1985.78
  4929.1 1986.81  4944.5 1986.07  4949.5 1987.35  4959.1 1984.53  4979.1 1976.61
    4986 1975.83  4986.3 1975.33  4990.6 1975.83  5029.4  1979.5  5039.5 1984.45
  5049.6 1992.48  5058.1 2000.77  5063.1 1998.47  5069.7 2004.85  5089.9  2002.9
  5128.1  2004.9  5216.6 2007.94  5313.1 2009.32  5442.8 2011.31  5478.6 2010.68
#Mann= 9 ,-1 , 0
  4256.2     .07       0  4356.4     .16       0  4509.6     .07       0
    4725     .16       0  4744.4     .07       0    4986     .07       0
  4990.6     .07       0  5128.1     .16       0  5313.1     .07       0
Bank Sta=4986,4990.6
XS Rating Curve= 0 ,0
Exp/Cntr=0.3,0.1

Type RM Length L Ch R = 1 ,80101   ,498,498,498
BEGIN DESCRIPTION:
Mapping XS 20f82894
END DESCRIPTION:
XS GIS Cut Line= 3
       1411992.1      6915486.76      1412467.83      6915156.88
      1412946.98      6914823.56
#Sta/Elev= 30
  4416.7 2007.26  4618.7 2001.76  4648.4 2000.05  4734.9 1999.54  4770.7  2000.3
  4827.4 1998.07  4857.1 1996.08  4913.9 1987.43  4955.8 1985.44  4970.6 1981.42
  4979.4 1975.77  4985.5 1973.69    4998 1971.81  4998.3 1971.31  5002.6 1971.81
  5042.2 1974.58  5065.3 1974.52  5071.9 1978.64    5078 1978.81  5086.7 1984.31
  5128.6 1993.79  5137.4 1995.22  5143.5 1995.04  5150.5 1997.29  5200.2 2000.06
  5238.4 2000.81  5360.2 2003.46  5467.3  2006.6  5474.3 2007.62  5579.3 2008.74
#Mann= 5 ,-1 , 0
  4416.7     .07       0    4998     .07       0  5002.6     .07       0
  5238.4     .16       0  5360.2     .07       0
Bank Sta=4998,5002.6
XS Rating Curve= 0 ,0
Exp/Cntr=0.3,0.1

Type RM Length L Ch R = 1 ,79603   ,553,553,553
BEGIN DESCRIPTION:
Mapping XS 5d60f22f
END DESCRIPTION:
XS GIS Cut Line= 4
      1412058.06       6915806.2      1412696.99      6915570.07
      1412891.44      6915511.04      1413044.21      6915163.85
#Sta/Elev= 30
  4310.3 2007.92  4584.4 1999.81  4616.2 2000.11  4634.5 1999.06  4725.8 1998.04
  4750.9 1996.53  4756.2 1997.39  4838.1 1993.78  4892.3 1990.38    4928 1982.52
    4960 1973.97    4968 1971.97  4999.8 1971.56  5010.3 1970.26  5013.3 1968.36
  5013.7 1967.86    5018 1968.36  5020.9  1968.4  5041.6  1974.6  5048.6 1978.84
  5053.8 1978.42  5062.5 1984.79    5073  1988.5  5093.9 1992.34  5114.3 1993.01
  5152.4 1996.87  5208.9 1998.78  5396.5 2000.86  5442.6 2000.89    5574 2002.53
#Mann= 7 ,-1 , 0
  4310.3     .07       0  4838.1    .035       0    4960     .07       0
  5013.3     .07       0    5018     .07       0  5396.5     .16       0
  5442.6     .07       0
Bank Sta=5013.3,5018
XS Rating Curve= 0 ,0
Exp/Cntr=0.3,0.1

Type RM Length L Ch R = 1 ,79050   ,440,440,440
BEGIN DESCRIPTION:
Mapping XS d6fae885
END DESCRIPTION:
XS GIS Cut Line= 4
      1411926.15      6916122.16      1412762.97      6916080.49
      1412905.33      6916035.35       1412971.3       6915406.9
#Sta/Elev= 30
  4170.2 2007.72  4289.2 2006.23  4409.3  2006.4  4755.6 1995.78  4899.9 1993.84
    4930 1991.66    4940  1989.6    4950 1986.24  4956.3 1976.24  4961.3 1976.46
    4970 1970.98    4980 1968.98  5000.1  1968.4  5004.2 1965.74  5004.5 1965.24
  5008.9 1965.74  5020.7 1966.18  5029.4 1969.31  5034.6 1969.65  5041.7 1975.06
  5061.7 1977.66  5066.9 1975.33  5073.1 1978.64  5099.2 1982.82  5104.6 1985.08
  5146.6 1987.21  5285.4 1989.75  5299.2 1988.99  5536.8 1995.54  5789.3  1999.3
#Mann= 3 ,-1 , 0
  4170.2     .07       0  5004.2     .07       0  5008.9     .07       0
Bank Sta=5004.2,5008.9
XS Rating Curve= 0 ,0
Exp/Cntr=0.3,0.1

Type RM Length L Ch R = 1 ,78610   ,41,41,41
BEGIN DESCRIPTION:
Mapping XS 60e31c10
END DESCRIPTION:
XS GIS Cut Line= 6
      1411931.34      6916269.72      1412723.04      6916384.31
      1412837.62      6916415.56      1413004.29       6916441.6
      1413176.16      6916436.39      1414341.44       6915734.1
#Sta/Elev= 30
  4064.1 2005.28  4220.3 2002.75  4319.9 2001.28  4632.3 1995.55  4704.4  1993.6
  4734.7 1989.71  4751.1 1991.28  4857.9 1986.33  4934.3 1977.86  4939.5 1981.37
  4968.8 1977.58    4974 1980.94    5020 1975.94  5024.9 1975.73  5025.4 1975.23
  5031.9 1975.73  5033.4 1978.82  5091.1 1979.07  5096.2 1983.36  5219.1 1979.81
  5242.3 1981.03  5264.1 1986.25  5302.3 1994.37    5329 1990.02  5434.9 1991.46
  5577.5 1987.88    6028 1993.42    6261 1999.94  6589.1 2015.64    6684 2016.29
#Mann= 11 ,-1 , 0
  4064.1     .07       0  4220.3    .035       0  4319.9     .07       0
  4632.3    .035       0  4751.1     .07       0    5020    .035       0
  5024.9     .07       0  5031.9    .035       0  5219.1     .07       0
  5264.1    .035       0  5434.9     .07       0
Bank Sta=5024.9,5031.9
XS Rating Curve= 0 ,0
Exp/Cntr=0.3,0.1

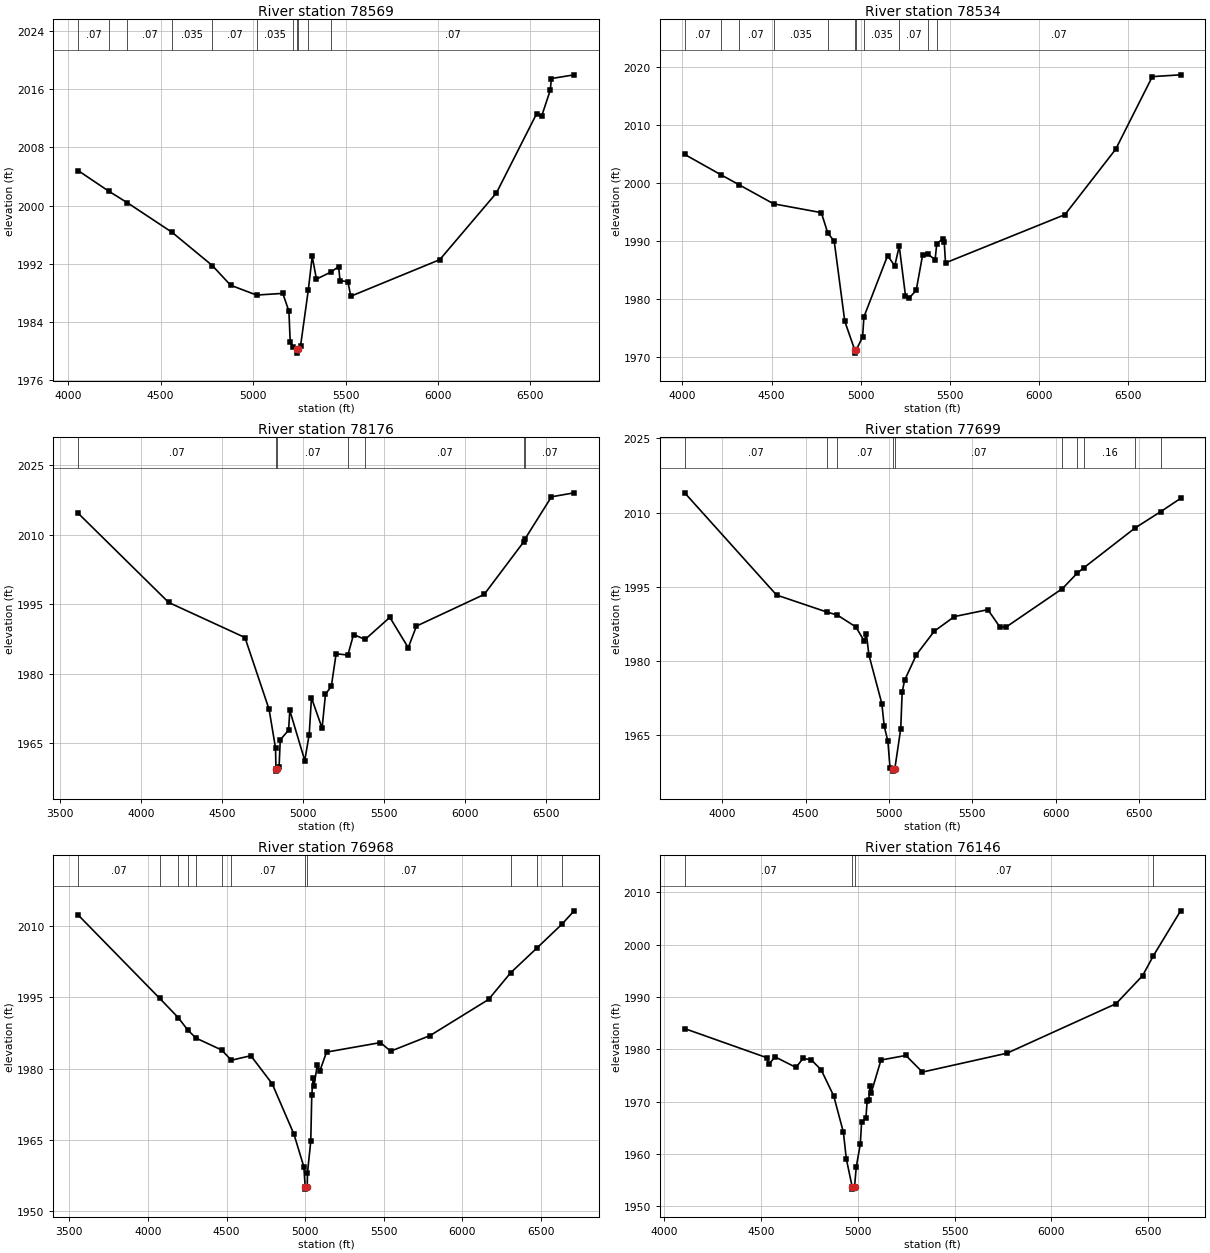
Type RM Length L Ch R = 1 ,78569   ,35,35,35
BEGIN DESCRIPTION:
Mapping XS dc3a3360
END DESCRIPTION:
XS GIS Cut Line= 6
      1411920.96      6916311.39      1412686.58      6916431.18
      1412868.87      6916462.43      1413045.95      6916472.85
      1413249.08       6916441.6      1414394.88      6915748.91
#Sta/Elev= 30
  4054.6 2004.79  4220.2 2001.96    4320 2000.39  4562.7 1996.31  4779.7 1991.76
  4878.7 1989.06  5018.8 1987.71  5160.9 1987.94  5193.9 1985.49    5201 1981.24
  5217.2 1980.52    5238 1980.24  5238.5 1979.74    5245 1980.24  5256.7  1980.7
  5298.7 1988.39  5319.9 1993.01  5342.7  1989.9  5422.1 1990.88  5462.7 1991.62
  5470.3 1989.69    5513 1989.54  5528.5 1987.55  6009.7 1992.57  6315.8 2001.72
  6533.5 2012.61  6561.2 2012.33  6607.2 2015.83  6613.1 2017.43  6736.3 2017.94
#Mann= 11 ,-1 , 0
  4054.6     .07       0  4220.2    .035       0    4320     .07       0
  4562.7    .035       0  4779.7     .07       0  5018.8    .035       0
  5217.2     .07       0    5238     .07       0    5245     .07       0
  5298.7    .035       0  5422.1     .07       0
Bank Sta=5238,5245
XS Rating Curve= 0 ,0
Exp/Cntr=0.3,0.1

Type RM Length L Ch R = 1 ,78534   ,358,358,358
BEGIN DESCRIPTION:
Mapping XS 5a8e66d7
END DESCRIPTION:
XS GIS Cut Line= 5
      1411884.48      6916332.22       1412702.2      6916498.89
      1412874.08      6916493.68       1413202.2      6916509.31
      1414440.92      6915765.04
#Sta/Elev= 30
  4013.1 2004.91  4216.3  2001.4  4316.8  1999.7  4511.6 1996.39  4779.1 1994.87
  4814.6 1991.42  4851.5 1989.91  4910.5 1976.15    4967 1971.15  4967.5 1970.65
    4974 1971.15  5010.5 1973.44  5017.8 1976.89  5150.7 1987.47  5190.7 1985.69
  5215.8 1989.09  5250.8 1980.57  5270.8 1980.14  5310.8 1981.46    5347 1987.59
  5374.8 1987.73  5417.1 1986.78  5426.1  1989.5  5459.8 1990.35    5468 1989.79
  5475.3 1986.21  6144.7 1994.53  6429.4 2005.81  6634.6 2018.32  6793.2 2018.63
#Mann= 11 ,-1 , 0
  4013.1     .07       0  4216.3    .035       0  4316.8     .07       0
  4511.6    .035       0  4814.6     .07       0    4967     .07       0
    4974     .07       0  5017.8    .035       0  5215.8     .07       0
  5374.8    .035       0  5426.1     .07       0
Bank Sta=4967,4974
XS Rating Curve= 0 ,0
Exp/Cntr=0.3,0.1

Type RM Length L Ch R = 1 ,78176   ,477,477,477
BEGIN DESCRIPTION:
Mapping XS bb0d28bc
END DESCRIPTION:
XS GIS Cut Line= 3
       1412499.1      6918024.89      1413082.41       6916754.1
      1414452.19       6915811.4
#Sta/Elev= 30
  3610.2 2014.63  4168.6 1995.39  4639.4 1987.82  4788.3 1972.32  4828.1 1963.97
  4830.7 1959.49  4831.2 1958.99  4837.8 1959.49  4850.1 1959.96  4857.3 1965.74
  4908.7 1967.84  4916.2 1972.09  5008.5 1961.28  5035.9 1966.88  5049.9 1974.81
  5115.5 1968.27  5136.5 1975.62  5172.3 1977.26  5202.1 1984.32  5274.6 1984.04
  5309.7 1988.47  5381.2 1987.41  5533.6 1992.18  5647.2 1985.63  5697.9 1990.29
  6115.9 1997.12  6361.3 2008.53  6369.6 2009.19  6531.2 2018.19  6671.3 2019.05
#Mann= 7 ,-1 , 0
  3610.2     .07       0  4830.7     .07       0  4837.8     .07       0
  5274.6    .035       0  5381.2     .07       0  6361.3     .16       0
  6369.6     .07       0
Bank Sta=4830.7,4837.8
XS Rating Curve= 0 ,0
Exp/Cntr=0.3,0.1

Type RM Length L Ch R = 1 ,77699   ,731,731,731
BEGIN DESCRIPTION:
Mapping XS 621c7e9c
END DESCRIPTION:
XS GIS Cut Line= 3
       1412556.4      6918066.57      1413358.45      6917123.89
      1414759.51      6916097.84
#Sta/Elev= 30
    3775 2014.01  4325.9 1993.37  4630.8  1989.9  4690.3 1989.33  4801.4 1986.93
  4850.8 1984.14  4865.1 1985.48  4879.4 1981.32  4957.4 1971.44  4971.7 1966.87
  4993.6 1963.87  5006.7 1958.34  5022.8  1958.3  5023.3  1957.8  5035.4  1958.3
  5070.8 1966.37  5079.3 1973.75  5093.9 1976.15    5165 1981.33  5271.5 1986.05
  5392.7 1989.02  5593.4 1990.41  5665.4 1986.91  5702.2 1986.89  6040.8 1994.68
  6129.4 1997.79  6169.5 1998.89  6475.7  2006.9  6630.9 2010.23  6749.3 2012.89
#Mann= 10 ,-1 , 0
    3775     .07       0  4630.8     .16       0  4690.3     .07       0
  5022.8     .07       0  5035.4     .07       0  6040.8     .16       0
  6129.4     .07       0  6169.5     .16       0  6475.7     .07       0
  6630.9     .16       0
Bank Sta=5022.8,5035.4
XS Rating Curve= 0 ,0
Exp/Cntr=0.3,0.1

Type RM Length L Ch R = 1 ,76968   ,822,822,822
BEGIN DESCRIPTION:
Mapping XS fcabc142
END DESCRIPTION:
XS GIS Cut Line= 3
       1412686.6      6918368.67      1413868.87      6917592.64
      1415275.14      6916566.59
#Sta/Elev= 30
  3556.2 2012.32  4073.9 1994.81  4192.4 1990.74  4252.7 1988.14    4306 1986.42
  4468.1 1983.93  4530.7 1981.77  4654.4 1982.72  4789.9 1976.83  4928.6 1966.21
  4991.7 1959.33    5000 1955.14  5000.5 1954.64  5012.7 1955.14  5014.8  1958.1
  5035.7 1964.74  5041.9 1974.41  5050.4 1978.01  5056.5 1976.41  5077.4 1980.84
  5092.1  1979.4  5136.1 1983.48  5479.1 1985.48  5543.9 1983.67    5795 1986.96
  6166.4 1994.55  6307.8 2000.19  6477.9 2005.49  6633.1 2010.39  6711.2 2013.21
#Mann= 12 ,-1 , 0
  3556.2     .07       0  4073.9     .16       0  4192.4     .07       0
  4252.7     .16       0    4306     .07       0  4468.1     .16       0
  4530.7     .07       0    5000     .07       0  5012.7     .07       0
  6307.8     .16       0  6477.9     .07       0  6633.1     .16       0
Bank Sta=5000,5012.7
XS Rating Curve= 0 ,0
Exp/Cntr=0.3,0.1

Type RM Length L Ch R = 1 ,76146   ,703,703,703
BEGIN DESCRIPTION:
China Creek 59.0
END DESCRIPTION:
XS GIS Cut Line= 3
      1413379.29      6918696.81      1414128.84      6918210.85
      1415461.34      6917208.19
#Sta/Elev= 30
  4106.7 1983.96  4530.6  1978.4  4542.5 1977.15  4572.8 1978.57  4681.6 1976.54
  4717.8 1978.26  4760.1    1978  4811.5 1976.08  4876.2  1971.1  4926.2 1964.17
  4941.3 1959.09  4971.2 1953.79  4971.7 1953.29    4984 1953.79  4992.8 1957.56
  5013.5 1961.86  5020.2 1966.03  5042.7 1966.97  5048.9 1970.08  5057.2 1970.25
  5063.5 1972.91  5070.3 1971.73  5120.3 1977.95  5248.8 1978.83  5334.2 1975.65
  5771.1 1979.26  6334.3 1988.72  6471.2 1994.07  6527.2 1997.89  6667.6 2006.46
#Mann= 4 ,-1 , 0
  4106.7     .07       0  4971.2     .07       0    4984     .07       0
  6527.2     .16       0
Bank Sta=4971.2,4984
XS Rating Curve= 0 ,0
Exp/Cntr=0.3,0.1

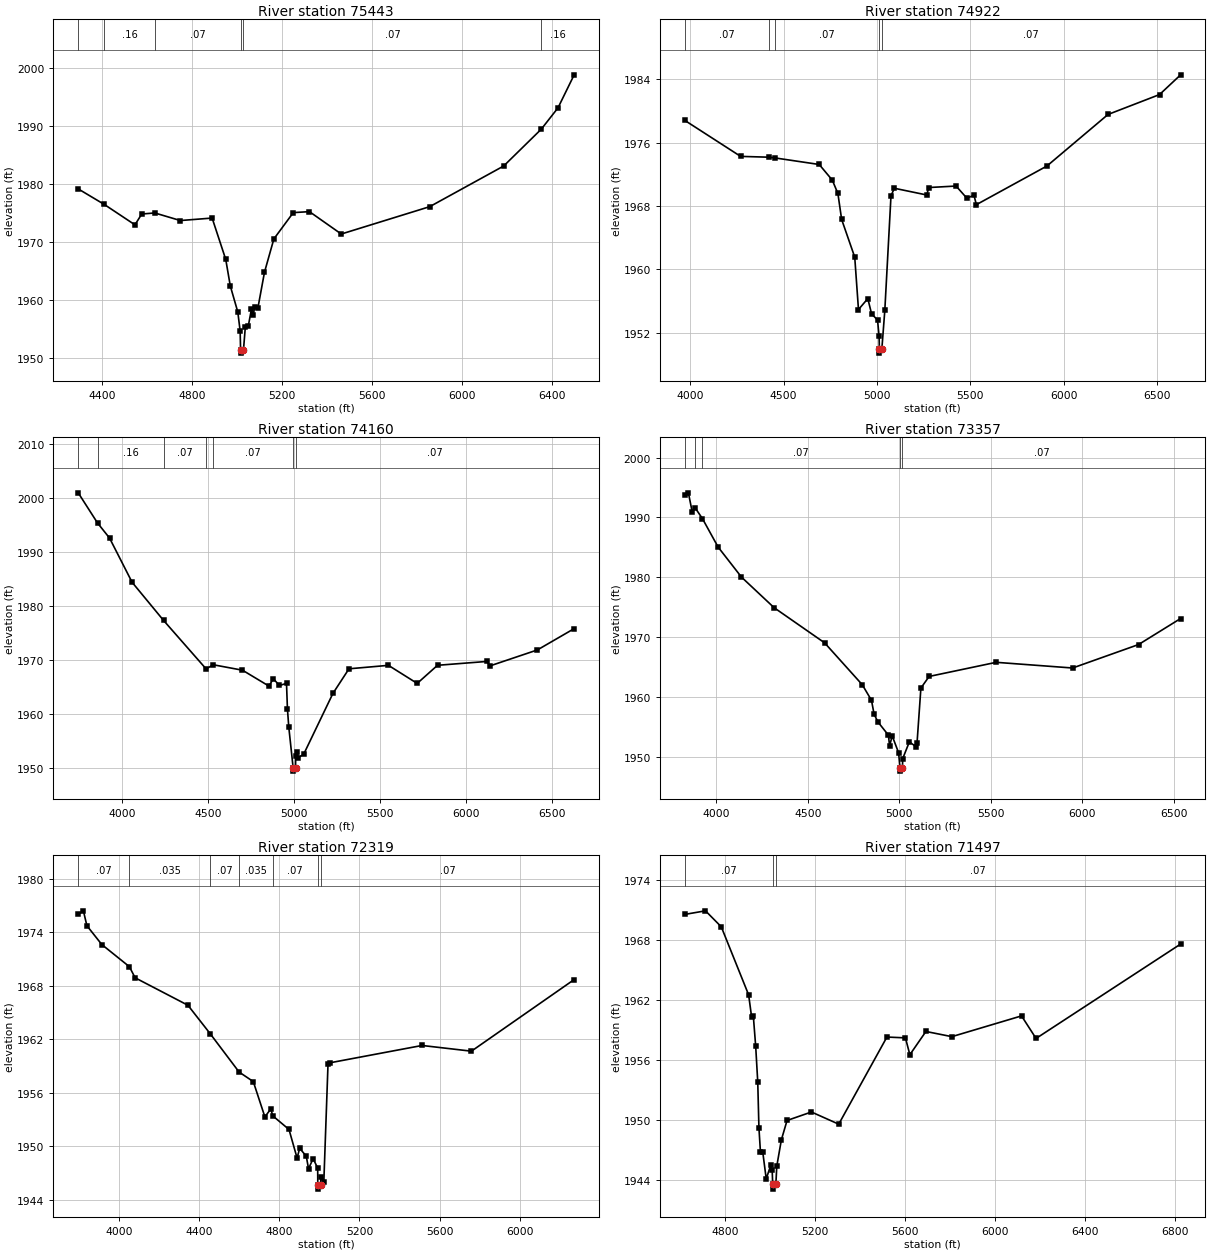
Type RM Length L Ch R = 1 ,75443   ,521,521,521
BEGIN DESCRIPTION:
China Creek 57.0
END DESCRIPTION:
XS GIS Cut Line= 3
      1413754.99        6918888.        1414455.        6918788.
      1415654.99      6917888.01
#Sta/Elev= 30
  4293.2 1979.15  4408.5 1976.48  4545.7 1972.94    4576 1974.81    4634 1974.99
  4747.8 1973.68  4889.2 1974.11  4949.8 1966.95    4970 1962.38  5003.4 1957.87
  5013.9 1954.58  5015.8 1951.26  5016.3 1950.76  5028.6 1951.26  5036.8 1955.25
  5050.3 1955.48  5063.9 1958.31  5072.2 1957.27  5078.4 1958.79    5093 1958.59
  5122.2 1964.75  5163.9  1970.5  5250.3 1975.05  5322.2 1975.22  5463.9 1971.35
  5857.6 1976.08  6186.8 1983.11  6354.1 1989.48  6428.4 1993.16  6500.3 1998.87
#Mann= 6 ,-1 , 0
  4293.2     .07       0  4408.5     .16       0    4634     .07       0
  5015.8     .07       0  5028.6     .07       0  6354.1     .16       0
Bank Sta=5015.8,5028.6
XS Rating Curve= 0 ,0
Exp/Cntr=0.3,0.1

Type RM Length L Ch R = 1 ,74922   ,762,762,762
BEGIN DESCRIPTION:
China Creek 56.0
END DESCRIPTION:
XS GIS Cut Line= 3
      1413665.73      6919181.18      1414693.88      6919147.52
      1416285.49      6918821.82
#Sta/Elev= 30
  3971.3  1978.8  4270.7 1974.25  4420.5 1974.15  4453.5 1974.06    4691 1973.23
    4761 1971.26    4791 1969.57    4811  1966.3  4881.1 1961.54  4901.1 1954.93
  4951.1 1956.31  4971.1 1954.39  5003.1 1953.61  5011.4 1951.56  5012.9 1949.93
  5013.4 1949.43  5026.1 1949.93    5042 1954.81  5075.1 1969.28    5093 1970.23
  5266.5 1969.38  5276.9 1970.32  5423.2 1970.51  5480.9 1968.98    5519 1969.34
  5531.9 1968.16  5909.6 1973.04  6236.2 1979.54  6511.8 1982.05  6624.6 1984.54
#Mann= 5 ,-1 , 0
  3971.3     .07       0  4420.5     .16       0  4453.5     .07       0
  5012.9     .07       0  5026.1     .07       0
Bank Sta=5012.9,5026.1
XS Rating Curve= 0 ,0
Exp/Cntr=0.3,0.1

Type RM Length L Ch R = 1 ,74160   ,803,803,803
BEGIN DESCRIPTION:
Mapping XS 7db8ac91
END DESCRIPTION:
XS GIS Cut Line= 4
      1413254.24      6920024.94      1414269.91      6919905.14
      1414561.58      6919785.35      1415900.07      6919019.75
#Sta/Elev= 30
  3746.3 2001.01  3858.4 1995.42  3928.3 1992.62  4059.2 1984.42    4242 1977.34
  4489.3 1968.34  4530.2 1969.12  4700.3 1968.11  4854.6 1965.15  4878.6 1966.54
  4915.1 1965.28  4955.9 1965.66  4961.3 1960.94  4969.1 1957.56  4994.8 1949.89
  4995.3 1949.39  5008.3 1949.89  5009.2 1952.18  5014.6 1952.91  5023.2 1951.86
  5055.6 1952.52  5225.4  1963.8  5318.7 1968.37  5547.8 1969.01  5714.8 1965.66
  5832.8 1969.02  6117.8 1969.73  6139.4 1968.93  6412.8 1971.87  6626.3 1975.82
#Mann= 7 ,-1 , 0
  3746.3     .07       0  3858.4     .16       0    4242     .07       0
  4489.3     .16       0  4530.2     .07       0  4994.8     .07       0
  5008.3     .07       0
Bank Sta=4994.8,5008.3
XS Rating Curve= 0 ,0
Exp/Cntr=0.3,0.1

Type RM Length L Ch R = 1 ,73357   ,1038,1038,1038
BEGIN DESCRIPTION:
Mapping XS ce1fdec9
END DESCRIPTION:
XS GIS Cut Line= 3
      1414254.31      6921285.32      1415019.91      6920363.48
      1415858.47      6919103.04
#Sta/Elev= 30
  3826.7 1993.71    3847  1994.1  3867.8 1990.93  3884.6 1991.56  3923.8 1989.79
  4009.7 1985.03  4137.3 1980.02  4315.7 1974.91  4591.8 1969.04  4798.1 1962.03
  4848.3 1959.43  4862.6 1957.11  4883.5 1955.82  4940.8 1953.61  4947.3 1951.81
  4961.6 1953.49  4996.7 1950.66  5004.2  1948.1  5004.7  1947.6  5017.9  1948.1
  5018.8 1949.66  5055.4 1952.49  5091.5 1951.69  5097.5 1952.34  5118.5 1961.48
  5163.6 1963.42  5530.3 1965.78  5948.2 1964.83  6308.9 1968.75  6538.9  1973.1
#Mann= 5 ,-1 , 0
  3826.7     .07       0  3884.6    .035       0  3923.8     .07       0
  5004.2     .07       0  5017.9     .07       0
Bank Sta=5004.2,5017.9
XS Rating Curve= 0 ,0
Exp/Cntr=0.3,0.1

Type RM Length L Ch R = 1 ,72319   ,822,822,822
BEGIN DESCRIPTION:
Mapping XS fcc2ed13
END DESCRIPTION:
XS GIS Cut Line= 4
      1414712.62      6921202.02      1415806.37      6920696.81
      1416030.33      6920420.77       1416202.2      6919524.96
#Sta/Elev= 30
  3797.8 1976.01  3823.6  1976.4  3841.1 1974.73  3915.4 1972.62  4052.7 1970.14
  4081.5 1968.89  4344.8 1965.81  4456.4  1962.6  4599.9 1958.32  4670.6 1957.25
  4728.4 1953.29  4758.7 1954.21  4766.6 1953.43  4848.6 1951.88  4888.9 1948.68
  4901.9 1949.77  4934.8 1948.88    4946 1947.47  4968.8 1948.61  4991.7 1947.55
  4992.1 1945.69  4992.6 1945.19  5006.1 1945.69  5007.9 1946.51  5022.3 1946.03
  5043.1 1959.19    5051 1959.35    5512  1961.3    5758 1960.66  6270.2 1968.69
#Mann= 7 ,-1 , 0
  3797.8     .07       0  4052.7    .035       0  4456.4     .07       0
  4599.9    .035       0  4766.6     .07       0  4992.1     .07       0
  5006.1     .07       0
Bank Sta=4992.1,5006.1
XS Rating Curve= 0 ,0
Exp/Cntr=0.3,0.1

Type RM Length L Ch R = 1 ,71497   ,2237,2237,2237
BEGIN DESCRIPTION:
Mapping XS ce6c0531
END DESCRIPTION:
XS GIS Cut Line= 3
      1415811.57      6921748.91      1415926.16      6921384.31
      1416275.12      6919597.86
#Sta/Elev= 30
  4621.9 1970.59  4714.3 1970.95  4784.4 1969.35  4905.9 1962.53  4919.2  1960.3
  4926.8 1960.39  4937.3 1957.36  4946.4 1953.79  4951.6 1949.22  4958.3 1946.81
  4968.8 1946.75    4984 1944.09  5004.1 1945.45  5010.5 1944.94  5012.8 1943.56
  5013.3 1943.06  5026.9 1943.56  5030.9 1945.36  5051.3    1948  5076.5 1949.94
  5184.7 1950.79    5306 1949.57    5520  1958.3  5602.2 1958.22  5621.9 1956.53
  5693.2 1958.86  5808.4 1958.34  6117.8 1960.42  6182.3 1958.16  6824.3 1967.62
#Mann= 3 ,-1 , 0
  4621.9     .07       0  5012.8     .07       0  5026.9     .07       0
Bank Sta=5012.8,5026.9
XS Rating Curve= 0 ,0
Exp/Cntr=0.3,0.1

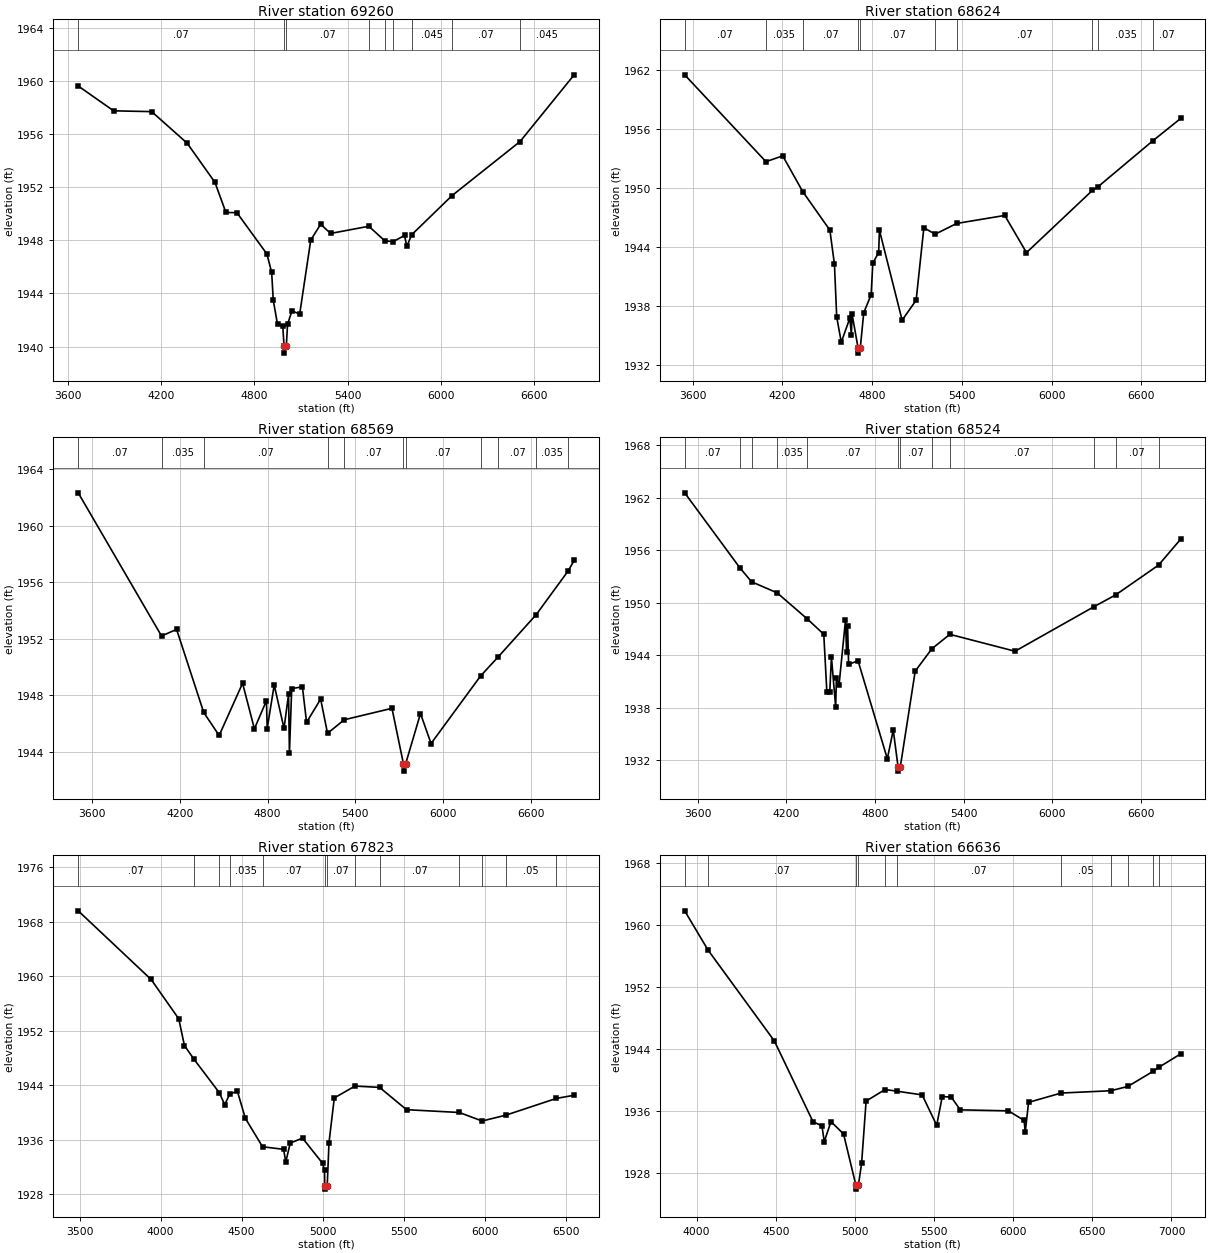
Type RM Length L Ch R = 1 ,69260   ,636,636,636
BEGIN DESCRIPTION:
China Creek 51.0
END DESCRIPTION:
XS GIS Cut Line= 3
      1415719.75      6922242.65       1417031.3      6922014.78
      1418236.76      6920602.48
#Sta/Elev= 30
  3668.8 1959.62  3896.4 1957.75    4141 1957.69  4368.6 1955.32  4547.6 1952.37
  4618.1  1950.1  4689.1 1950.08    4882 1946.97  4912.4 1945.58  4922.6 1943.49
  4949.9 1941.68  4983.5 1941.58  4992.2 1940.01  4992.7 1939.51  5006.5 1940.01
  5014.4 1941.68    5043 1942.69  5092.4 1942.45  5163.8 1948.03  5227.4 1949.21
  5291.1 1948.52  5536.9 1949.06  5640.1 1947.96  5694.7 1947.91  5766.5 1948.37
  5780.8 1947.55  5813.2 1948.43    6072 1951.37  6509.2 1955.44  6856.8 1960.46
#Mann= 9 ,-1 , 0
  3668.8     .07       0  4992.2     .07       0  5006.5     .07       0
  5536.9    .035       0  5640.1     .07       0  5694.7    .035       0
  5813.2    .045       0    6072     .07       0  6509.2    .045       0
Bank Sta=4992.2,5006.5
XS Rating Curve= 0 ,0
Exp/Cntr=0.3,0.1

Type RM Length L Ch R = 1 ,68624   ,55,55,55
BEGIN DESCRIPTION:
Mapping XS 2e740e63
END DESCRIPTION:
XS GIS Cut Line= 6
      1416301.17      6923342.63      1416973.04      6922842.64
      1417238.66      6922785.35       1417264.7      6922613.48
      1417311.58      6922462.43      1418327.21      6920884.29
#Sta/Elev= 30
  3545.5 1961.52  4089.2 1952.69  4201.4 1953.28  4335.6 1949.64    4517 1945.73
  4547.5 1942.26  4562.8 1936.89  4593.3 1934.33  4650.6 1936.78  4660.8  1935.1
  4665.8 1937.16    4706 1933.72  4706.5 1933.22  4720.3 1933.72  4743.5 1937.32
  4793.3 1939.17  4804.1 1942.37  4843.4 1943.45  4848.6 1945.71  5000.5 1936.57
  5094.2  1938.6  5145.7 1945.96  5222.1 1945.32  5366.2 1946.41  5687.2 1947.22
  5832.5 1943.44  6273.1 1949.76  6312.2 1950.15  6677.7 1954.81  6863.8 1957.08
#Mann= 10 ,-1 , 0
  3545.5     .07       0  4089.2    .035       0  4335.6     .07       0
    4706     .07       0  4720.3     .07       0  5222.1    .035       0
  5366.2     .07       0  6273.1    .045       0  6312.2    .035       0
  6677.7     .07       0
Bank Sta=4706,4720.3
XS Rating Curve= 0 ,0
Exp/Cntr=0.3,0.1

Type RM Length L Ch R = 1 ,68569   ,45,45,45
BEGIN DESCRIPTION:
Mapping XS 7948ec98
END DESCRIPTION:
XS GIS Cut Line= 6
      1416311.56      6923384.32      1416946.99      6922925.98
      1417217.83      6922884.31      1417295.95      6922592.64
      1417457.41       6922316.6      1418426.16      6920925.98
#Sta/Elev= 30
    3505 1962.32  4074.8  1952.2  4177.6 1952.67    4363  1946.8  4468.6 1945.17
  4628.8 1948.86  4709.5 1945.64    4792 1947.63  4797.1 1945.66  4845.1 1948.74
  4912.1 1945.67  4943.2 1948.08  4949.1 1943.91  4964.6 1948.48  5037.8 1948.61
  5066.3  1946.1  5162.6 1947.74  5209.6 1945.32  5323.7 1946.28  5650.2 1947.09
  5728.9 1943.15  5729.4 1942.65  5743.2 1943.15  5845.2 1946.72  5917.5  1944.6
  6256.4 1949.38  6377.9 1950.74    6637 1953.72  6854.8  1956.8  6895.8 1957.54
#Mann= 11 ,-1 , 0
    3505     .07       0  4074.8    .035       0    4363     .07       0
  5209.6    .035       0  5323.7     .07       0  5728.9     .07       0
  5743.2     .07       0  6256.4    .045       0  6377.9     .07       0
    6637    .035       0  6854.8     .07       0
Bank Sta=5728.9,5743.2
XS Rating Curve= 0 ,0
Exp/Cntr=0.3,0.1

Type RM Length L Ch R = 1 ,68524   ,701,701,701
BEGIN DESCRIPTION:
Mapping XS 585aeeb7
END DESCRIPTION:
XS GIS Cut Line= 6
      1416342.83      6923425.98      1416957.41      6922983.27
      1417243.87      6922905.14      1417363.66      6922785.35
      1417384.49      6922530.14      1418462.62      6920993.69
#Sta/Elev= 30
    3511 1962.54  3885.3 1953.96    3964 1952.38  4136.8 1951.12    4340 1948.15
  4452.5 1946.39  4473.2 1939.84  4493.1 1939.84  4504.3 1943.79  4532.9 1938.09
  4538.1 1941.42  4556.2 1940.65  4599.5    1948  4606.6 1944.35  4613.6  1947.3
  4620.7 1942.94  4684.3 1943.37  4882.6 1932.17  4922.7 1935.45  4955.2 1931.26
  4955.7 1930.76  4970.6 1931.26  5071.4 1942.18  5183.9 1944.73    5306 1946.38
  5746.9 1944.45  6279.6 1949.52  6428.6 1950.89  6718.1 1954.28  6867.8 1957.24
#Mann= 12 ,-1 , 0
    3511     .07       0  3885.3    .035       0    3964     .07       0
  4136.8    .035       0    4340     .07       0  4955.2     .07       0
  4970.6     .07       0  5183.9    .035       0    5306     .07       0
  6279.6    .045       0  6428.6     .07       0  6718.1    .035       0
Bank Sta=4955.2,4970.6
XS Rating Curve= 0 ,0
Exp/Cntr=0.3,0.1

Type RM Length L Ch R = 1 ,67823   ,1187,1187,1187
BEGIN DESCRIPTION:
Mapping XS 11ef0510
END DESCRIPTION:
XS GIS Cut Line= 4
      1416368.84      6923915.58      1417191.79      6923222.85
      1418155.33      6922925.98       1418910.3      6922306.38
#Sta/Elev= 30
  3491.9 1969.62    3942 1959.54  4112.4 1953.77  4147.5 1949.84  4205.9 1947.85
  4363.1 1942.91  4395.9 1941.16  4426.5 1942.71    4474 1943.15  4523.4 1939.16
  4629.5 1934.99  4759.3 1934.61  4772.9 1932.77  4800.4 1935.53  4876.2 1936.26
    5000 1932.56  5012.1 1931.51  5013.2 1929.27  5013.7 1928.77  5028.6 1929.27
  5039.6 1935.61  5072.3 1942.16  5200.2  1943.9    5352  1943.7    5518 1940.43
  5843.8 1940.02  5984.7 1938.77  6130.2 1939.62    6442 1942.08  6552.5 1942.55
#Mann= 13 ,-1 , 0
  3491.9     .07       0  4205.9    .035       0  4363.1     .07       0
  4426.5    .035       0  4629.5     .07       0  5013.2     .07       0
  5028.6     .07       0  5200.2    .035       0    5352     .07       0
  5843.8     .05       0  5984.7     .07       0  6130.2     .05       0
    6442     .07       0
Bank Sta=5013.2,5028.6
XS Rating Curve= 0 ,0
Exp/Cntr=0.3,0.1

Type RM Length L Ch R = 1 ,66636   ,825,825,825
BEGIN DESCRIPTION:
Mapping XS 4f183cf3
END DESCRIPTION:
XS GIS Cut Line= 3
      1417150.12      6924332.22      1418019.91      6923717.64
      1419550.53      6922326.59
#Sta/Elev= 30
  3924.8 1961.87  4072.6 1956.79  4491.6 1945.04  4735.4 1934.61    4792 1934.07
  4806.7 1932.03  4849.1 1934.62  4928.6 1933.02  5006.5 1926.39    5007 1925.89
  5022.1 1926.39  5042.6 1929.22    5071 1937.27  5191.2 1938.77  5263.2 1938.56
  5425.1 1938.07    5517 1934.14  5552.2 1937.86  5608.9 1937.79  5665.7 1936.14
  5969.8 1936.01  6069.1 1934.78  6076.5 1933.27  6097.5 1937.11  6302.7 1938.31
  6616.2 1938.61  6724.3 1939.16  6884.3 1941.12  6923.8 1941.68  7058.1 1943.37
#Mann= 11 ,-1 , 0
  3924.8    .035       0  4072.6     .07       0  5006.5     .07       0
  5022.1     .07       0  5191.2    .035       0  5263.2     .07       0
  6302.7     .05       0  6616.2     .07       0  6724.3     .05       0
  6884.3     .07       0  6923.8     .05       0
Bank Sta=5006.5,5022.1
XS Rating Curve= 0 ,0
Exp/Cntr=0.3,0.1