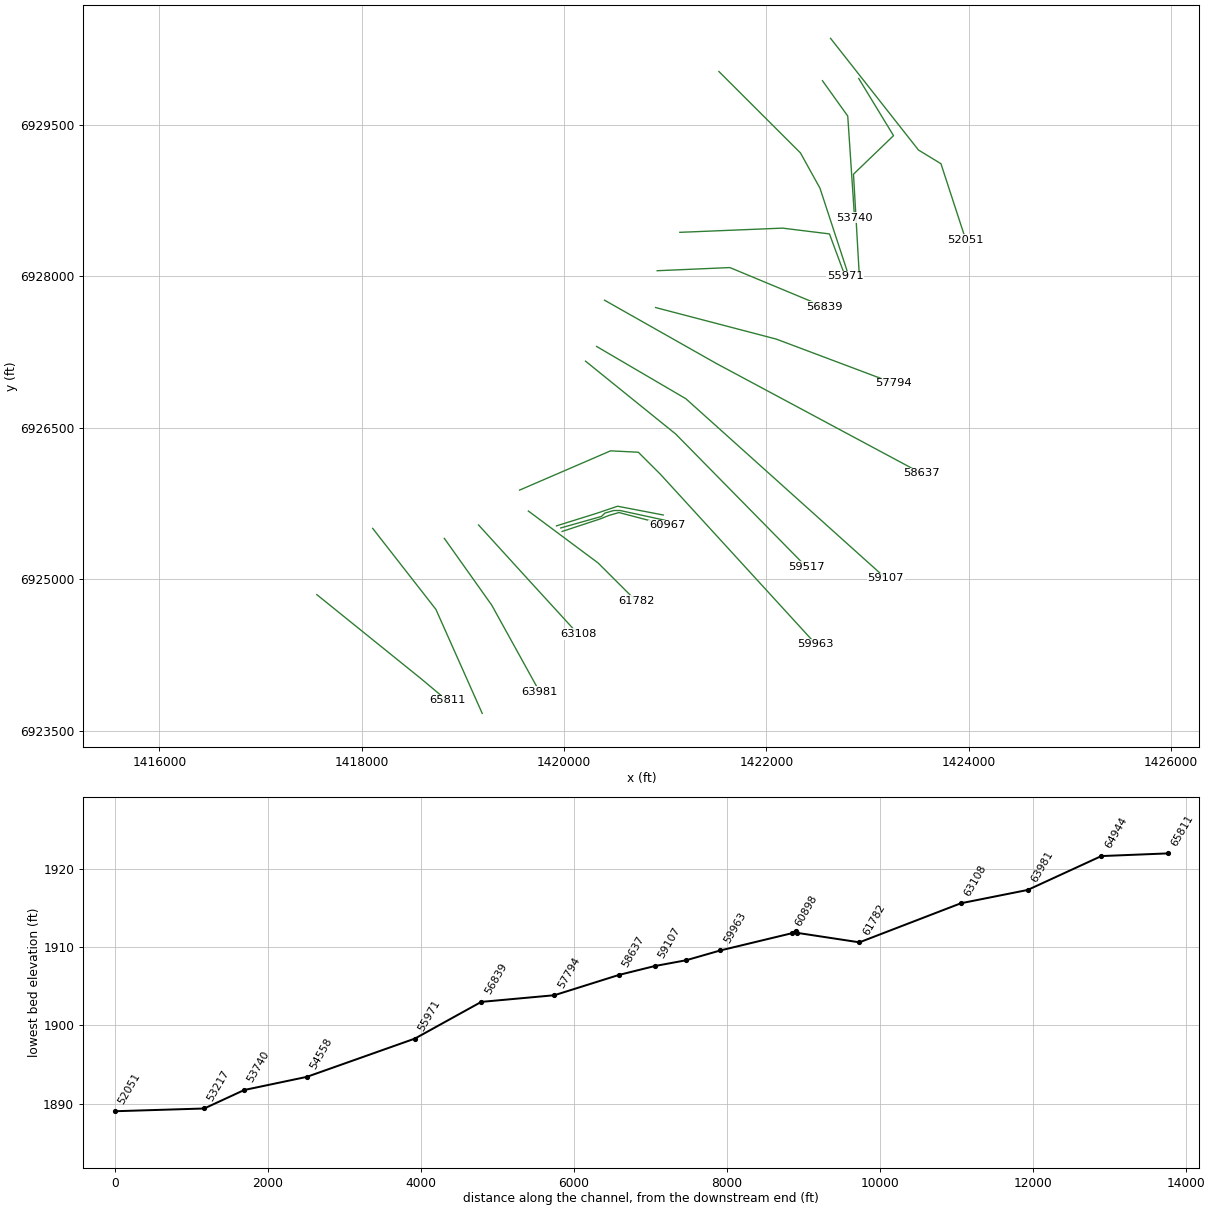
HEC-RAS study China Creek.prj: China Creek Base Level Engineering

--- China Creek.g01 (geometry) --- (continued)

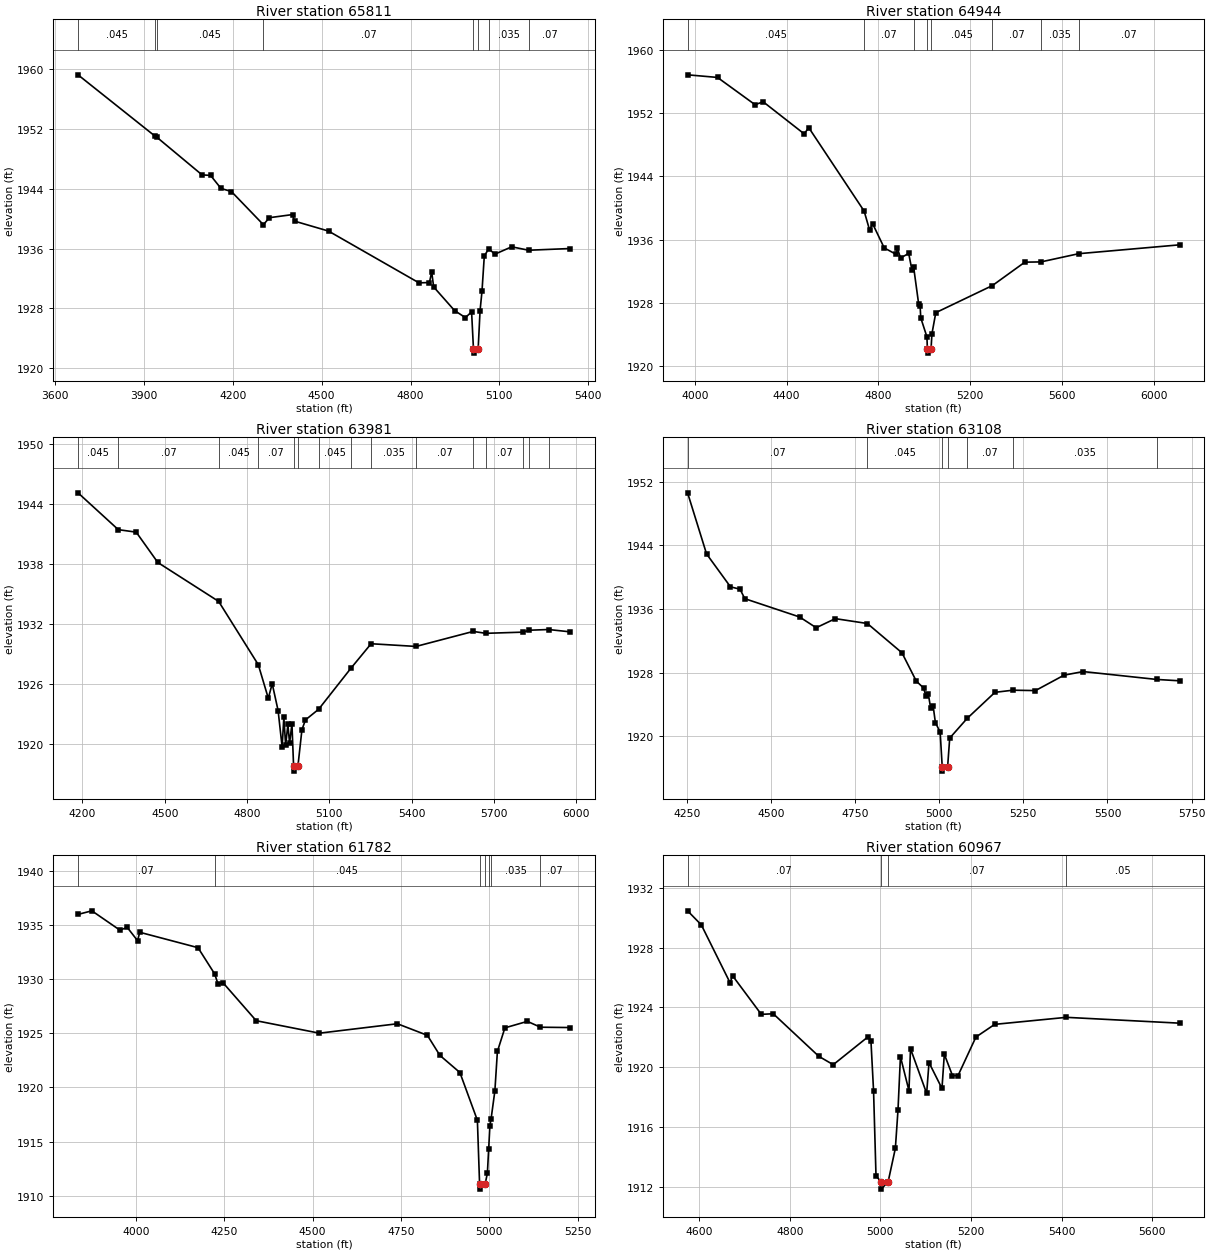
Type RM Length L Ch R = 1 ,65811   ,867,867,867
BEGIN DESCRIPTION:
Mapping XS c40eefe2
END DESCRIPTION:
XS GIS Cut Line= 3
      1417556.41      6924847.82      1418587.62      6924014.52
      1418844.34      6923799.48
#Sta/Elev= 30
  3677.5 1959.28  3938.5 1951.03  3943.8 1950.91  4096.2 1945.87    4125  1945.8
  4160.2 1944.05  4195.3 1943.64  4303.3 1939.19  4323.3 1940.13  4401.6 1940.55
  4408.5 1939.67  4523.1 1938.34  4828.5  1931.4  4863.7 1931.44  4871.4 1932.85
  4878.1 1930.85  4948.5 1927.69  4985.2 1926.74  5006.1 1927.51  5012.5 1922.48
    5013 1921.98  5028.2 1922.48  5034.7 1927.68  5041.2 1930.27    5049    1935
  5064.3 1935.99  5084.1 1935.23  5141.4 1936.23  5198.9 1935.77  5338.2    1936
#Mann= 8 ,-1 , 0
  3677.5    .045       0  3938.5    .035       0  3943.8    .045       0
  4303.3     .07       0  5012.5     .07       0  5028.2     .07       0
  5064.3    .035       0  5198.9     .07       0
Bank Sta=5012.5,5028.2
XS Rating Curve= 0 ,0
Exp/Cntr=0.3,0.1

Type RM Length L Ch R = 1 ,64944   ,963,963,963
BEGIN DESCRIPTION:
Mapping XS 1a0d3e68
END DESCRIPTION:
XS GIS Cut Line= 3
      1418108.46      6925504.09      1418733.45      6924702.02
      1419191.28       6923671.9
#Sta/Elev= 30
  3968.6 1956.85    4099 1956.52  4262.8 1953.07    4298 1953.44  4476.3 1949.39
  4497.1 1950.15  4738.1 1939.61  4762.1 1937.19    4775 1938.02  4825.7 1934.95
  4876.1 1934.16  4882.5 1934.94  4896.9 1933.67  4932.2 1934.26  4946.7 1932.11
  4953.8 1932.53  4975.7 1927.86    4982 1927.63  4984.8 1926.11  5011.7  1923.7
  5013.8 1922.14  5014.3 1921.64  5029.6 1922.14  5033.6 1924.09  5050.4 1926.76
  5297.2 1930.19  5438.5 1933.15  5508.5 1933.18  5673.1 1934.22  6112.7 1935.34
#Mann= 8 ,-1 , 0
  3968.6    .045       0  4738.1     .07       0  4953.8    .045       0
  5013.8    .045       0  5029.6    .045       0  5297.2     .07       0
  5508.5    .035       0  5673.1     .07       0
Bank Sta=5013.8,5029.6
XS Rating Curve= 0 ,0
Exp/Cntr=0.3,0.1

Type RM Length L Ch R = 1 ,63981   ,873,873,873
BEGIN DESCRIPTION:
Mapping XS b4d00682
END DESCRIPTION:
XS GIS Cut Line= 3
      1418816.79      6925405.14      1419285.54      6924743.68
      1419759.48      6923884.33
#Sta/Elev= 30
  4184.2 1945.12  4330.9 1941.44  4396.2 1941.19  4474.9 1938.16  4696.5 1934.27
    4841 1927.94  4877.4 1924.59  4891.6 1926.05  4913.1 1923.36  4927.8 1919.71
    4934  1922.7  4940.6 1919.88  4948.7 1921.98  4954.9  1920.1  4963.5 1922.04
  4969.5 1917.81    4970 1917.31  4985.3 1917.81  4999.9 1921.45  5012.8 1922.43
  5060.7 1923.49  5178.3 1927.59  5251.9 1930.04  5415.4 1929.77  5623.9 1931.27
  5669.8 1931.08  5806.5  1931.2  5827.1 1931.39  5898.4 1931.46  5976.3 1931.23
#Mann= 15 ,-1 , 0
  4184.2    .045       0  4330.9     .07       0  4696.5    .045       0
    4841     .07       0  4969.5     .07       0  4985.3     .07       0
  5060.7    .045       0  5178.3     .07       0  5251.9    .035       0
  5415.4     .07       0  5623.9    .035       0  5669.8     .07       0
  5806.5    .035       0  5827.1     .07       0  5898.4    .035       0
Bank Sta=4969.5,4985.3
XS Rating Curve= 0 ,0
Exp/Cntr=0.3,0.1

Type RM Length L Ch R = 1 ,63108   ,1326,1326,1326
BEGIN DESCRIPTION:
China Creek 42.0
END DESCRIPTION:
XS GIS Cut Line= 3
        1419155.      6925538.01        1419655.        6924988.
       1420139.3      6924457.53
#Sta/Elev= 30
  4252.5 1950.58  4308.9  1942.9  4379.9 1938.77  4408.3 1938.47  4422.5 1937.28
  4585.3 1934.98  4634.6 1933.63  4691.4 1934.77  4786.6 1934.16  4889.4 1930.48
    4932 1926.92  4953.6 1926.06  4960.3 1925.09  4967.8 1925.28  4974.5 1923.56
    4982 1923.81  4988.7 1921.72  5002.9  1920.5  5009.1 1916.11  5009.6 1915.61
    5025 1916.11  5031.3 1919.76    5083 1922.23  5165.7 1925.51  5218.9 1925.78
    5286 1925.73  5371.1 1927.67  5427.8 1928.12  5646.2 1927.13  5714.1 1926.96
#Mann= 7 ,-1 , 0
  4252.5     .07       0  4786.6    .045       0  5009.1    .045       0
    5025    .045       0    5083     .07       0  5218.9    .035       0
  5646.2     .07       0
Bank Sta=5009.1,5025
XS Rating Curve= 0 ,0
Exp/Cntr=0.3,0.1

Type RM Length L Ch R = 1 ,61782   ,815,815,815
BEGIN DESCRIPTION:
China Creek 40.0
END DESCRIPTION:
XS GIS Cut Line= 3
      1419647.77      6925675.78      1420336.32      6925162.13
       1420712.9      6924785.55
#Sta/Elev= 30
  3836.5 1935.97  3875.7  1936.3  3954.9 1934.52  3975.7 1934.77  4004.9 1933.55
  4011.2 1934.32  4175.9  1932.9  4222.8 1930.49  4232.3 1929.58  4246.8 1929.66
  4340.6 1926.16  4519.2 1925.01  4739.9 1925.88  4824.8 1924.81  4860.2 1922.96
  4916.7 1921.38  4966.2 1916.97  4972.4 1911.12  4972.9 1910.62  4988.3 1911.12
  4994.5 1912.09  4998.1 1914.31  5001.6 1916.47    5005 1917.11  5015.7 1919.69
  5022.8 1923.32    5044  1925.5  5107.6  1926.1  5144.7 1925.56  5228.1 1925.53
#Mann= 7 ,-1 , 0
  3836.5     .07       0  4222.8    .045       0  4972.4     .07       0
  4988.3    .045       0  4998.1     .07       0    5005    .035       0
  5144.7     .07       0
Bank Sta=4972.4,4988.3
XS Rating Curve= 0 ,0
Exp/Cntr=0.3,0.1

Type RM Length L Ch R = 1 ,60967   ,19,19,19
BEGIN DESCRIPTION:
Mapping XS ddb1c792
END DESCRIPTION:
XS GIS Cut Line= 5
      1419981.05      6925473.54      1420359.55      6925598.55
      1420446.36      6925633.27      1420543.58      6925661.05
      1421019.32      6925536.04
#Sta/Elev= 30
  4574.7 1930.46    4605 1929.52  4668.5 1925.64  4673.8 1926.12  4737.3 1923.53
  4763.7 1923.57  4864.2 1920.72    4896 1920.16  4973.3 1922.04  4979.2 1921.72
  4984.9 1918.42  4990.3 1912.72  5001.2 1912.33  5001.7 1911.83  5017.1 1912.33
    5033 1914.56  5038.8 1917.12  5044.2  1920.7    5063 1918.42  5066.4 1921.23
    5102 1918.24  5107.2  1920.3  5135.8 1918.57    5141 1920.86    5159 1919.43
  5171.2 1919.43  5210.7 1922.01  5252.1 1922.86  5410.3 1923.33  5659.8 1922.94
#Mann= 4 ,-1 , 0
  4574.7     .07       0  5001.2     .07       0  5017.1     .07       0
  5410.3     .05       0
Bank Sta=5001.2,5017.1
XS Rating Curve= 0 ,0
Exp/Cntr=0.3,0.1

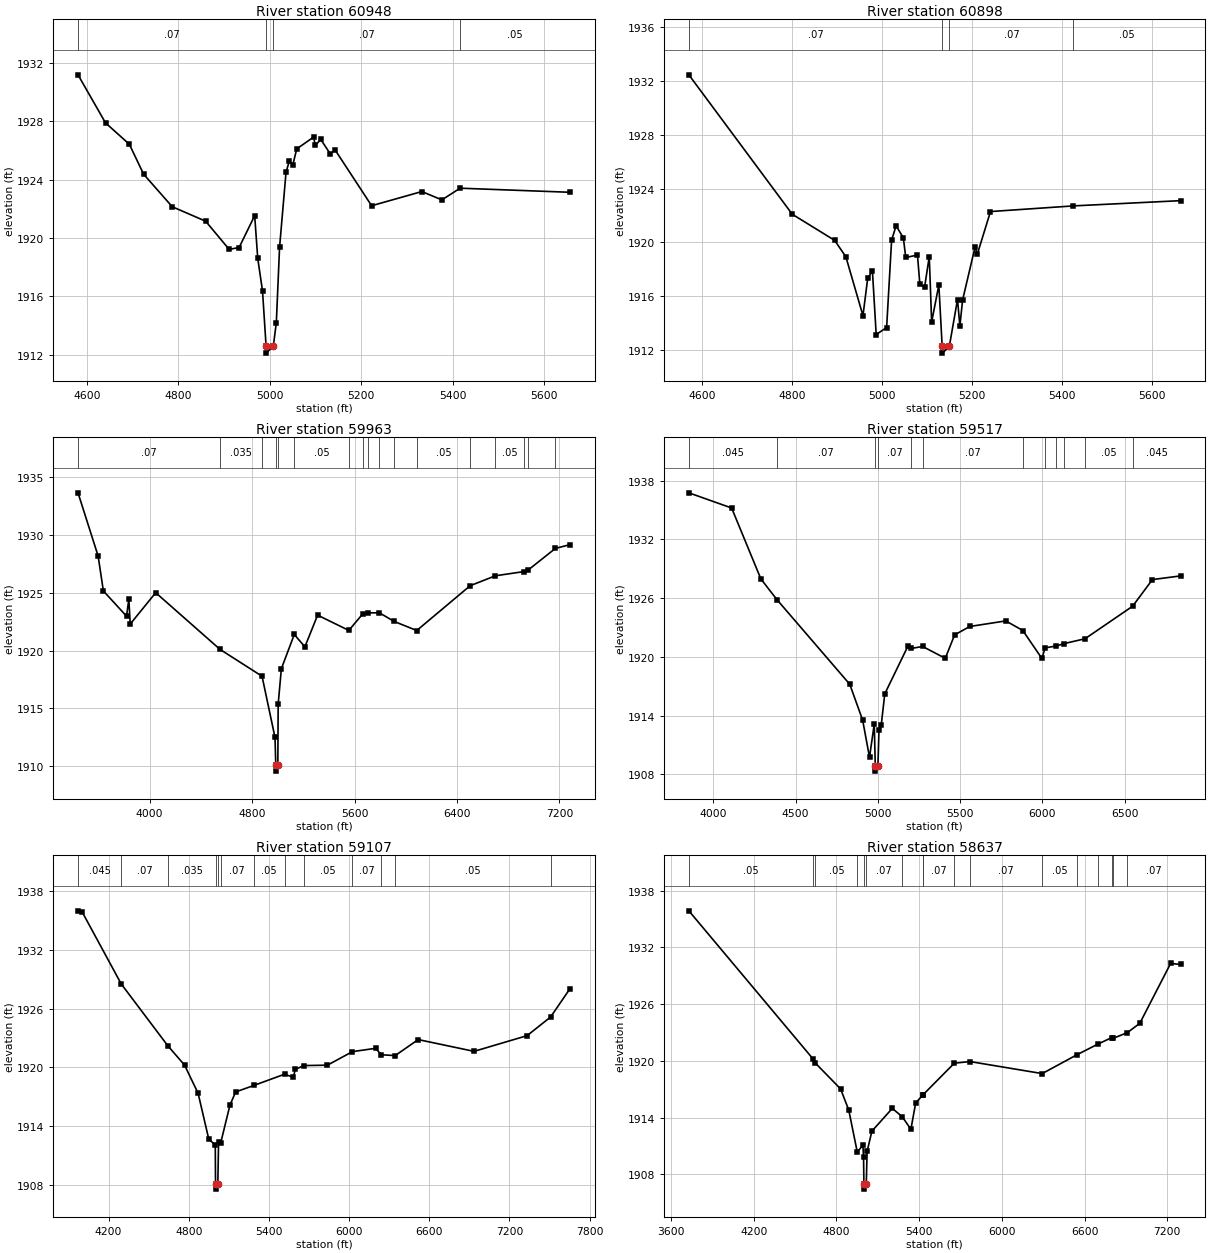
Type RM Length L Ch R = 1 ,60948   ,50,50,50
BEGIN DESCRIPTION:
Mapping XS e151c90c
END DESCRIPTION:
XS GIS Cut Line= 6
      1419967.15      6925508.26       1420370.3      6925622.43
      1420403.76      6925655.43      1420492.09      6925681.22
      1420555.67      6925681.04      1420998.47      6925584.65
#Sta/Elev= 30
    4581 1931.17  4641.1 1927.88  4693.1 1926.42  4724.3 1924.37  4786.9 1922.14
  4859.9 1921.15  4911.3 1919.22    4933 1919.35    4967 1921.53  4973.7  1918.6
  4984.1 1916.38  4991.9 1912.62  4992.4 1912.12  5007.8 1912.62  5014.3  1914.2
  5021.4 1919.37  5035.5  1924.5  5042.6 1925.26  5050.3    1925  5058.9  1926.1
  5095.8 1926.91  5099.3 1926.34  5111.4 1926.75  5131.9 1925.77  5143.1 1926.01
  5222.5 1922.21  5332.3 1923.18    5376 1922.61  5415.9 1923.41  5655.9 1923.13
#Mann= 4 ,-1 , 0
    4581     .07       0  4991.9      .1       0  5007.8     .07       0
  5415.9     .05       0
Bank Sta=4991.9,5007.8
XS Rating Curve= 0 ,0
Exp/Cntr=0.3,0.1

Type RM Length L Ch R = 1 ,60898   ,935,935,935
BEGIN DESCRIPTION:
Mapping XS 0e39c506
END DESCRIPTION:
XS GIS Cut Line= 4
      1419925.56      6925529.12      1420324.83       6925654.1
      1420529.69      6925723.55      1420980.54      6925636.85
#Sta/Elev= 30
  4571.3 1932.44  4801.2 1922.09  4895.5 1920.15  4920.4 1918.93  4958.4 1914.56
  4968.9 1917.33  4979.4  1917.9  4987.8 1913.16    5011 1913.68  5022.1 1920.17
  5032.1 1921.23  5048.2 1920.34  5053.5 1918.88  5079.6 1919.06  5084.9 1916.89
  5095.4 1916.67  5105.8 1918.95  5111.1 1914.09  5127.1 1916.84  5134.5 1912.28
    5135 1911.78  5150.4 1912.28  5168.6 1915.76  5173.9 1913.79  5179.9 1915.72
  5207.6 1919.65  5212.7 1919.13  5241.9 1922.29  5426.4 1922.71  5665.1  1923.1
#Mann= 4 ,-1 , 0
  4571.3     .07       0  5134.5     .07       0  5150.4     .07       0
  5426.4     .05       0
Bank Sta=5134.5,5150.4
XS Rating Curve= 0 ,0
Exp/Cntr=0.3,0.1

Type RM Length L Ch R = 1 ,59963   ,446,446,446
BEGIN DESCRIPTION:
China Creek 39.0
END DESCRIPTION:
XS GIS Cut Line= 5
      1419560.93      6925883.27      1420460.24      6926272.16
      1420734.64      6926258.36        1420955.        6926038.
      1422488.64      6924358.29
#Sta/Elev= 30
  3441.4 1933.63  3598.4 1928.17  3639.4 1925.15  3820.2 1922.97  3838.1 1924.43
  3849.1 1922.29    4048    1925  4550.1  1920.1  4878.1 1917.78  4979.3 1912.49
  4985.4 1910.08  4985.9 1909.58  5001.4 1910.08    5004 1915.36  5028.9 1918.43
  5129.8 1921.39  5212.6 1920.32  5311.9 1923.06  5555.6 1921.74  5665.1 1923.18
  5707.2 1923.26  5794.4 1923.26  5908.5 1922.52  6085.9 1921.73  6502.5  1925.6
  6699.5 1926.46  6920.1 1926.82  6958.1 1926.98  7168.7 1928.83  7282.1 1929.15
#Mann= 17 ,-1 , 0
  3441.4     .07       0  4550.1    .035       0  4878.1     .07       0
  4985.4     .07       0  5001.4     .07       0  5129.8     .05       0
  5555.6     .07       0  5665.1    .035       0  5707.2     .07       0
  5794.4    .035       0  5908.5     .07       0  6085.9     .05       0
  6502.5    .045       0  6699.5     .05       0  6920.1    .045       0
  6958.1     .05       0  7168.7    .045       0
Bank Sta=4985.4,5001.4
XS Rating Curve= 0 ,0
Exp/Cntr=0.3,0.1

Type RM Length L Ch R = 1 ,59517   ,410,410,410
BEGIN DESCRIPTION:
China Creek 38.0
END DESCRIPTION:
XS GIS Cut Line= 3
       1420212.6      6927160.36        1421105.        6926438.
       1422394.9      6925123.91
#Sta/Elev= 30
  3851.9 1936.75  4111.9  1935.2  4289.4 1927.96  4387.7 1925.83  4829.7  1917.2
  4908.1 1913.53  4949.7 1909.74  4978.5 1913.15  4984.8 1908.83  4985.3 1908.33
  5000.8 1908.83  5007.1 1912.49  5021.2 1913.07  5042.4 1916.22  5183.8 1921.12
  5204.4 1920.86  5272.4 1921.06  5410.1 1919.85  5466.7 1922.24  5558.7  1923.1
  5777.9 1923.67  5881.2 1922.69    5997 1919.84    6017 1920.92  6085.7 1921.11
  6128.9 1921.34  6259.5 1921.85  6548.5 1925.17  6668.8 1927.89  6841.4 1928.27
#Mann= 12 ,-1 , 0
  3851.9    .045       0  4387.7     .07       0  4984.8     .07       0
  5000.8     .07       0  5204.4     .05       0  5272.4     .07       0
  5881.2    .035       0    6017     .07       0  6085.7     .05       0
  6128.9     .07       0  6259.5     .05       0  6548.5    .045       0
Bank Sta=4984.8,5000.8
XS Rating Curve= 0 ,0
Exp/Cntr=0.3,0.1

Type RM Length L Ch R = 1 ,59107   ,470,470,470
BEGIN DESCRIPTION:
China Creek 37.0
END DESCRIPTION:
XS GIS Cut Line= 3
      1420321.97       6927306.2        1421205.        6926788.
      1423180.66      6925009.95
#Sta/Elev= 30
  3971.5 1935.97  4000.8  1935.9  4295.1 1928.51    4643 1922.22  4768.7 1920.24
  4870.3 1917.36  4950.4 1912.67  4998.7 1912.11  5000.7 1908.09  5001.2 1907.59
  5017.7 1908.09  5023.4 1912.38  5038.4 1912.25  5108.6 1916.16  5151.2  1917.5
  5288.9 1918.17  5517.4 1919.31  5583.2 1918.99  5597.4  1919.8  5661.7 1920.19
  5838.1 1920.23  6025.1 1921.61  6199.1 1921.95    6241 1921.29  6345.4 1921.21
  6517.5 1922.84  6935.3 1921.64  7332.2 1923.24  7508.3 1925.14  7653.3 1928.03
#Mann= 13 ,-1 , 0
  3971.5    .045       0  4295.1     .07       0    4643    .035       0
  5000.7    .035       0  5017.7    .035       0  5038.4     .07       0
  5288.9     .05       0  5517.4     .07       0  5661.7     .05       0
  6025.1     .07       0    6241    .035       0  6345.4     .05       0
  7508.3    .045       0
Bank Sta=5000.7,5017.7
XS Rating Curve= 0 ,0
Exp/Cntr=0.3,0.1

Type RM Length L Ch R = 1 ,58637   ,843,843,843
BEGIN DESCRIPTION:
China Creek 36.0
END DESCRIPTION:
XS GIS Cut Line= 3
      1420400.12      6927764.52        1421505.        6927138.
      1423530.19      6926051.05
#Sta/Elev= 30
  3729.6 1935.86  4628.6 1920.24  4647.9 1919.76  4830.2 1917.04  4889.4 1914.81
  4951.4 1910.35  4991.8 1911.11  4996.9 1909.88  4999.3 1906.95  4999.8 1906.45
  5016.5 1906.95  5022.5 1910.43  5057.4 1912.58  5205.2 1914.98    5277 1914.11
  5340.2 1912.77  5374.9 1915.56  5426.6 1916.39    5427  1916.4  5655.2 1919.76
  5769.3 1919.93  6292.7 1918.66  6542.2 1920.63  6695.8 1921.77  6796.6 1922.46
  6804.7 1922.37  6910.7 1922.99  7000.5 1923.97  7224.2  1930.3  7298.2 1930.19
#Mann= 17 ,-1 , 0
  3729.6     .05       0  4628.6     .07       0  4647.9     .05       0
  4951.4     .07       0  4999.3     .07       0  5016.5     .07       0
    5277    .035       0  5426.6     .05       0    5427     .07       0
  5655.2    .035       0  5769.3     .07       0  6292.7     .05       0
  6542.2    .035       0  6695.8     .05       0  6796.6     .07       0
  6804.7     .05       0  6910.7     .07       0
Bank Sta=4999.3,5016.5
XS Rating Curve= 0 ,0
Exp/Cntr=0.3,0.1

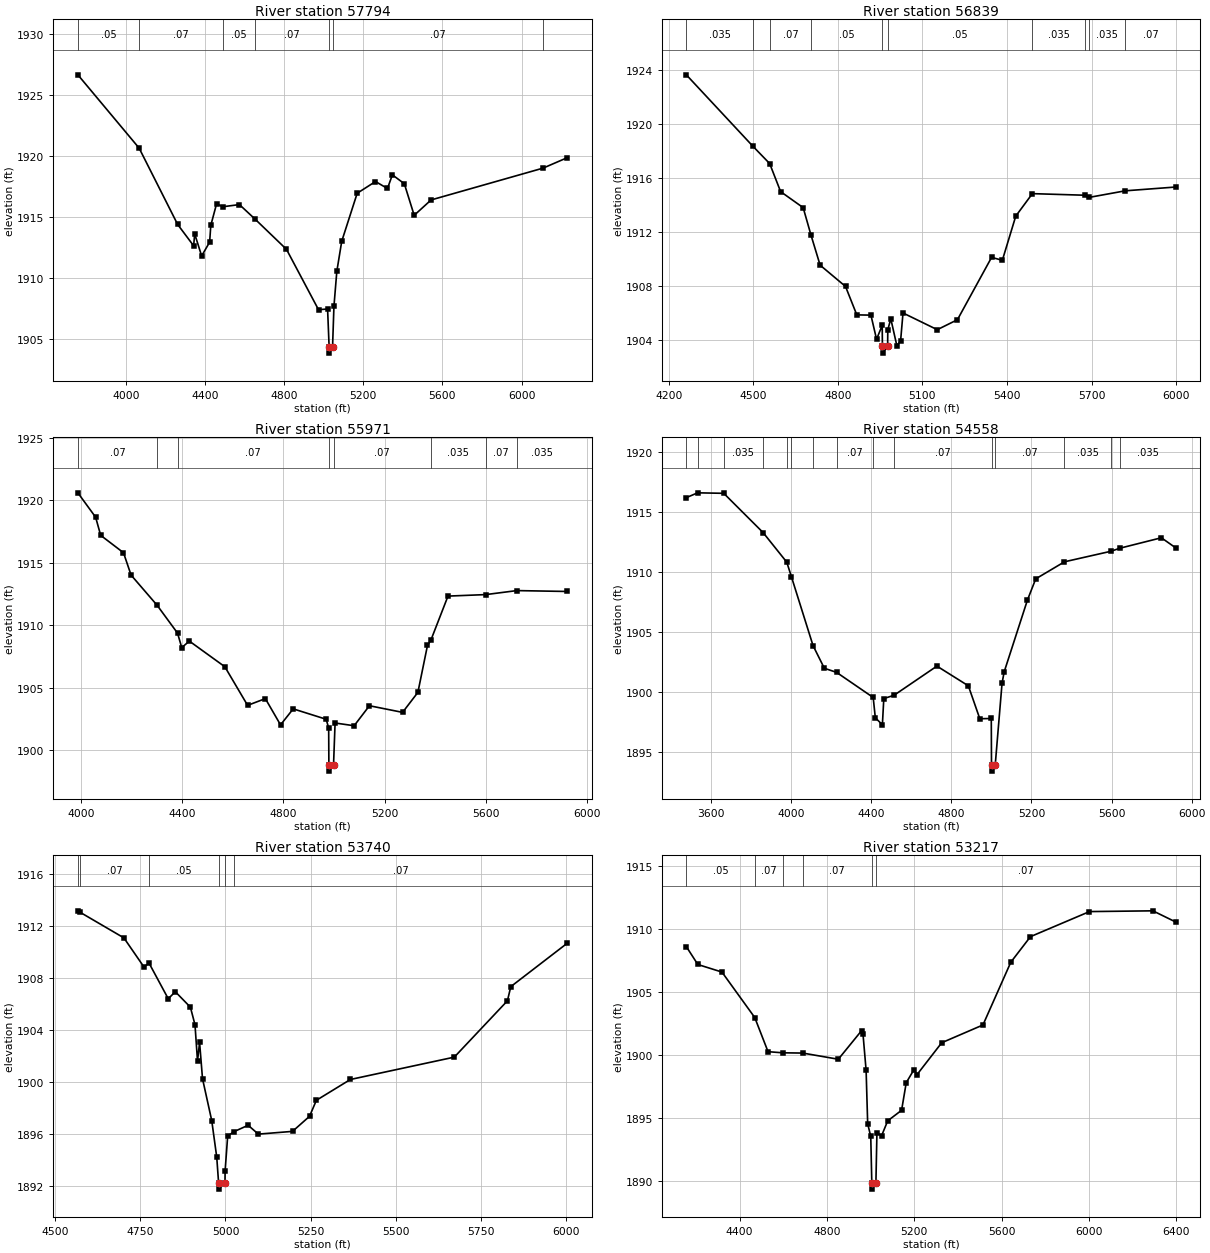
Type RM Length L Ch R = 1 ,57794   ,955,955,955
BEGIN DESCRIPTION:
Mapping XS dc06d625
END DESCRIPTION:
XS GIS Cut Line= 3
      1420905.31      6927691.61      1422098.04       6927379.1
      1423257.61      6926942.31
#Sta/Elev= 30
  3758.2 1926.68  4067.7 1920.67  4262.4 1914.41  4343.2 1912.66  4348.4 1913.64
  4383.6 1911.83    4424 1912.96  4429.8 1914.33  4459.3 1916.12  4489.3 1915.86
  4574.5 1916.04  4652.8 1914.86  4812.3 1912.37  4974.2 1907.42    5020 1907.48
  5027.8 1904.36  5028.3 1903.86  5045.1 1904.36  5052.1 1907.69  5066.7 1910.57
  5091.5 1913.03  5169.6 1916.97  5262.1 1917.93  5322.6 1917.36  5347.4 1918.48
  5407.8 1917.75  5457.6 1915.16  5542.9 1916.42  6108.9 1919.03  6230.3 1919.88
#Mann= 7 ,-1 , 0
  3758.2     .05       0  4067.7     .07       0  4489.3     .05       0
  4652.8     .07       0  5027.8     .07       0  5045.1     .07       0
  6108.9    .035       0
Bank Sta=5027.8,5045.1
XS Rating Curve= 0 ,0
Exp/Cntr=0.3,0.1

Type RM Length L Ch R = 1 ,56839   ,868,868,868
BEGIN DESCRIPTION:
Mapping XS e712c2aa
END DESCRIPTION:
XS GIS Cut Line= 3
      1420920.95      6928056.18       1421639.7      6928087.43
      1422577.24      6927696.79
#Sta/Elev= 30
  4262.6 1923.67  4497.7 1918.39  4558.3 1917.08    4597    1915    4677 1913.81
  4704.8 1911.77  4737.1 1909.54  4827.2 1907.96  4867.2 1905.85  4917.3 1905.83
  4937.3 1904.04  4957.3 1905.07  4958.1 1903.51  4958.6 1903.01  4976.5 1903.51
  4977.2 1904.74  4987.8 1905.56  5009.4 1903.55  5022.6 1903.93  5031.1 1905.99
  5152.6 1904.75  5224.1 1905.49  5345.3 1910.12  5383.4  1909.9    5431 1913.18
  5489.9 1914.85  5678.3 1914.73  5690.9 1914.57  5819.5 1915.06  5997.7 1915.34
#Mann= 10 ,-1 , 0
  4262.6    .035       0  4497.7     .05       0  4558.3     .07       0
  4704.8     .05       0  4958.1     .07       0  4976.5     .05       0
  5489.9    .035       0  5678.3     .07       0  5690.9    .035       0
  5819.5     .07       0
Bank Sta=4958.1,4976.5
XS Rating Curve= 0 ,0
Exp/Cntr=0.3,0.1

Type RM Length L Ch R = 1 ,55971   ,1413,1413,1413
BEGIN DESCRIPTION:
Mapping XS 7c9ba34c
END DESCRIPTION:
XS GIS Cut Line= 4
      1421144.94      6928436.39      1422160.54      6928478.06
      1422624.08      6928420.77      1422780.15      6927999.36
#Sta/Elev= 30
  3987.8 1920.58  4057.9 1918.63  4077.9 1917.18    4168 1915.79    4198    1914
  4301.1 1911.58  4381.5 1909.36  4398.2  1908.2  4428.2 1908.72  4568.4 1906.67
  4658.4 1903.58  4728.5 1904.12  4788.5 1902.02  4838.6  1903.3  4968.7 1902.47
  4978.7 1901.77  4979.5 1898.82    4980 1898.32  4997.9 1898.82    5004 1902.17
  5079.3 1901.95  5139.7 1903.55  5270.7 1903.02  5331.2 1904.62    5369 1908.37
    5383 1908.82  5450.1 1912.32  5599.3 1912.44  5722.1 1912.76  5920.7 1912.69
#Mann= 8 ,-1 , 0
  3987.8     .07       0  4301.1     .05       0  4381.5     .07       0
  4979.5     .07       0  4997.9     .07       0    5383    .035       0
  5599.3     .07       0  5722.1    .035       0
Bank Sta=4979.5,4997.9
XS Rating Curve= 0 ,0
Exp/Cntr=0.3,0.1

Type RM Length L Ch R = 1 ,54558   ,818,818,818
BEGIN DESCRIPTION:
Mapping XS 56e6a0b5
END DESCRIPTION:
XS GIS Cut Line= 4
      1421531.41      6930029.12      1422337.62      6929222.85
      1422530.33      6928873.89      1422811.59      6928014.47
#Sta/Elev= 30
  3476.5 1916.19    3533 1916.59  3663.4 1916.55    3860 1913.28  3978.1 1910.82
  4001.3 1909.61  4109.2 1903.88  4165.7 1901.99  4226.7 1901.65  4409.7 1899.56
  4420.3 1897.87  4455.6 1897.29  4462.7 1899.47  4513.6 1899.74  4727.9 1902.17
  4884.9 1900.53  4942.1 1897.79  4999.4 1897.81  5000.5 1893.93    5001 1893.43
    5019 1893.93  5053.1 1900.73  5063.6 1901.68  5179.8 1907.66  5221.4 1909.43
    5365 1910.85  5597.8 1911.73  5641.4 1911.98  5848.8 1912.85  5919.6 1912.02
#Mann= 15 ,-1 , 0
  3476.5    .035       0    3533     .07       0  3663.4    .035       0
    3860     .07       0  3978.1    .035       0  4001.3     .07       0
  4109.2    .035       0  4226.7     .07       0  4409.7    .035       0
  4513.6     .07       0  5000.5     .07       0    5019     .07       0
    5365    .035       0  5597.8     .07       0  5641.4    .035       0
Bank Sta=5000.5,5019
XS Rating Curve= 0 ,0
Exp/Cntr=0.3,0.1

Type RM Length L Ch R = 1 ,53740   ,523,523,523
BEGIN DESCRIPTION:
China Creek 32.0
END DESCRIPTION:
XS GIS Cut Line= 3
        1422555.      6929938.01        1422805.        6929588.
      1422872.12      6928582.96
#Sta/Elev= 30
  4566.3 1913.15  4572.7 1913.04  4701.5 1911.07  4760.5 1908.83  4775.4 1909.13
  4831.8 1906.39  4852.6 1906.93  4896.9 1905.74  4910.4 1904.39  4917.8  1901.6
  4923.9 1903.03  4932.5 1900.24  4959.6 1897.02  4974.3 1894.21  4979.7 1892.25
  4980.2 1891.75  4998.5 1892.25  4998.9 1893.15  5006.4 1895.82  5024.1 1896.16
  5066.5 1896.66  5096.6 1895.98  5196.9 1896.19    5247 1897.35    5267 1898.58
  5366.9 1900.18  5672.3  1901.9  5828.3 1906.23  5838.3 1907.32  6003.7 1910.65
#Mann= 6 ,-1 , 0
  4566.3    .035       0  4572.7     .07       0  4775.4     .05       0
  4979.7     .05       0  4998.5     .05       0  5024.1     .07       0
Bank Sta=4979.7,4998.5
XS Rating Curve= 0 ,0
Exp/Cntr=0.3,0.1

Type RM Length L Ch R = 1 ,53217   ,1166,1166,1166
BEGIN DESCRIPTION:
Mapping XS 6b8d4815
END DESCRIPTION:
XS GIS Cut Line= 4
      1422913.82        6929960.      1423257.54      6929394.07
      1422861.71      6929012.13      1422920.74      6927984.32
#Sta/Elev= 30
  4155.6 1908.64  4208.3 1907.22  4318.8 1906.62  4469.2 1903.01    4530  1900.3
  4597.8 1900.21  4688.9 1900.19    4852  1899.7  4958.3 1901.96  4965.2 1901.69
  4979.4 1898.82  4986.6 1894.58  5000.7 1893.57  5005.5 1889.89    5006 1889.39
  5024.3 1889.89    5029 1893.87  5050.1 1893.62  5078.4 1894.81    5142 1895.65
  5163.3 1897.84  5198.6 1898.87  5212.7 1898.48  5325.9 1901.01  5514.8 1902.42
  5642.4  1907.4  5732.5 1909.43    6003 1911.42  6293.4 1911.48  6397.3  1910.6
#Mann= 6 ,-1 , 0
  4155.6     .05       0  4469.2     .07       0  4597.8     .05       0
  4688.9     .07       0  5005.5     .07       0  5024.3     .07       0
Bank Sta=5005.5,5024.3
XS Rating Curve= 0 ,0
Exp/Cntr=0.3,0.1

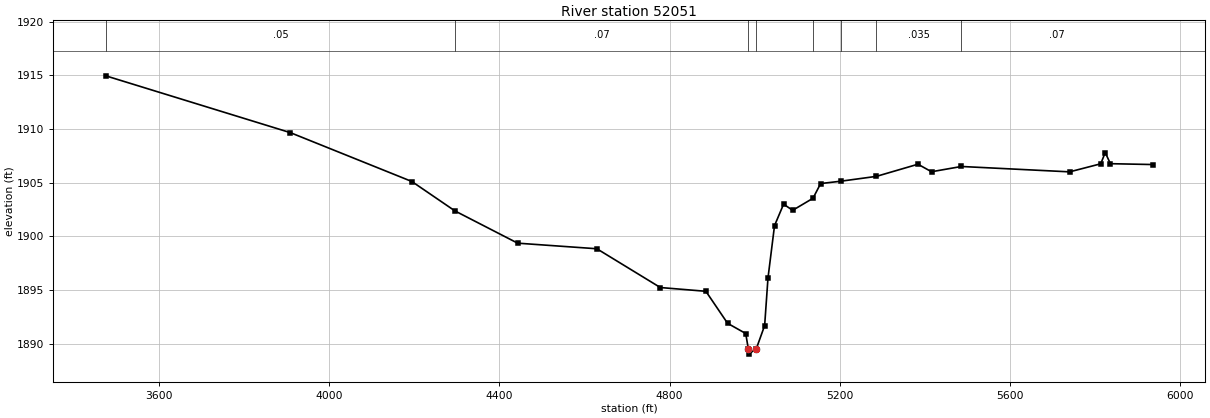
Type RM Length L Ch R = 1 ,52051   ,843,843,843
BEGIN DESCRIPTION:
Mapping XS 9d4f4fa5
END DESCRIPTION:
XS GIS Cut Line= 4
      1422634.93       6930357.9      1423504.07      6929251.71
      1423726.29       6929116.3      1423972.23      6928361.16
#Sta/Elev= 30
  3474.9 1914.95  3908.7 1909.66  4194.3 1905.11  4295.6 1902.37  4442.9 1899.37
    4629 1898.85  4778.2 1895.24  4885.2 1894.89  4936.2 1891.91  4978.8 1890.96
  4984.9 1889.54  4985.4 1889.04  5003.7 1889.54  5023.3  1891.7  5031.1 1896.11
  5046.5    1901  5067.8    1903  5089.2 1902.43  5136.9 1903.55  5154.9 1904.92
  5202.5 1905.14    5286 1905.59  5383.6 1906.72  5415.5 1906.02  5485.7 1906.51
    5740 1906.01  5813.2 1906.76  5823.7 1907.81  5835.8 1906.77  5936.1 1906.69
#Mann= 8 ,-1 , 0
  3474.9     .05       0  4295.6     .07       0  4984.9     .07       0
  5003.7     .07       0  5136.9    .035       0  5202.5     .07       0
    5286    .035       0  5485.7     .07       0
Bank Sta=4984.9,5003.7
XS Rating Curve= 0 ,0
Exp/Cntr=0.3,0.1