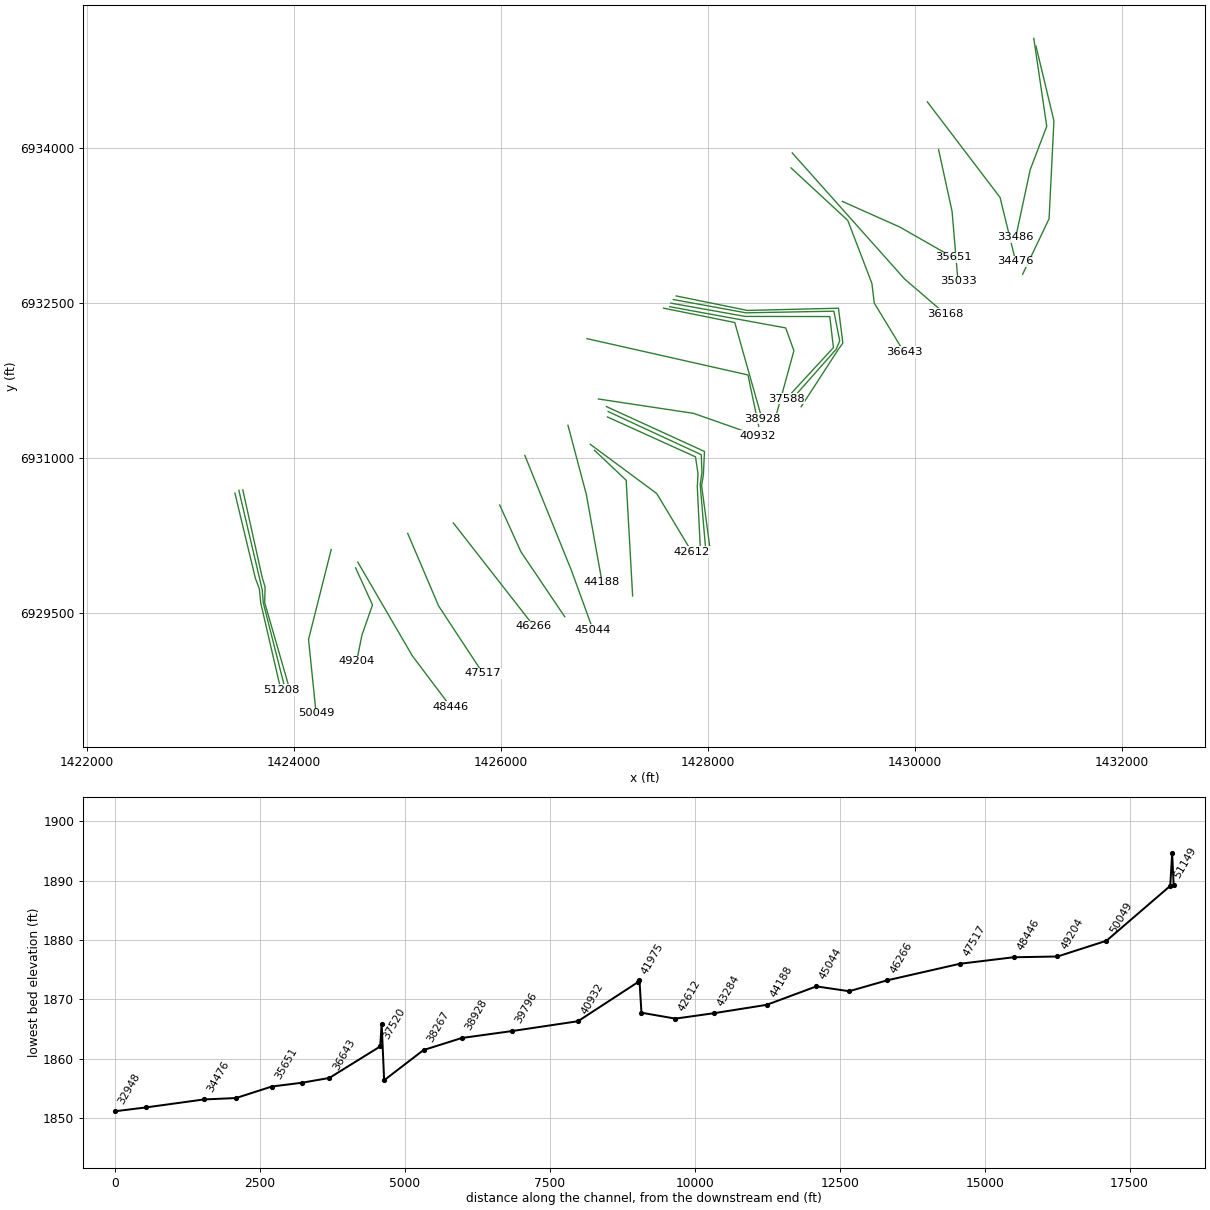
HEC-RAS study China Creek.prj: China Creek Base Level Engineering

--- China Creek.g01 (geometry) --- (continued)

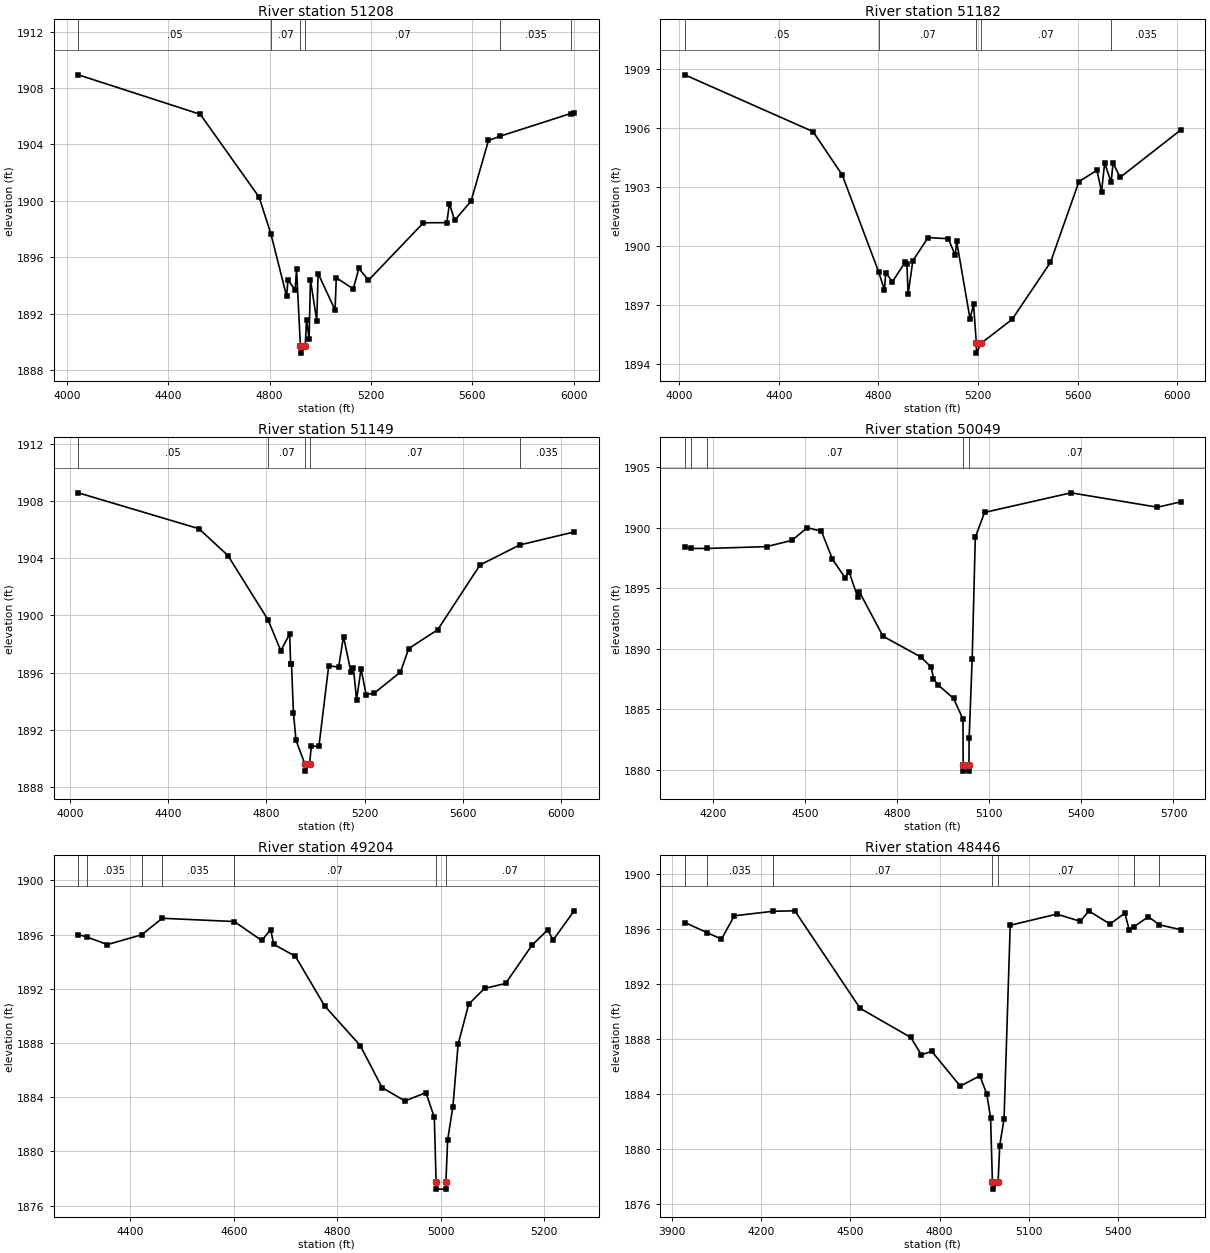
Type RM Length L Ch R = 1 ,51208   ,26,26,26
BEGIN DESCRIPTION:
Mapping XS 40fddd3d
END DESCRIPTION:
XS GIS Cut Line= 5
      1423427.69      6930661.39       1423625.6      6929838.52
      1423663.79      6929737.82      1423677.68      6929598.94
      1423872.13      6928758.65
#Sta/Elev= 30
  4045.3 1908.94  4526.3 1906.14  4758.5 1900.26  4805.2 1897.64  4867.1 1893.22
  4872.2 1894.39  4900.8 1893.67  4906.1 1895.16  4921.5 1889.69    4922 1889.19
  4940.4 1889.69  4945.7 1891.54  4955.7  1890.2  4961.1 1894.39  4985.9 1891.49
  4991.2 1894.84  5058.1 1892.26  5063.1 1894.54  5129.8 1893.75  5152.2  1895.2
  5189.8 1894.36  5406.7 1898.44    5499 1898.45  5509.4  1899.8  5529.9 1898.61
  5594.7 1899.98  5663.4 1904.28  5710.2 1904.59  5987.1 1906.19  6001.4 1906.24
#Mann= 6 ,-1 , 0
  4045.3     .05       0  4805.2     .07       0  4921.5     .07       0
  4940.4     .07       0  5710.2    .035       0  5987.1     .07       0
Bank Sta=4921.5,4940.4
XS Rating Curve= 0 ,0
Exp/Cntr=0.3,0.1

Type RM Length L Ch R = 1 ,51182   ,33,33,33
BEGIN DESCRIPTION:
Mapping XS 37f57261
END DESCRIPTION:
XS GIS Cut Line= 5
      1423465.88      6930689.18      1423667.26      6929831.57
      1423691.57      6929727.41      1423701.99      6929602.41
      1423917.11      6928752.33
#Sta/Elev= 30
  4023.1 1908.72  4537.9 1905.83  4654.8 1903.63  4800.7 1898.71  4824.5 1897.78
  4829.6 1898.65  4856.3 1898.19  4908.4  1899.2  4914.5 1899.09  4919.6 1897.57
  4938.5 1899.26  4999.5 1900.44  5080.6 1900.38  5109.1 1899.53  5114.1 1900.27
  5167.9 1896.31  5182.2 1897.04  5193.4 1895.06  5193.9 1894.56  5212.3 1895.06
  5337.1 1896.28  5490.9 1899.18  5605.2 1903.29  5677.4 1903.86  5695.9 1902.77
  5708.3 1904.24  5734.4 1903.25  5742.1 1904.24  5770.2  1903.5  6013.3 1905.91
#Mann= 5 ,-1 , 0
  4023.1     .05       0  4800.7     .07       0  5193.4     .07       0
  5212.3     .07       0  5734.4    .035       0
Bank Sta=5193.4,5212.3
XS Rating Curve= 0 ,0
Exp/Cntr=0.3,0.1

Type RM Length L Ch R = 1 ,51149   ,1100,1100,1100
BEGIN DESCRIPTION:
Mapping XS 219f0f71
END DESCRIPTION:
XS GIS Cut Line= 5
      1423504.08      6930692.65      1423691.57      6929845.46
      1423719.35      6929755.19      1423715.87      6929602.41
      1423965.88      6928734.35
#Sta/Elev= 30
  4034.4 1908.58  4525.1 1906.07  4643.4 1904.19  4806.3  1899.7  4858.5 1897.53
  4894.6  1898.7  4898.5 1896.61  4902.1 1896.61  4909.9  1893.2  4920.4 1891.26
  4956.6  1889.6  4957.1  1889.1  4975.5  1889.6  4983.1 1890.86  5013.7 1890.83
  5053.7 1896.49  5093.8 1896.37  5113.8 1898.52  5143.8 1896.06  5154.3 1896.32
  5166.9 1894.09  5185.2 1896.26    5206 1894.45  5239.5 1894.57  5345.7 1896.03
  5379.4 1897.68  5497.4    1899  5669.6 1903.53  5831.1 1904.93  6052.7 1905.84
#Mann= 5 ,-1 , 0
  4034.4     .05       0  4806.3     .07       0  4956.6     .07       0
  4975.5     .07       0  5831.1    .035       0
Bank Sta=4956.6,4975.5
XS Rating Curve= 0 ,0
Exp/Cntr=0.3,0.1

Type RM Length L Ch R = 1 ,50049   ,845,845,845
BEGIN DESCRIPTION:
Mapping XS 26a4c87e
END DESCRIPTION:
XS GIS Cut Line= 3
      1424358.23      6930116.28      1424139.49      6929248.24
       1424212.4      6928533.03
#Sta/Elev= 30
  4109.1  1898.4  4130.1 1898.29  4182.6 1898.29  4375.5 1898.44    4458 1898.96
  4507.7 1900.01    4554 1899.71  4589.9 1897.39    4631 1895.86  4643.6 1896.36
  4672.1 1894.26  4677.2 1894.71  4754.3 1891.03  4877.5 1889.31  4911.7 1888.46
  4918.6 1887.52  4932.3 1887.03  4983.9 1885.89  5014.6 1884.18  5015.2 1880.37
  5015.7 1879.87  5033.6 1879.87  5034.1 1880.37  5034.7 1882.61  5044.7 1889.18
  5054.8 1899.21  5084.9 1901.27  5366.4 1902.89  5647.8  1901.7  5723.2 1902.14
#Mann= 5 ,-1 , 0
  4109.1     .07       0  4130.1    .035       0  4182.6     .07       0
  5015.2     .07       0  5034.1     .07       0
Bank Sta=5015.2,5034.1
XS Rating Curve= 0 ,0
Exp/Cntr=0.3,0.1

Type RM Length L Ch R = 1 ,49204   ,758,758,758
BEGIN DESCRIPTION:
China Creek 28.0
END DESCRIPTION:
XS GIS Cut Line= 4
      1424594.36      6929939.19      1424757.54      6929581.57
        1424655.        6929288.        1424605.      6929038.01
#Sta/Elev= 30
  4299.3 1896.01  4315.7 1895.83  4355.6 1895.27  4421.7 1895.99  4461.6 1897.21
  4600.9 1896.97    4654 1895.57  4671.5 1896.38    4677 1895.29    4719 1894.41
  4775.8 1890.74  4844.5 1887.82  4886.8 1884.71    4931 1883.73  4971.6 1884.34
  4987.8 1882.52  4991.3 1877.72  4991.8 1877.22  5009.7 1877.22  5010.2 1877.72
  5013.6 1880.85  5023.8 1883.31  5033.9 1887.92  5054.3 1890.87  5084.9 1892.03
  5125.7  1892.4  5176.7 1895.22  5207.3 1896.36  5217.5  1895.6  5258.3 1897.76
#Mann= 7 ,-1 , 0
  4299.3     .07       0  4315.7    .035       0  4421.7     .07       0
  4461.6    .035       0  4600.9     .07       0  4991.3     .07       0
  5010.2     .07       0
Bank Sta=4991.3,5010.2
XS Rating Curve= 0 ,0
Exp/Cntr=0.3,0.1

Type RM Length L Ch R = 1 ,48446   ,929,929,929
BEGIN DESCRIPTION:
Mapping XS c7596fbb
END DESCRIPTION:
XS GIS Cut Line= 3
      1424615.16      6929994.81      1425142.96      6929088.52
      1425514.46       6928595.5
#Sta/Elev= 30
    3944 1896.48  4019.5 1895.74  4067.3 1895.27  4110.3 1896.97  4241.3  1897.3
  4313.8 1897.33  4533.1 1890.24  4703.5 1888.12  4738.8 1886.86  4773.8 1887.11
  4869.8 1884.58  4935.5 1885.33  4958.7 1884.01  4971.5 1882.27  4977.7 1877.59
  4978.2 1877.09  4996.8 1877.59  5002.1 1880.25  5016.7 1882.18  5037.5 1896.28
  5193.8 1897.09  5272.8 1896.57  5301.9 1897.32  5372.7 1896.37  5422.7 1897.16
  5437.2 1895.96    5453 1896.17  5501.8  1896.9  5539.1 1896.31  5610.1 1895.96
#Mann= 7 ,-1 , 0
    3944     .07       0  4019.5    .035       0  4241.3     .07       0
  4977.7     .07       0  4996.8     .07       0    5453    .035       0
  5539.1     .07       0
Bank Sta=4977.7,4996.8
XS Rating Curve= 0 ,0
Exp/Cntr=0.3,0.1

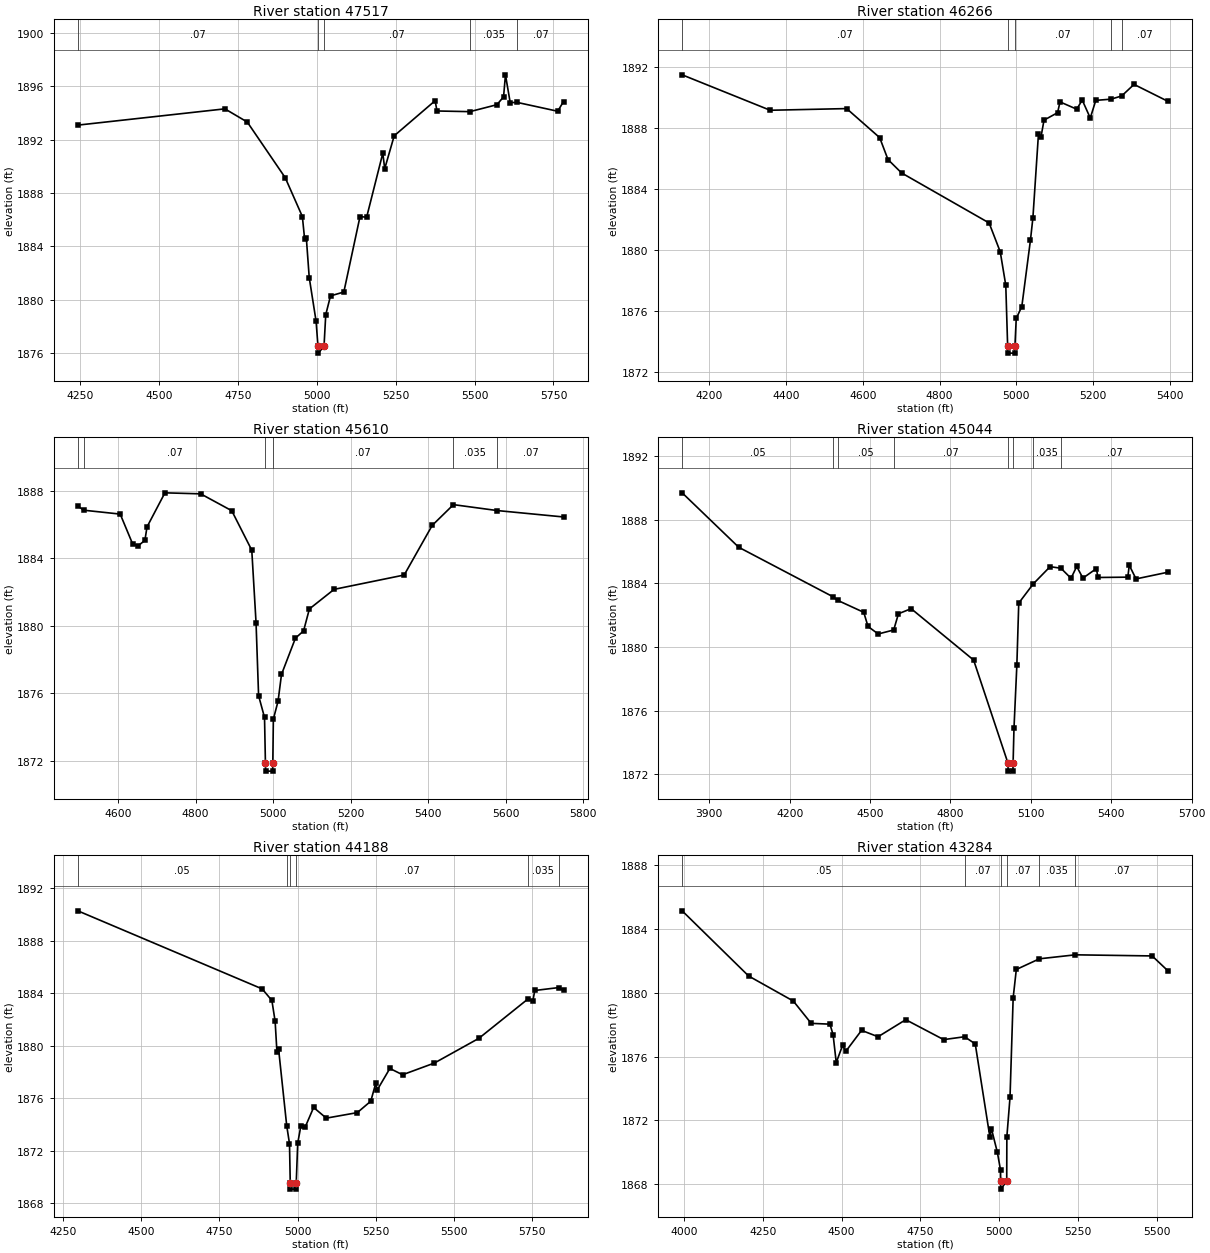
Type RM Length L Ch R = 1 ,47517   ,1251,1251,1251
BEGIN DESCRIPTION:
Mapping XS 5d7375cd
END DESCRIPTION:
XS GIS Cut Line= 3
      1425097.81      6930272.57      1425396.43      6929571.16
      1425823.13      6928922.44
#Sta/Elev= 30
  4242.9 1893.08  4708.9  1894.3  4779.8 1893.31    4900 1889.14  4954.3 1886.23
  4961.5 1884.54    4967 1884.59  4976.1 1881.65  4997.8 1878.38  5003.8 1876.49
  5004.3 1875.99  5022.9 1876.49  5028.4 1878.87  5043.5 1880.28  5085.7 1880.57
  5136.9 1886.22    5158 1886.18  5209.2 1890.98  5215.2 1889.81  5245.3 1892.28
  5374.9 1894.91  5380.9 1894.14  5485.1 1894.09  5570.7 1894.61  5591.8  1895.2
  5597.8 1896.85  5612.8 1894.77  5635.4 1894.78  5763.4 1894.12  5781.7 1894.85
#Mann= 5 ,-1 , 0
  4242.9     .07       0  5003.8     .07       0  5022.9     .07       0
  5485.1    .035       0  5635.4     .07       0
Bank Sta=5003.8,5022.9
XS Rating Curve= 0 ,0
Exp/Cntr=0.3,0.1

Type RM Length L Ch R = 1 ,46266   ,656,656,656
BEGIN DESCRIPTION:
Mapping XS 2c40fa25
END DESCRIPTION:
XS GIS Cut Line= 3
      1425538.78      6930373.26      1426070.04      6929692.69
      1426316.54      6929376.75
#Sta/Elev= 30
    4130 1891.51  4359.1 1889.18  4558.1 1889.29  4644.1 1887.38  4665.7 1885.94
    4701 1885.06  4928.9 1881.77  4957.9 1879.87  4972.3 1877.67  4977.1 1873.71
  4977.6 1873.21  4995.7 1873.21  4996.2 1873.71  4999.5 1875.49    5014 1876.27
  5036.6 1880.66  5042.9 1882.11  5057.4 1887.64  5063.7 1887.39  5071.8 1888.53
  5107.1 1889.02  5113.5 1889.73  5156.9 1889.25  5171.3 1889.85  5192.2 1888.67
  5206.6 1889.83  5246.3 1889.91  5273.9 1890.12  5306.1 1890.88  5394.1 1889.77
#Mann= 5 ,-1 , 0
    4130     .07       0  4977.1     .07       0  4996.2     .07       0
  5246.3    .035       0  5273.9     .07       0
Bank Sta=4977.1,4996.2
XS Rating Curve= 0 ,0
Exp/Cntr=0.3,0.1

Type RM Length L Ch R = 1 ,45610   ,566,566,566
BEGIN DESCRIPTION:
Mapping XS 28a79b71
END DESCRIPTION:
XS GIS Cut Line= 3
      1425986.71      6930546.85      1426191.57      6930095.46
      1426615.18      6929466.99
#Sta/Elev= 30
  4495.9 1887.09  4511.2 1886.84  4605.3 1886.61  4637.4 1884.84  4651.5 1884.73
    4669 1885.05  4674.5 1885.85  4720.7 1887.87    4813 1887.81  4893.2 1886.81
  4944.9 1884.47  4955.9 1880.18  4962.5 1875.85  4977.8 1874.56  4980.1 1871.88
  4980.6 1871.38  4998.7 1871.38  4999.2 1871.88  5000.6 1874.46  5012.7 1875.52
  5021.6 1877.11  5057.6 1879.26  5078.6 1879.69  5093.6 1880.99  5157.4 1882.15
  5338.3    1883  5410.6 1885.94  5465.4 1887.17  5578.2 1886.82  5749.5 1886.44
#Mann= 6 ,-1 , 0
  4495.9     .05       0  4511.2     .07       0  4980.1     .07       0
  4999.2     .07       0  5465.4    .035       0  5578.2     .07       0
Bank Sta=4980.1,4999.2
XS Rating Curve= 0 ,0
Exp/Cntr=0.3,0.1

Type RM Length L Ch R = 1 ,45044   ,856,856,856
BEGIN DESCRIPTION:
Mapping XS b348a78f
END DESCRIPTION:
XS GIS Cut Line= 3
      1426229.76      6931026.03      1426681.15      6929911.44
       1426889.5      6929338.48
#Sta/Elev= 30
  3798.9 1889.68  4009.9 1886.26  4360.3 1883.16  4379.4 1882.92  4476.5 1882.17
  4492.4 1881.28  4530.4 1880.81  4588.2 1881.06  4605.9 1882.08  4653.3  1882.4
  4886.4 1879.17  5014.6 1872.69  5015.1 1872.19  5033.2 1872.19  5033.7 1872.69
    5037 1874.88  5047.7 1878.84  5054.8 1882.75  5109.1 1883.96  5171.8 1885.04
  5212.2 1884.94  5249.8 1884.31  5271.1 1885.05  5294.2 1884.32  5344.7 1884.92
  5350.1 1884.36  5461.8 1884.38  5467.1 1885.13  5492.4 1884.27  5611.1 1884.69
#Mann= 8 ,-1 , 0
  3798.9     .05       0  4360.3     .07       0  4379.4     .05       0
  4588.2     .07       0  5014.6     .07       0  5033.7     .07       0
  5109.1    .035       0  5212.2     .07       0
Bank Sta=5014.6,5033.7
XS Rating Curve= 0 ,0
Exp/Cntr=0.3,0.1

Type RM Length L Ch R = 1 ,44188   ,904,904,904
BEGIN DESCRIPTION:
Mapping XS 011754f7
END DESCRIPTION:
XS GIS Cut Line= 3
      1426646.44      6931317.64      1426823.51      6930651.02
      1426976.05      6929801.65
#Sta/Elev= 30
  4297.3 1890.26  4886.7 1884.32  4917.7 1883.44  4928.1 1881.85  4933.8 1879.55
    4939 1879.77  4965.1 1873.92    4974 1872.55  4976.4 1869.59  4976.9 1869.09
  4995.1 1869.09  4995.6 1869.59  5000.3 1872.59  5010.4  1873.9  5024.7 1873.84
  5051.1  1875.3  5091.7 1874.49  5190.8 1874.91  5233.9 1875.78  5249.6 1877.13
  5254.7 1876.64  5294.9 1878.27  5335.5 1877.79  5437.1 1878.68  5579.4 1880.56
  5735.1 1883.53  5752.1 1883.42  5758.2  1884.2  5834.1 1884.42    5850 1884.21
#Mann= 6 ,-1 , 0
  4297.3     .05       0  4965.1     .07       0  4976.4     .07       0
  4995.6     .07       0  5735.1    .035       0  5834.1     .07       0
Bank Sta=4976.4,4995.6
XS Rating Curve= 0 ,0
Exp/Cntr=0.3,0.1

Type RM Length L Ch R = 1 ,43284   ,672,672,672
BEGIN DESCRIPTION:
Mapping XS ced188df
END DESCRIPTION:
XS GIS Cut Line= 3
      1426903.39      6931074.62      1427208.93      6930786.44
      1427271.43      6929668.39
#Sta/Elev= 30
  3994.7 1885.15  4205.5 1881.06  4347.1 1879.49  4403.8 1878.09  4463.2 1878.04
  4473.2 1877.38  4483.2 1875.63  4503.3 1876.71  4513.3 1876.33  4563.4 1877.65
  4615.8 1877.25  4703.6 1878.32  4823.8 1877.07  4890.1 1877.25  4923.9  1876.8
  4970.2 1870.97  4975.2 1871.48    4994    1870  5004.1 1868.88  5004.5 1868.19
    5005 1867.69  5023.7 1868.19  5024.1 1870.97  5034.1 1873.44  5044.1 1879.69
  5054.1 1881.47  5127.3 1882.14  5241.2 1882.39  5484.8 1882.32  5534.5 1881.39
#Mann= 6 ,-1 , 0
  3994.7     .05       0  4890.1     .07       0  5004.5     .07       0
  5023.7     .07       0  5127.3    .035       0  5241.2     .07       0
Bank Sta=5004.5,5023.7
XS Rating Curve= 0 ,0
Exp/Cntr=0.3,0.1

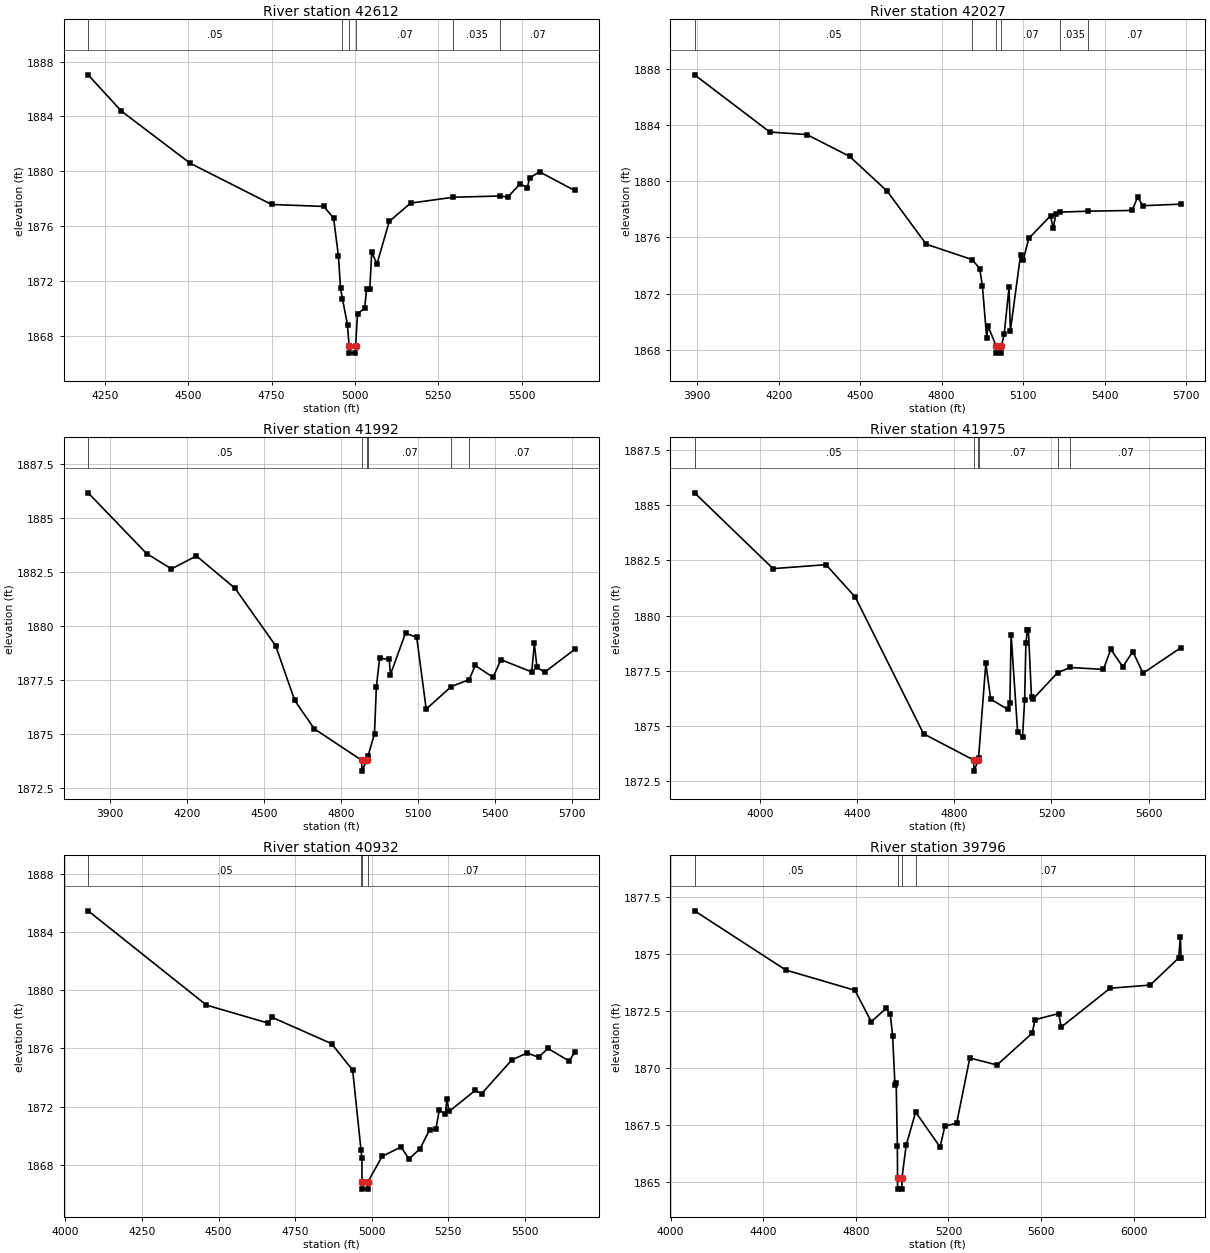
Type RM Length L Ch R = 1 ,42612   ,585,585,585
BEGIN DESCRIPTION:
Mapping XS 6fe23086
END DESCRIPTION:
XS GIS Cut Line= 3
      1426861.68      6931133.68      1427504.07      6930657.96
      1427844.07      6930092.46
#Sta/Elev= 30
  4199.5 1887.03  4299.2 1884.39  4505.8 1880.59    4750 1877.59  4906.5 1877.45
  4935.8 1876.59  4950.2 1873.86  4956.6 1871.48  4962.4 1870.73  4977.5 1868.81
  4982.4 1867.27  4982.9 1866.77  5001.2 1866.77  5001.7 1867.27  5007.5 1869.64
  5028.9 1870.03  5034.7 1871.42  5044.4 1871.47  5050.2 1874.12  5065.8 1873.26
  5102.7 1876.36  5166.8 1877.69  5295.2 1878.12  5436.3 1878.21  5458.2 1878.12
  5495.1  1879.1  5516.5 1878.82  5523.9 1879.52  5553.4 1879.97  5658.7 1878.61
#Mann= 6 ,-1 , 0
  4199.5     .05       0  4962.4     .07       0  4982.4     .07       0
  5001.7     .07       0  5295.2    .035       0  5436.3     .07       0
Bank Sta=4982.4,5001.7
XS Rating Curve= 0 ,0
Exp/Cntr=0.3,0.1

Type RM Length L Ch R = 1 ,42027   ,35,35,35
BEGIN DESCRIPTION:
Mapping XS 1eae30e2
END DESCRIPTION:
XS GIS Cut Line= 5
      1427028.37      6931397.55      1427879.07      6931012.13
      1427903.37      6930848.94      1427896.43      6930723.94
      1427924.21      6930157.94
#Sta/Elev= 30
  3890.6 1887.56  4167.5 1883.49  4304.1 1883.31  4461.1 1881.76  4599.7 1879.28
  4743.2 1875.51  4912.7 1874.41  4939.9 1873.78    4950 1872.56  4965.9 1868.82
    4971 1869.67  5000.8 1868.26  5001.3 1867.76  5019.6 1867.76  5020.1 1868.26
  5030.5 1869.15    5048 1872.43    5053 1869.35  5090.6 1874.76  5100.6  1874.4
  5120.7 1875.92  5200.8 1877.53  5210.8 1876.64  5220.8 1877.69  5235.3 1877.79
  5339.6 1877.86  5501.1 1877.91  5521.1 1878.85  5541.2 1878.25  5681.4 1878.36
#Mann= 6 ,-1 , 0
  3890.6     .05       0  4912.7     .07       0  5000.8     .07       0
  5020.1     .07       0  5235.3    .035       0  5339.6     .07       0
Bank Sta=5000.8,5020.1
XS Rating Curve= 0 ,0
Exp/Cntr=0.3,0.1

Type RM Length L Ch R = 1 ,41992   ,17,17,17
BEGIN DESCRIPTION:
Mapping XS 5deec8ae
END DESCRIPTION:
XS GIS Cut Line= 5
      1427035.29      6931449.64      1427934.62      6931032.96
      1427941.57      6930859.35      1427924.21      6930744.77
      1427976.17      6930131.58
#Sta/Elev= 30
  3813.7 1886.18  4041.5 1883.37  4138.6 1882.66  4235.8 1883.26  4386.5 1881.76
  4544.7  1879.1    4619 1876.57  4695.1 1875.26  4880.3  1873.8  4880.8  1873.3
  4899.6  1873.8  4904.1 1873.98  4929.9 1875.03  4937.2 1877.21    4950 1878.53
  4987.1 1878.47  4992.1 1877.77  5050.8 1879.69  5094.5 1879.49  5131.4 1876.17
  5228.7 1877.21  5299.3 1877.54  5322.1 1878.19  5392.3 1877.64  5422.5 1878.46
  5542.9 1877.89  5552.9 1879.21    5563 1878.11  5593.1 1877.88  5709.9 1878.93
#Mann= 6 ,-1 , 0
  3813.7     .05       0  4880.3     .07       0  4899.6     .05       0
  4904.1     .07       0  5228.7    .035       0  5299.3     .07       0
Bank Sta=4880.3,4899.6
XS Rating Curve= 0 ,0
Exp/Cntr=0.3,0.1

Type RM Length L Ch R = 1 ,41975   ,1043,1043,1043
BEGIN DESCRIPTION:
Mapping XS c71c281d
END DESCRIPTION:
XS GIS Cut Line= 5
      1427017.97      6931498.23      1427965.87      6931064.21
      1427955.46      6930838.52       1427938.1      6930734.35
      1428021.19      6930111.14
#Sta/Elev= 30
  3731.1 1885.55  4054.1 1882.12  4272.2  1882.3  4392.7 1880.83  4673.7 1874.65
  4880.3 1873.46  4880.8 1872.96  4899.6 1873.46  4900.1 1873.56    4930 1877.83
    4950 1876.22  5020.4 1875.75  5029.1 1876.04  5034.2 1879.13  5060.9 1874.73
  5081.2 1874.51  5089.9 1876.19    5095 1878.76  5100.8 1879.33  5105.2 1879.33
  5118.1  1876.3  5123.1 1876.21  5225.3 1877.41  5276.9 1877.65  5414.2 1877.56
  5444.5 1878.47  5493.9 1877.68  5535.3 1878.37  5577.1 1877.39  5733.9 1878.55
#Mann= 6 ,-1 , 0
  3731.1     .05       0  4880.3     .07       0  4899.6     .05       0
  4900.1     .07       0  5225.3    .035       0  5276.9     .07       0
Bank Sta=4880.3,4899.6
XS Rating Curve= 0 ,0
Exp/Cntr=0.3,0.1

Type RM Length L Ch R = 1 ,40932   ,1136,1136,1136
BEGIN DESCRIPTION:
Mapping XS 44ba6ece
END DESCRIPTION:
XS GIS Cut Line= 3
      1426941.57      6931571.16      1427861.71      6931432.27
      1428481.66      6931214.07
#Sta/Elev= 30
  4074.4 1885.46  4460.6 1878.98  4662.2 1877.74  4674.6 1878.14  4868.9 1876.33
  4937.8 1874.51  4964.9 1869.04  4967.8 1868.46  4968.3 1866.83  4968.8 1866.33
  4987.1 1866.33  4987.6 1866.83  5033.9 1868.58  5095.8 1869.23  5121.5  1868.4
  5157.8 1869.11  5188.7  1870.4  5209.1 1870.44  5220.5 1871.76  5240.1 1871.49
  5245.4 1872.52  5252.3 1871.67  5338.2 1873.12  5358.3 1872.88  5456.8  1875.2
  5506.7 1875.69  5544.4  1875.4  5575.3    1876  5644.5 1875.13  5662.2 1875.74
#Mann= 4 ,-1 , 0
  4074.4     .05       0  4964.9     .07       0  4968.3     .07       0
  4987.6     .07       0
Bank Sta=4968.3,4987.6
XS Rating Curve= 0 ,0
Exp/Cntr=0.3,0.1

Type RM Length L Ch R = 1 ,39796   ,868,868,868
BEGIN DESCRIPTION:
Mapping XS 77e6800d
END DESCRIPTION:
XS GIS Cut Line= 3
      1426830.49      6932154.48      1428386.01       6931803.8
       1428490.1      6931307.66
#Sta/Elev= 30
  4103.6  1876.9  4497.8  1874.3  4796.3 1873.41  4866.8 1872.03  4931.1 1872.62
  4948.8 1872.38  4959.1 1871.41  4969.2 1869.24  4974.4 1869.32  4979.6 1866.59
  4980.2 1865.18  4980.7 1864.68    4999 1864.68  4999.5 1865.18  5017.6 1866.61
  5058.5 1868.06  5164.1 1866.53  5184.6 1867.44  5235.8 1867.58  5292.4 1870.44
  5410.1 1870.13  5562.1 1871.53  5574.1 1872.12  5676.6 1872.39  5686.9 1871.79
  5898.2  1873.5  6071.9 1873.64  6194.5 1874.83  6202.1 1875.73  6205.1 1874.81
#Mann= 4 ,-1 , 0
  4103.6     .05       0  4980.2     .05       0  4999.5     .05       0
  5058.5     .07       0
Bank Sta=4980.2,4999.5
XS Rating Curve= 0 ,0
Exp/Cntr=0.3,0.1

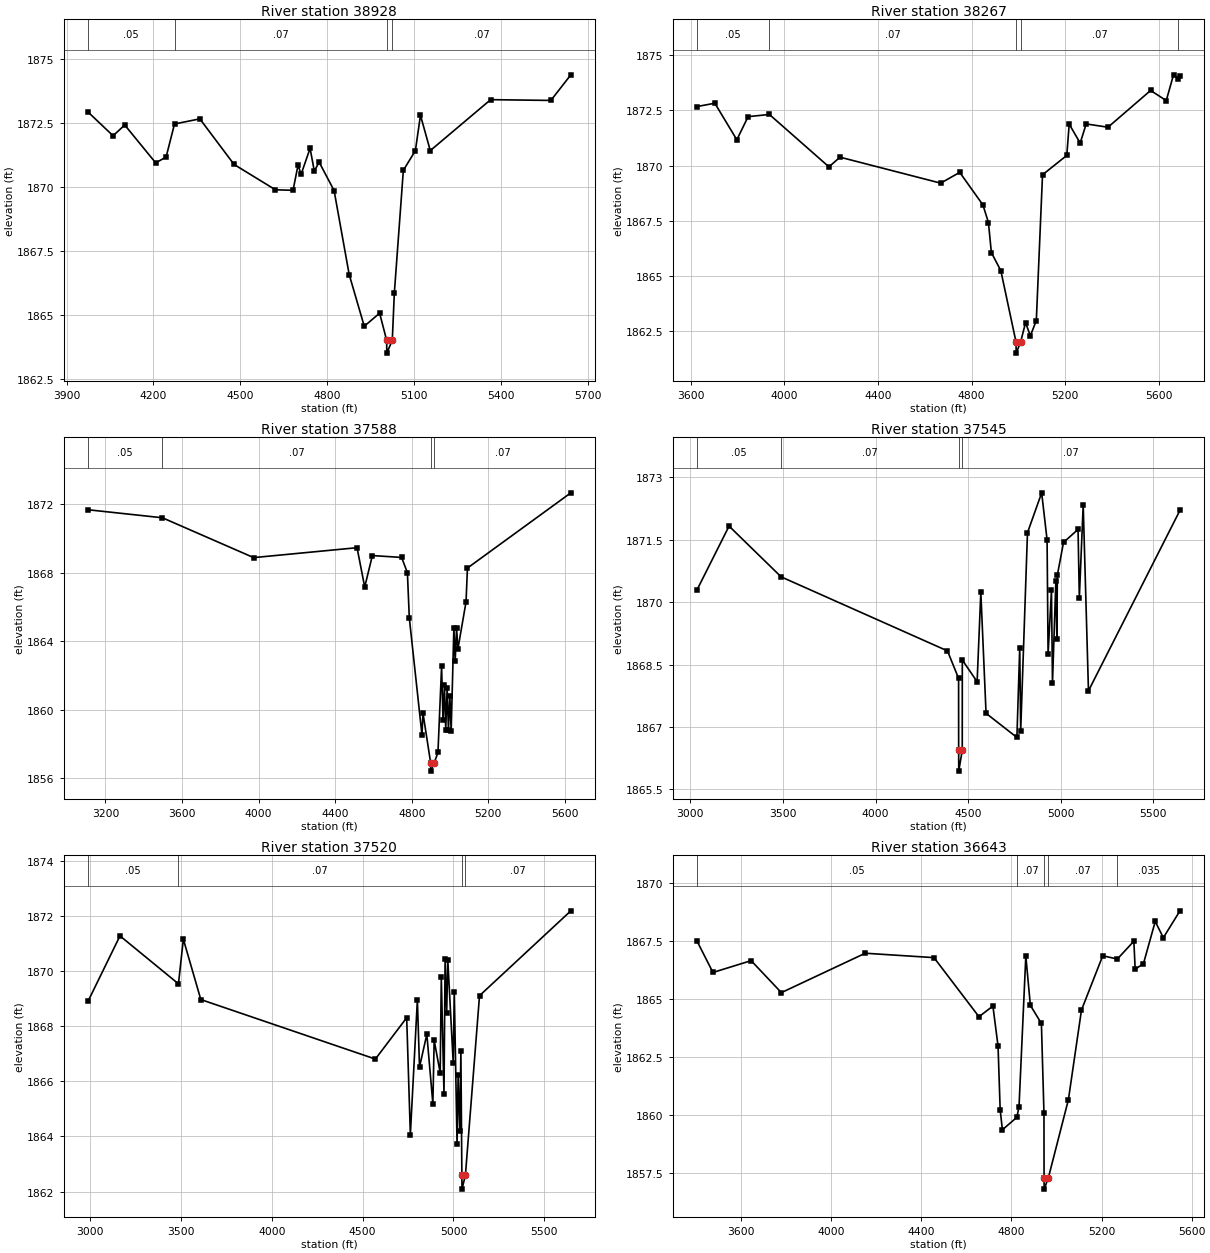
Type RM Length L Ch R = 1 ,38928   ,661,661,661
BEGIN DESCRIPTION:
Mapping XS bea14b34
END DESCRIPTION:
XS GIS Cut Line= 4
      1427570.44      6932449.24      1428258.86      6932310.35
      1428344.35      6932005.19      1428521.02      6931381.63
#Sta/Elev= 30
    3974 1872.93  4060.8    1872  4101.1 1872.42    4208 1870.94  4243.9 1871.17
  4272.9 1872.46  4360.4 1872.66  4478.5 1870.88  4621.3 1869.89  4682.2 1869.87
  4699.5 1870.86  4709.9 1870.49    4741 1871.51  4755.6 1870.62  4772.2 1870.97
  4823.9 1869.86    4876 1866.58    4928 1864.56  4981.1 1865.07  5005.4 1864.01
  5005.9 1863.51  5024.8 1864.01  5031.9 1865.86    5063 1870.65  5104.6 1871.42
  5122.1  1872.8    5156 1871.42  5364.4 1873.41  5572.3 1873.38  5641.3 1874.38
#Mann= 4 ,-1 , 0
    3974     .05       0  4272.9     .07       0  5005.4     .07       0
  5024.8     .07       0
Bank Sta=5005.4,5024.8
XS Rating Curve= 0 ,0
Exp/Cntr=0.3,0.1

Type RM Length L Ch R = 1 ,38267   ,679,679,679
BEGIN DESCRIPTION:
Mapping XS 4ac84f38
END DESCRIPTION:
XS GIS Cut Line= 4
      1427630.38      6932463.13      1428750.85      6932258.36
      1428830.18       6932037.5      1428646.87      6931371.36
#Sta/Elev= 30
  3626.3 1872.68  3702.2 1872.83  3796.3 1871.17  3844.5 1872.22  3935.5 1872.32
  4190.1 1869.94  4237.4 1870.38  4667.9  1869.2  4749.2 1869.69  4848.5 1868.21
    4872 1867.41  4884.5 1866.05  4925.1 1865.22    4990 1861.98  4990.5 1861.48
  5009.4 1861.98  5030.6 1862.86  5051.3 1862.27  5076.7 1862.96  5103.2 1869.58
  5206.9 1870.46  5217.3 1871.88  5264.2 1871.02  5289.9 1871.89  5383.2 1871.74
  5565.4 1873.41  5632.2 1872.95  5663.3 1874.12    5684 1873.93  5690.9 1874.05
#Mann= 5 ,-1 , 0
  3626.3     .05       0  3935.5     .07       0    4990     .07       0
  5009.4     .07       0    5684    .035       0
Bank Sta=4990,5009.4
XS Rating Curve= 0 ,0
Exp/Cntr=0.3,0.1

Type RM Length L Ch R = 1 ,37588   ,43,43,43
BEGIN DESCRIPTION:
Mapping XS 0dc2c42b
END DESCRIPTION:
XS GIS Cut Line= 5
      1427640.82      6932497.85      1428359.55      6932369.38
      1429177.06      6932368.11      1429212.06      6932068.21
      1428756.31      6931573.39
#Sta/Elev= 30
  3108.6 1871.69  3497.7 1871.22  3974.2 1868.89  4514.2 1869.47  4554.2 1867.17
  4594.2 1869.01    4747  1868.9  4777.2 1868.01  4787.2 1865.36  4853.4 1858.51
  4858.5  1859.8  4898.4  1856.9  4898.9  1856.4  4917.8  1856.9  4936.8 1857.49
  4955.8 1862.53  4963.2 1859.38  4970.6 1861.42  4977.4 1858.83  4984.8 1861.24
  4991.6 1858.83    4999 1860.77  5005.8 1858.76    5020 1864.78  5026.7 1862.82
  5034.1 1864.78  5040.9 1863.54  5083.5  1866.3  5090.8 1868.28  5630.9 1872.68
#Mann= 4 ,-1 , 0
  3108.6     .05       0  3497.7     .07       0  4898.4     .07       0
  4917.8     .07       0
Bank Sta=4898.4,4917.8
XS Rating Curve= 0 ,0
Exp/Cntr=0.3,0.1

Type RM Length L Ch R = 1 ,37545   ,25,25,25
BEGIN DESCRIPTION:
Mapping XS 81355179
END DESCRIPTION:
XS GIS Cut Line= 6
      1427665.09      6932532.58      1428366.49       6932404.1
       1429216.3      6932419.95      1429272.82      6932133.31
       1429238.1      6932050.85      1428799.84      6931556.18
#Sta/Elev= 30
  3036.8  1870.3  3209.5 1871.83  3490.6 1870.61  4388.5 1868.83  4448.5 1868.17
  4448.8 1866.44  4449.3 1865.94  4468.2 1866.44  4468.5 1868.61  4548.5 1868.09
  4568.5 1870.24  4596.7 1867.33  4763.2 1866.75  4778.5 1868.91  4783.6 1866.91
  4820.3 1871.67  4896.9 1872.63  4926.1  1871.5  4931.5 1868.75  4949.8 1870.29
  4955.3 1868.06  4973.6 1870.52    4979 1869.11  4981.5 1870.65  5014.9 1871.44
  5093.3 1871.75  5100.2  1870.1  5121.1 1872.34  5149.5 1867.87  5643.5 1872.21
#Mann= 4 ,-1 , 0
  3036.8     .05       0  3490.6     .07       0  4448.8     .07       0
  4468.2     .07       0
Bank Sta=4448.8,4468.2
XS Rating Curve= 0 ,0
Exp/Cntr=0.3,0.1

Type RM Length L Ch R = 1 ,37520   ,877,877,877
BEGIN DESCRIPTION:
Mapping XS f1c384ca
END DESCRIPTION:
XS GIS Cut Line= 6
      1427692.87       6932567.3      1428380.38      6932427.25
      1429260.76      6932448.61       1429303.2      6932111.61
       1429259.8      6932050.85      1428899.82      6931496.47
#Sta/Elev= 30
  2988.4  1868.9  3164.7 1871.28  3486.6 1869.54  3513.5 1871.16  3609.6 1868.97
  4570.3 1866.81  4742.6 1868.31  4762.8 1864.07  4801.4 1868.96  4813.2 1866.52
  4853.5 1867.71  4886.7 1865.19  4893.8 1867.49    4927 1866.31  4933.1 1869.79
  4947.9 1865.55    4954 1870.45  4962.6 1868.48  4968.8 1870.41  4998.7 1866.67
  5004.6 1869.24  5019.8 1863.71  5025.7 1866.22  5034.9  1864.2  5040.9  1867.1
  5046.3 1862.59  5046.8 1862.09  5065.7 1862.59  5143.4 1869.11    5646 1872.19
#Mann= 4 ,-1 , 0
  2988.4     .05       0  3486.6     .07       0  5046.3     .07       0
  5065.7     .07       0
Bank Sta=5046.3,5065.7
XS Rating Curve= 0 ,0
Exp/Cntr=0.3,0.1

Type RM Length L Ch R = 1 ,36643   ,475,475,475
BEGIN DESCRIPTION:
Mapping XS 405ee8aa
END DESCRIPTION:
XS GIS Cut Line= 5
      1428802.46       6933804.8      1429350.87      6933297.04
      1429583.85      6932688.25      1429607.02      6932497.89
       1429894.5      6932024.89
#Sta/Elev= 30
  3403.8 1867.49  3474.3 1866.14  3643.9 1866.65  3778.2 1865.27  4150.6 1866.97
  4455.9 1866.78  4655.6 1864.23  4717.6 1864.69  4740.4 1862.96  4749.8 1860.21
  4759.7 1859.35  4823.9 1859.89  4833.5 1860.35  4863.7 1866.85  4883.9 1864.72
  4932.9 1863.94  4944.3 1860.07  4944.7 1857.29  4945.2 1856.79  4964.1 1857.29
  5052.8 1860.65  5110.9 1864.52  5205.3 1866.86  5270.2 1866.72  5343.5 1867.49
  5349.3 1866.28  5386.1 1866.52  5438.4 1868.34  5474.4 1867.64  5548.3  1868.8
#Mann= 5 ,-1 , 0
  3403.8     .05       0  4823.9     .07       0  4944.7     .07       0
  4964.1     .07       0  5270.2    .035       0
Bank Sta=4944.7,4964.1
XS Rating Curve= 0 ,0
Exp/Cntr=0.3,0.1

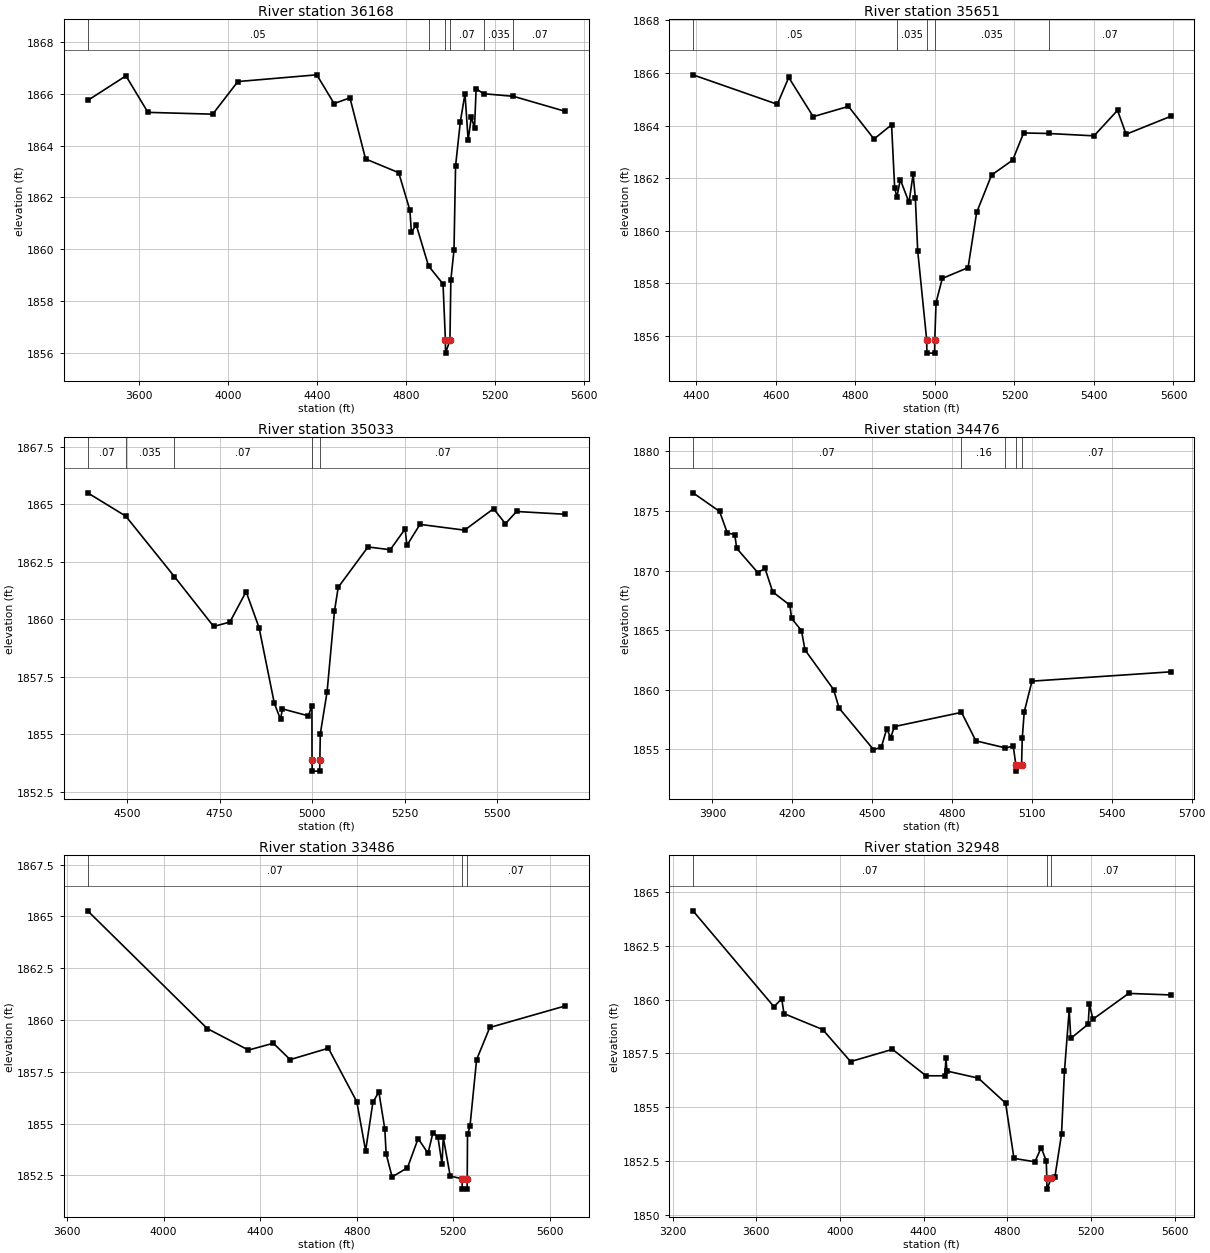
Type RM Length L Ch R = 1 ,36168   ,517,517,517
BEGIN DESCRIPTION:
Mapping XS aabee782
END DESCRIPTION:
XS GIS Cut Line= 3
      1428814.01      6933949.44      1429900.42      6932730.53
      1430288.42      6932397.22
#Sta/Elev= 30
  3371.1 1865.74    3543 1866.69  3641.6 1865.28  3932.6 1865.21  4045.4 1866.47
  4399.9 1866.73  4477.7 1865.62  4548.8 1865.84    4619 1863.48  4767.8 1862.95
    4818  1861.5  4824.7 1860.65  4846.4 1860.93  4901.6 1859.35  4966.8 1858.65
  4977.5 1856.48    4978 1855.98  4997.9 1856.48  5001.9 1858.81    5016 1859.96
  5023.1 1863.21  5044.5 1864.92  5065.4    1866  5079.6 1864.21  5093.9  1865.1
  5108.2 1864.67  5115.4 1866.19  5149.3    1866  5283.1  1865.9  5515.4 1865.32
#Mann= 6 ,-1 , 0
  3371.1     .05       0  4901.6     .07       0  4977.5     .07       0
  4997.9     .07       0  5149.3    .035       0  5283.1     .07       0
Bank Sta=4977.5,4997.9
XS Rating Curve= 0 ,0
Exp/Cntr=0.3,0.1

Type RM Length L Ch R = 1 ,35651   ,618,618,618
BEGIN DESCRIPTION:
Mapping XS b06a35a7
END DESCRIPTION:
XS GIS Cut Line= 3
      1429298.82      6933480.55      1429853.55      6933233.14
      1430369.18      6932938.86
#Sta/Elev= 30
  4391.5 1865.93  4603.6 1864.81  4632.3 1865.83  4693.9 1864.34  4782.6 1864.73
  4846.8 1863.49    4891 1864.03  4898.8 1861.61  4904.5 1861.29  4912.9 1861.95
  4934.8 1861.08  4945.2 1862.15  4950.7 1861.26  4956.7 1859.24  4979.3 1855.85
  4979.8 1855.35  4999.2 1855.35  4999.7 1855.85  5002.8 1857.27  5018.6 1858.19
  5083.4  1858.6    5105  1860.7  5142.5 1862.12  5195.7 1862.69  5223.1 1863.72
  5285.9  1863.7  5400.2 1863.61  5459.3 1864.58  5480.9 1863.67  5592.6 1864.35
#Mann= 5 ,-1 , 0
  4391.5     .05       0  4904.5    .035       0  4979.3    .035       0
  4999.7    .035       0  5285.9     .07       0
Bank Sta=4979.3,4999.7
XS Rating Curve= 0 ,0
Exp/Cntr=0.3,0.1

Type RM Length L Ch R = 1 ,35033   ,557,557,557
BEGIN DESCRIPTION:
Mapping XS 783cab27
END DESCRIPTION:
XS GIS Cut Line= 3
      1430228.56      6933980.49      1430358.76      6933384.18
      1430416.05      6932707.05
#Sta/Elev= 30
  4393.4 1865.49  4496.2 1864.48  4627.9 1861.85  4733.7 1859.69  4777.5 1859.88
  4821.4  1861.2  4856.5 1859.63  4897.5 1856.36  4914.3 1855.66  4919.5 1856.11
  4989.6 1855.81  4999.2 1856.25  4999.4 1853.91  4999.9 1853.41  5020.1 1853.41
  5020.6 1853.91  5021.8 1855.03  5040.1 1856.85  5060.1 1860.36  5070.2 1861.39
  5150.5 1863.14  5210.7 1863.02  5250.8 1863.92  5255.8 1863.21    5291 1864.12
  5411.4 1863.87  5489.8  1864.8  5521.8 1864.15  5551.9 1864.68  5683.3 1864.56
#Mann= 5 ,-1 , 0
  4393.4     .07       0  4496.2    .035       0  4627.9     .07       0
  4999.4     .07       0  5020.6     .07       0
Bank Sta=4999.4,5020.6
XS Rating Curve= 0 ,0
Exp/Cntr=0.3,0.1

Type RM Length L Ch R = 1 ,34476   ,990,990,990
BEGIN DESCRIPTION:
Mapping XS 7d4abced
END DESCRIPTION:
XS GIS Cut Line= 3
      1430119.76      6934442.79       1430822.3       6933519.6
      1430972.61      6932904.19
#Sta/Elev= 30
    3827 1876.52  3926.9 1874.96    3956 1873.15  3983.8 1873.02  3991.3 1871.86
  4070.3 1869.83  4097.4 1870.18  4126.5 1868.21  4190.9 1867.09  4197.4 1865.98
  4234.5 1864.96  4247.7 1863.34  4355.2 1860.01    4376 1858.45  4504.9 1854.98
    4534 1855.16  4554.8 1856.72  4569.3 1855.99  4583.9 1856.91  4835.5  1858.1
  4889.6 1855.71  5000.1 1855.12  5029.9 1855.26  5039.9 1853.67  5040.4 1853.17
  5061.1 1853.67  5063.8 1855.95  5071.1 1858.14  5100.3 1860.72  5620.6  1861.5
#Mann= 5 ,-1 , 0
    3827     .07       0  4835.5     .16       0  5000.1     .07       0
  5039.9     .07       0  5061.1     .07       0
Bank Sta=5039.9,5061.1
XS Rating Curve= 0 ,0
Exp/Cntr=0.3,0.1

Type RM Length L Ch R = 1 ,33486   ,538,538,538
BEGIN DESCRIPTION:
Mapping XS c06e41c3
END DESCRIPTION:
XS GIS Cut Line= 4
       1431148.4      6935056.91      1431273.66      6934206.49
      1431113.96      6933787.82      1430973.49      6933132.29
#Sta/Elev= 30
  3685.5 1865.27  4180.8 1859.59  4351.5 1858.55  4454.5 1858.88  4524.2 1858.09
  4682.6 1858.64  4800.3 1856.06  4836.9 1853.69    4867 1856.03  4891.7 1856.53
  4916.4 1854.74  4921.8 1853.55  4946.5 1852.43  5010.2 1852.87  5054.4 1854.28
  5095.3 1853.57  5115.7 1854.56  5136.2 1854.36  5153.4 1853.04  5158.5 1854.34
  5187.3 1852.47  5236.6 1852.34  5237.1 1851.84  5257.3 1851.84  5257.8 1852.34
  5258.9 1854.48  5269.1 1854.87  5296.6 1858.09  5351.1 1859.64  5663.6 1860.68
#Mann= 3 ,-1 , 0
  3685.5     .07       0  5236.6     .07       0  5257.8     .07       0
Bank Sta=5236.6,5257.8
XS Rating Curve= 0 ,0
Exp/Cntr=0.3,0.1

Type RM Length L Ch R = 1 ,32948   ,573,573,573
BEGIN DESCRIPTION:
Mapping XS dc3c3df0
END DESCRIPTION:
XS GIS Cut Line= 4
      1431170.09      6934981.02      1431343.13      6934259.18
      1431296.26      6933313.87      1431041.06      6932777.44
#Sta/Elev= 30
  3297.9 1864.13  3685.1 1859.67    3722 1860.04  3732.9 1859.35    3918 1858.61
  4051.4 1857.12  4251.6 1857.69  4411.8 1856.46  4501.9 1856.46  4507.1 1857.27
  4512.1 1856.68  4662.1 1856.35  4792.3 1855.19  4832.3 1852.62  4932.5 1852.46
  4962.5 1853.12  4986.7  1852.5  4989.3 1851.69  4989.8 1851.19  5010.6 1851.69
  5028.2 1851.77  5059.6 1853.74  5073.6 1856.66  5096.3 1859.53  5103.9  1858.2
  5187.2 1858.86  5192.7  1859.8  5209.9 1859.09  5380.7 1860.29  5580.7 1860.22
#Mann= 3 ,-1 , 0
  3297.9     .07       0  4989.3     .07       0  5010.6     .07       0
Bank Sta=4989.3,5010.6
XS Rating Curve= 0 ,0
Exp/Cntr=0.3,0.1