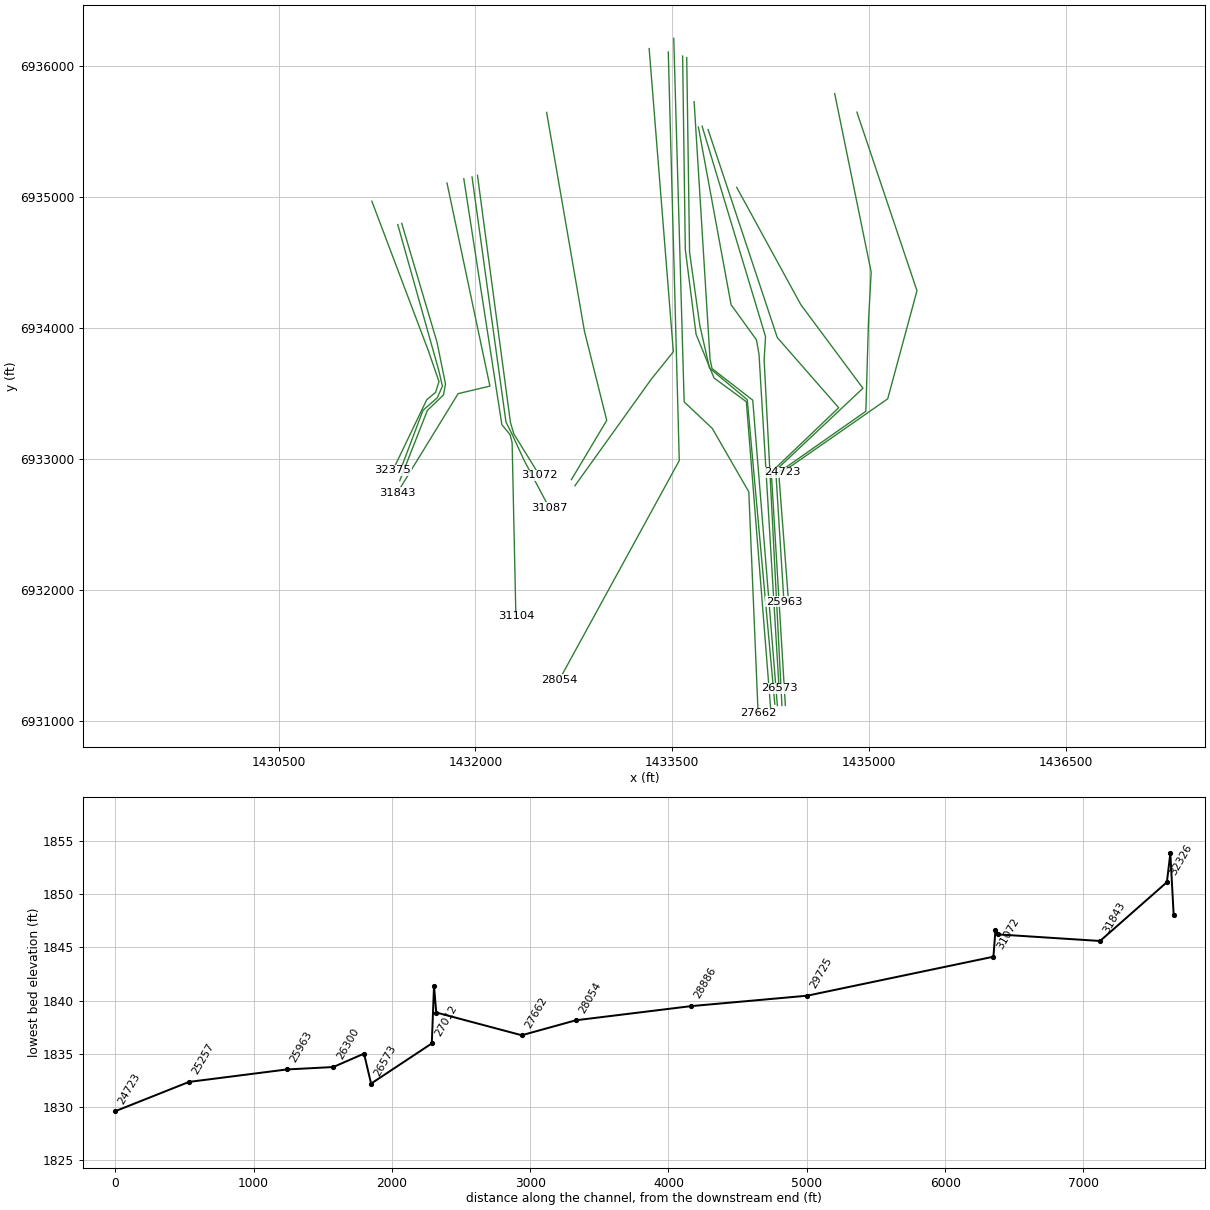
HEC-RAS study China Creek.prj: China Creek Base Level Engineering

--- China Creek.g01 (geometry) --- (continued)

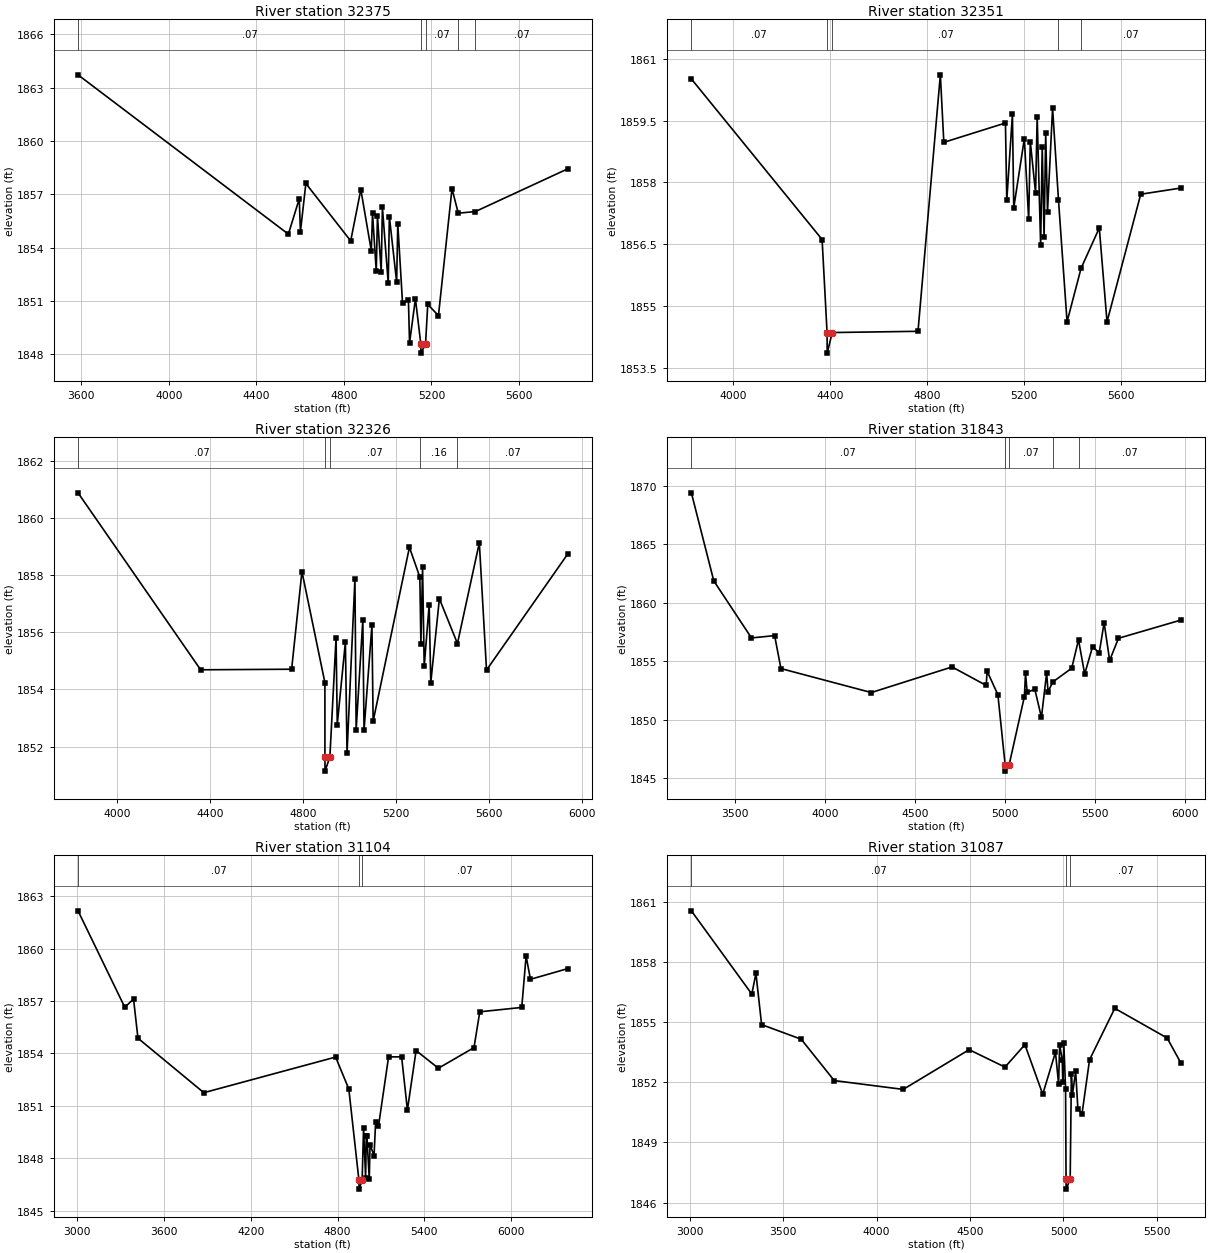
Type RM Length L Ch R = 1 ,32375   ,24,24,24
BEGIN DESCRIPTION:
Mapping XS 6defc2d7
END DESCRIPTION:
XS GIS Cut Line= 6
      1431211.34      6934965.78      1431642.61      6933824.28
      1431723.34      6933589.91       1431697.3      6933509.18
      1431629.59      6933451.89      1431371.77      6932915.41
#Sta/Elev= 30
  3584.6 1863.72  4546.2 1854.76  4595.9 1856.75  4601.3  1854.9  4626.1 1857.61
  4831.1 1854.38  4877.4 1857.27  4925.3 1853.82  4930.8 1855.93  4947.9 1852.67
  4953.4 1855.78  4970.5 1852.66    4976 1856.27  5002.6    1852  5007.8 1855.75
  5041.1 1852.06  5046.3 1855.33  5068.1 1850.87  5094.9 1851.07  5100.1 1848.64
  5126.9 1851.13  5151.8 1848.57  5152.3 1848.07  5173.1 1848.57  5183.3 1850.81
  5232.2 1850.18  5294.1 1857.32  5322.7 1855.94  5400.8 1856.03  5822.5 1858.43
#Mann= 5 ,-1 , 0
  3584.6     .07       0  5151.8     .07       0  5173.1     .07       0
  5322.7     .16       0  5400.8     .07       0
Bank Sta=5151.8,5173.1
XS Rating Curve= 0 ,0
Exp/Cntr=0.3,0.1

Type RM Length L Ch R = 1 ,32351   ,25,25,25
BEGIN DESCRIPTION:
Mapping XS a8913a53
END DESCRIPTION:
XS GIS Cut Line= 6
      1431408.82      6934787.81      1431720.74      6933678.45
      1431749.38      6933556.05      1431710.32      6933467.51
      1431600.94      6933371.16      1431423.97       6932902.7
#Sta/Elev= 30
  3827.5 1860.51  4367.3 1856.61  4387.8 1854.35  4388.3 1853.85  4409.1 1854.35
  4763.2 1854.38  4855.5 1860.61  4869.9 1858.97  5124.3 1859.44  5129.8 1857.56
  5153.1 1859.65  5158.6 1857.38  5202.4 1859.06  5220.2  1857.1  5226.9 1858.99
  5248.7 1857.74  5255.3 1859.59  5269.6 1856.47  5276.2 1858.86  5283.8 1856.66
  5290.5 1859.19    5298 1857.29  5318.9  1859.8  5343.3 1857.57  5378.7 1854.61
  5436.5 1855.91  5511.8 1856.89  5543.7 1854.61  5682.9 1857.71  5848.9 1857.86
#Mann= 5 ,-1 , 0
  3827.5     .07       0  4387.8     .07       0  4409.1     .07       0
  5343.3     .16       0  5436.5     .07       0
Bank Sta=4387.8,4409.1
XS Rating Curve= 0 ,0
Exp/Cntr=0.3,0.1

Type RM Length L Ch R = 1 ,32326   ,483,483,483
BEGIN DESCRIPTION:
Mapping XS d4628a11
END DESCRIPTION:
XS GIS Cut Line= 6
       1431439.2      6934796.51      1431707.71      6933891.99
      1431772.82      6933571.68      1431757.19      6933488.35
       1431634.8      6933371.16      1431423.85      6932834.66
#Sta/Elev= 30
  3832.5 1860.89  4360.1 1854.69  4751.5 1854.71  4795.9 1858.13  4894.7 1854.24
  4894.8 1851.64  4895.3 1851.14  4916.1 1851.64  4942.7 1855.81  4947.8 1852.77
  4982.8 1855.66  4989.9 1851.78  5023.9 1857.86  5029.1 1852.59  5057.9 1856.44
    5063 1852.57    5097 1856.25  5102.2 1852.89  5258.3 1858.98  5303.1 1857.94
  5307.7 1855.59  5314.9 1858.28  5321.9 1854.81  5343.2 1856.96  5350.2 1854.24
  5387.2 1857.18  5464.9 1855.61  5559.1 1859.14    5590 1854.68  5938.8 1858.74
#Mann= 5 ,-1 , 0
  3832.5     .07       0  4894.8     .07       0  4916.1     .07       0
  5303.1     .16       0  5464.9     .07       0
Bank Sta=4894.8,4916.1
XS Rating Curve= 0 ,0
Exp/Cntr=0.3,0.1

Type RM Length L Ch R = 1 ,31843   ,739,739,739
BEGIN DESCRIPTION:
Mapping XS efadf03f
END DESCRIPTION:
XS GIS Cut Line= 4
      1431784.24       6935104.7      1432111.36      6933556.05
      1431869.17      6933498.76      1431404.96      6932742.22
#Sta/Elev= 30
  3256.7 1869.41  3381.2 1861.88  3590.6    1857  3719.2  1857.2  3754.1 1854.38
  4256.2 1852.33  4704.7 1854.52  4894.3 1852.94  4899.4 1854.16  4959.1 1852.15
  4999.8 1846.11  5000.3 1845.61  5021.1 1846.11  5106.4 1851.98  5112.7 1853.97
  5121.8 1852.35  5164.4 1852.61  5201.1  1850.2  5230.1 1854.01  5237.9  1852.4
  5264.6 1853.24  5369.3 1854.41  5407.1 1856.84  5441.3 1853.91  5485.3 1856.26
  5522.1 1855.72  5549.2  1858.3  5580.1 1855.08    5629 1856.97    5976 1858.53
#Mann= 5 ,-1 , 0
  3256.7     .07       0  4999.8     .07       0  5021.1     .07       0
  5264.6     .16       0  5407.1     .07       0
Bank Sta=4999.8,5021.1
XS Rating Curve= 0 ,0
Exp/Cntr=0.3,0.1

Type RM Length L Ch R = 1 ,31104   ,17,17,17
BEGIN DESCRIPTION:
Mapping XS 964e82a0
END DESCRIPTION:
XS GIS Cut Line= 5
      1431912.28      6935137.28      1432202.51      6933261.78
      1432265.01      6933186.26      1432280.63      6933126.37
      1432309.38      6931801.32
#Sta/Elev= 30
  3006.3 1862.16  3329.4 1856.64  3390.1 1857.11  3420.4 1854.87  3875.8 1851.75
  4786.5 1853.79  4877.6 1851.96  4947.6 1846.73  4948.1 1846.23  4969.7 1846.73
  4979.5 1849.74  4993.8 1846.86  4998.2 1849.29  5002.1 1849.29  5018.9 1846.83
  5024.1 1848.77    5052 1848.15  5062.8 1850.06  5082.4 1849.82  5152.4  1853.8
  5242.5  1853.8  5282.5 1850.76  5342.5 1854.16  5496.7 1853.15  5742.6 1854.33
  5782.6 1856.38  6072.6 1856.63  6102.7 1859.57  6132.7 1858.24  6389.4 1858.85
#Mann= 3 ,-1 , 0
  3006.3     .07       0  4947.6     .07       0  4969.7     .07       0
Bank Sta=4947.6,4969.7
XS Rating Curve= 0 ,0
Exp/Cntr=0.3,0.1

Type RM Length L Ch R = 1 ,31087   ,15,15,15
BEGIN DESCRIPTION:
Mapping XS d87a57dd
END DESCRIPTION:
XS GIS Cut Line= 5
      1431975.22      6935150.27      1432233.76      6933282.62
      1432278.03      6933194.07      1432371.78      6932990.95
      1432564.17      6932627.39
#Sta/Elev= 30
  3008.9 1860.54  3332.3 1856.39  3354.4 1857.42  3384.7 1854.87  3596.7 1854.14
  3773.2 1852.08  4142.3 1851.64  4495.2 1853.62    4687 1852.75  4793.5 1853.87
  4888.9  1851.4    4957 1853.49  4973.8 1851.91  4979.4 1853.87  4993.4  1853.1
  4996.3 1851.99  5001.8 1853.94  5011.1 1851.68  5013.7 1847.17  5014.2 1846.67
  5035.8 1847.17  5042.2 1852.39  5047.7 1851.38  5065.1 1852.54  5077.1 1850.66
  5099.2 1850.43  5139.5 1853.12  5274.4 1855.68  5554.8  1854.2  5628.4 1852.95
#Mann= 3 ,-1 , 0
  3008.9     .07       0  5013.7     .07       0  5035.8     .07       0
Bank Sta=5013.7,5035.8
XS Rating Curve= 0 ,0
Exp/Cntr=0.3,0.1

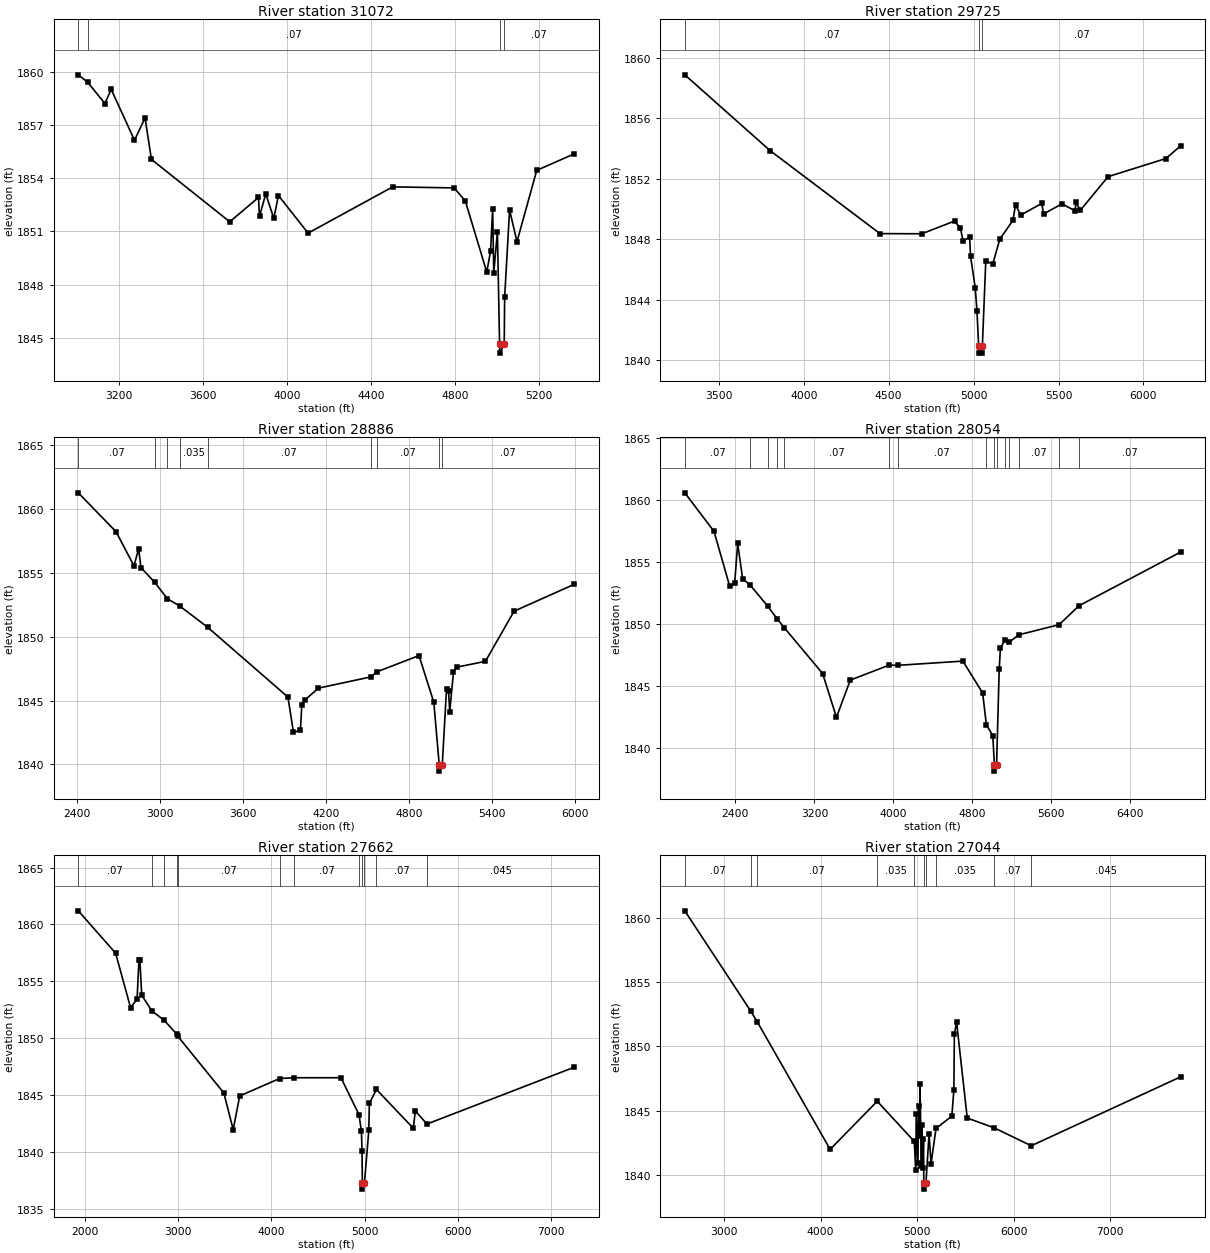
Type RM Length L Ch R = 1 ,31072   ,1347,1347,1347
BEGIN DESCRIPTION:
Mapping XS 37859a76
END DESCRIPTION:
XS GIS Cut Line= 4
      1432016.46      6935163.26      1432267.61      6933280.01
      1432293.65      6933191.47      1432488.95       6932876.4
#Sta/Elev= 30
  3005.4 1859.83    3051  1859.4  3131.8 1858.21    3162 1859.01    3273 1856.14
  3323.4  1857.4  3353.7 1855.06    3727 1851.54  3863.8 1852.91  3868.8 1851.84
  3898.5 1853.12  3936.9 1851.73    3959 1853.02  4100.3  1850.9  4503.8 1853.51
  4796.4 1853.45  4849.8 1852.71  4951.8  1848.7    4970 1849.89  4979.9 1852.27
  4985.1 1848.65  5002.6 1850.98  5012.9 1844.63  5013.4 1844.13    5035 1844.63
    5037 1847.28  5060.5 1852.21  5095.8 1850.42  5189.9 1854.44  5368.3 1855.37
#Mann= 4 ,-1 , 0
  3005.4    .035       0    3051     .07       0  5012.9     .07       0
    5035     .07       0
Bank Sta=5012.9,5035
XS Rating Curve= 0 ,0
Exp/Cntr=0.3,0.1

Type RM Length L Ch R = 1 ,29725   ,839,839,839
BEGIN DESCRIPTION:
Mapping XS ee1bb391
END DESCRIPTION:
XS GIS Cut Line= 4
      1432543.79      6935642.89      1432832.71      6933971.85
      1433001.99      6933294.77      1432732.87      6932843.35
#Sta/Elev= 30
  3299.6 1858.88  3801.2 1853.87  4448.7 1848.37  4694.9 1848.36  4887.7  1849.2
    4922 1848.74  4938.4 1847.89  4976.7 1848.12  4981.8 1846.89  5009.7 1844.77
    5020 1843.23  5029.6 1840.96  5030.1 1840.46  5051.2 1840.46  5051.7 1840.96
  5071.7 1846.55  5112.9 1846.36  5154.2    1848  5231.5 1849.25  5246.8 1850.27
  5277.9  1849.6  5401.6 1850.37  5411.7 1849.67  5520.1 1850.34  5597.3 1849.88
  5602.6 1850.44  5628.2 1849.91  5791.7 1852.14  6132.3 1853.34  6218.9 1854.18
#Mann= 3 ,-1 , 0
  3299.6     .07       0  5029.6     .07       0  5051.7     .07       0
Bank Sta=5029.6,5051.7
XS Rating Curve= 0 ,0
Exp/Cntr=0.3,0.1

Type RM Length L Ch R = 1 ,28886   ,832,832,832
BEGIN DESCRIPTION:
Mapping XS 952edc3f
END DESCRIPTION:
XS GIS Cut Line= 4
      1433325.44       6936129.4       1433509.8       6933817.8
      1433340.53      6933607.27      1432759.44      6932796.35
#Sta/Elev= 30
    2407 1861.28  2679.3 1858.24  2809.7 1855.56  2843.3  1856.9  2859.8 1855.43
  2958.6 1854.28  3050.9 1852.99    3142  1852.4  3342.4 1850.75  3923.2 1845.28
  3963.3 1842.52  4013.5 1842.68  4023.5 1844.63  4043.6 1845.03  4143.9 1845.98
  4522.4 1846.86    4567 1847.26  4871.2 1848.53  4978.4 1844.88  5017.6 1839.98
  5018.1 1839.48  5039.7 1839.98  5070.4 1845.92  5085.1 1845.74  5093.6 1844.15
  5120.8 1847.21  5142.8 1847.62  5351.7 1848.08  5559.2 1852.01  5993.7 1854.11
#Mann= 9 ,-1 , 0
    2407     .07       0  2958.6    .035       0  3050.9     .07       0
    3142    .035       0  3342.4     .07       0  4522.4    .035       0
    4567     .07       0  5017.6     .07       0  5039.7     .07       0
Bank Sta=5017.6,5039.7
XS Rating Curve= 0 ,0
Exp/Cntr=0.3,0.1

Type RM Length L Ch R = 1 ,28054   ,392,392,392
BEGIN DESCRIPTION:
China Creek 15.0
END DESCRIPTION:
XS GIS Cut Line= 3
      1433471.27      6936103.36        1433555.        6932988.
      1432640.54      6931316.93
#Sta/Elev= 30
  1887.3 1860.56  2182.8 1857.46  2342.8 1853.02  2392.8 1853.33  2422.9 1856.48
  2472.9 1853.64  2548.8 1853.14  2725.8 1851.44  2824.5  1850.4  2893.4 1849.71
  3283.2 1846.01  3423.2 1842.48  3563.3 1845.48  3958.5 1846.69  4046.4 1846.67
  4703.7 1847.01  4903.8 1844.44  4941.4 1841.88  5006.6 1841.01  5022.6 1838.65
  5023.1 1838.15  5044.8 1838.65  5071.6  1846.4  5083.6 1848.03  5127.9 1848.69
  5172.7 1848.54  5270.3 1849.13  5677.4 1849.94  5880.3 1851.47  6908.7 1855.79
#Mann= 15 ,-1 , 0
  1887.3     .07       0  2548.8    .035       0  2725.8     .07       0
  2824.5    .035       0  2893.4     .07       0  3958.5    .035       0
  4046.4     .07       0  4941.4    .035       0  5022.6    .035       0
  5044.8    .035       0  5127.9     .07       0  5172.7     .16       0
  5270.3     .07       0  5677.4    .035       0  5880.3     .07       0
Bank Sta=5022.6,5044.8
XS Rating Curve= 0 ,0
Exp/Cntr=0.3,0.1

Type RM Length L Ch R = 1 ,27662   ,618,618,618
BEGIN DESCRIPTION:
Mapping XS 95a05c16
END DESCRIPTION:
XS GIS Cut Line= 5
      1433512.93      6936207.56      1433592.26      6933435.83
      1433806.53      6933233.73      1434085.14      6932750.08
      1434156.08      6931061.03
#Sta/Elev= 30
  1930.3  1861.2    2330 1857.48  2490.1  1852.7  2560.1 1853.42  2580.1 1856.87
  2590.1 1856.87  2610.1 1853.79  2719.6 1852.39  2846.9 1851.61  2983.4 1850.38
  2993.6 1850.21  3490.5 1845.19  3590.5 1841.97  3660.6 1844.93  4088.2 1846.46
  4242.2 1846.53  4746.2 1846.53  4939.7 1843.28  4965.4 1841.83  4972.3 1840.05
  4975.4 1837.24  4975.9 1836.74  4997.6 1837.24  5044.7 1841.92  5050.5 1844.28
  5126.7  1845.5  5521.7 1842.09  5543.3 1843.62  5668.1 1842.46  7246.4 1847.45
#Mann= 12 ,-1 , 0
  1930.3     .07       0  2719.6    .035       0  2846.9     .07       0
  2983.4    .035       0  2993.6     .07       0  4088.2    .035       0
  4242.2     .07       0  4939.7    .035       0  4975.4    .035       0
  4997.6    .035       0  5126.7     .07       0  5668.1    .045       0
Bank Sta=4975.4,4997.6
XS Rating Curve= 0 ,0
Exp/Cntr=0.3,0.1

Type RM Length L Ch R = 1 ,27044   ,16,16,16
BEGIN DESCRIPTION:
Mapping XS a1e1d635
END DESCRIPTION:
XS GIS Cut Line= 6
      1433580.64      6936072.13      1433601.04      6934598.17
      1433683.41      6933950.15      1433820.13      6933618.12
      1434066.47      6933436.85      1434250.99      6931106.24
#Sta/Elev= 30
  2595.2 1860.57  3276.5 1852.77  3346.1 1851.91  4099.7 1841.98  4587.1 1845.73
  4970.3  1842.6  4985.4 1840.35  4990.7 1844.73  5008.2 1840.94  5014.2 1845.38
  5023.3 1843.02  5029.3 1847.11  5044.3 1840.65  5050.3 1843.91  5059.4 1840.51
  5065.4 1842.76  5069.4 1839.38  5069.9 1838.88  5091.6 1839.38  5123.3 1843.16
  5144.1 1840.87  5195.4 1843.61  5359.3 1844.57  5380.2 1846.62  5385.4 1850.98
  5408.3  1851.9  5518.7 1844.42  5796.6 1843.66    6181 1842.26  7727.3 1847.63
#Mann= 10 ,-1 , 0
  2595.2     .07       0  3276.5    .035       0  3346.1     .07       0
  4587.1    .035       0  4970.3     .07       0  5069.4     .07       0
  5091.6     .07       0  5195.4    .035       0  5796.6     .07       0
    6181    .045       0
Bank Sta=5069.4,5091.6
XS Rating Curve= 0 ,0
Exp/Cntr=0.3,0.1

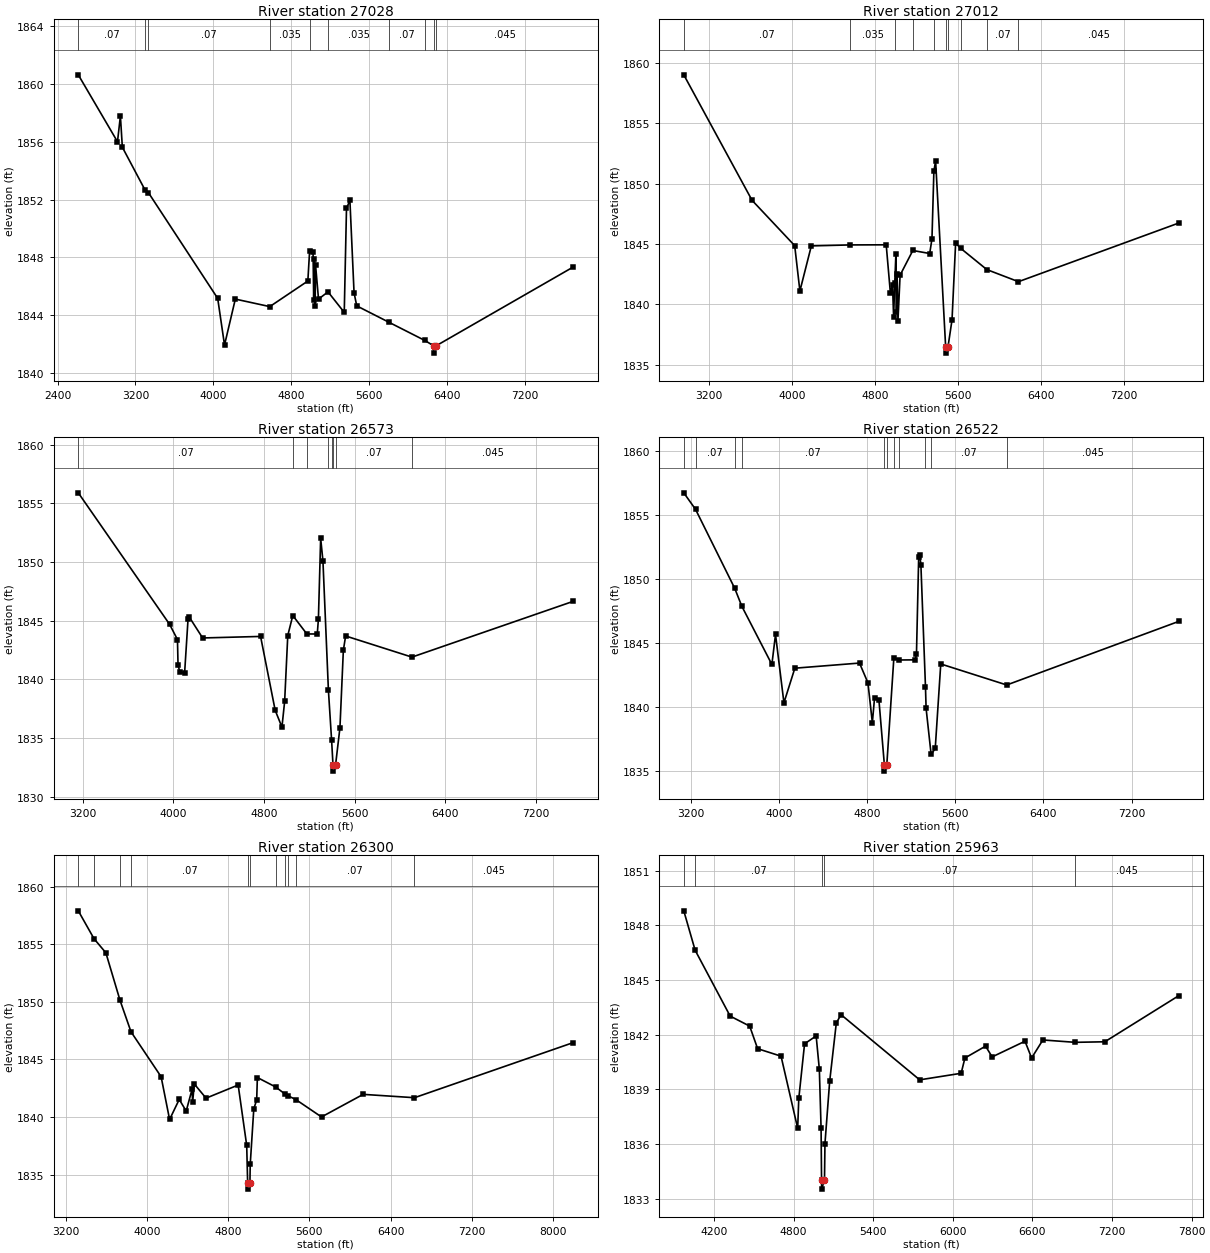
Type RM Length L Ch R = 1 ,27028   ,16,16,16
BEGIN DESCRIPTION:
Mapping XS fca618b0
END DESCRIPTION:
XS GIS Cut Line= 6
      1433611.89      6936060.89      1433633.59      6934576.47
      1433711.62       6934019.6      1433785.41      6933694.07
      1434073.27      6933452.39      1434283.41      6931131.58
#Sta/Elev= 30
  2611.9 1860.64  3014.8 1856.01  3044.8 1857.79  3064.8 1855.63  3298.1 1852.67
  3333.4 1852.48  4044.9 1845.17  4115.1 1841.94  4226.2 1845.12  4580.5  1844.6
  4971.7 1846.37  4990.1 1848.48  5025.3 1848.35  5031.9 1845.05  5039.6 1847.88
  5046.2 1844.65  5051.3 1847.45  5081.4 1845.12    5179 1845.62  5345.9  1844.2
    5369 1851.39    5404 1851.96  5446.7 1845.56  5474.3 1844.65  5810.1  1843.5
  6173.2 1842.26  6266.5 1841.88    6267 1841.38  6288.7 1841.88  7699.8 1847.34
#Mann= 10 ,-1 , 0
  2611.9     .07       0  3298.1    .035       0  3333.4     .07       0
  4580.5    .035       0  4990.1     .07       0    5179    .035       0
  5810.1     .07       0  6173.2    .045       0  6266.5     .07       0
  6288.7    .045       0
Bank Sta=6266.5,6288.7
XS Rating Curve= 0 ,0
Exp/Cntr=0.3,0.1

Type RM Length L Ch R = 1 ,27012   ,439,439,439
BEGIN DESCRIPTION:
Mapping XS 1de49790
END DESCRIPTION:
XS GIS Cut Line= 5
      1433668.32      6935724.42      1433789.75      6933761.35
      1433804.94      6933689.73      1434115.07      6933449.16
      1434302.93      6931121.06
#Sta/Elev= 30
  2957.7 1858.99  3615.4 1848.61  4026.2 1844.86  4076.3 1841.11  4186.5 1844.84
  4563.4 1844.92  4907.8 1844.93  4948.4 1840.92  4968.8 1841.62  4979.1 1838.98
  4990.3 1841.78  5000.9 1844.13  5006.4 1839.35  5012.8 1842.51  5020.9 1838.63
  5041.7 1842.42  5164.3 1844.46  5326.9 1844.21  5348.6 1845.42  5367.1 1851.02
  5383.9 1851.86  5480.6 1836.47  5481.1 1835.97  5502.8 1836.47  5541.9 1838.72
  5576.5 1845.07  5625.3 1844.64  5877.3 1842.88  6181.8 1841.88  7725.9 1846.73
#Mann= 10 ,-1 , 0
  2957.7     .07       0  4563.4    .035       0  4990.3     .07       0
  5164.3    .035       0  5367.1     .07       0  5480.6     .07       0
  5502.8     .07       0  5625.3    .035       0  5877.3     .07       0
  6181.8    .045       0
Bank Sta=5480.6,5502.8
XS Rating Curve= 0 ,0
Exp/Cntr=0.3,0.1

Type RM Length L Ch R = 1 ,26573   ,51,51,51
BEGIN DESCRIPTION:
Mapping XS 7892ad4b
END DESCRIPTION:
XS GIS Cut Line= 5
      1433700.88      6935531.29      1433950.17      6934176.59
      1434143.48      6933908.92      1434163.01      6933798.24
      1434315.99      6931251.24
#Sta/Elev= 30
    3160 1855.89  3966.6 1844.69    4036 1843.39    4041 1841.21  4058.1 1840.61
  4099.2 1840.56  4129.3 1845.12  4139.5 1845.32  4258.3 1843.53  4770.1 1843.66
    4899 1837.37  4958.8 1835.94  4982.6 1838.12  5010.3 1843.74  5054.6 1845.44
  5178.8 1843.87  5270.8 1843.87  5280.8 1845.13  5300.8 1852.02  5320.9 1850.09
  5369.2 1839.08  5397.3 1834.84  5409.9 1832.69  5410.4 1832.19  5432.1 1832.69
  5471.1 1835.89  5501.2 1842.48  5521.2  1843.7  6107.1  1841.9  7531.6 1846.65
#Mann= 8 ,-1 , 0
    3160     .07       0  5054.6    .035       0  5178.8     .07       0
  5369.2    .035       0  5397.3     .07       0  5409.9     .07       0
  5432.1     .07       0  6107.1    .045       0
Bank Sta=5409.9,5432.1
XS Rating Curve= 0 ,0
Exp/Cntr=0.3,0.1

Type RM Length L Ch R = 1 ,26522   ,222,222,222
BEGIN DESCRIPTION:
Mapping XS a47fb06e
END DESCRIPTION:
XS GIS Cut Line= 4
      1433729.08      6935537.85      1434212.92      6933932.79
      1434202.07      6933757.01      1434337.71      6931121.12
#Sta/Elev= 30
  3135.9 1856.72  3242.7 1855.43  3598.2 1849.27  3662.8 1847.87  3935.4 1843.33
  3968.4 1845.67  4044.8 1840.34  4143.8 1843.04  4730.7 1843.44  4807.1  1841.9
  4847.2 1838.79  4867.2 1840.72  4907.3 1840.52  4956.3 1835.51  4956.8 1835.01
  4978.5 1835.51  5042.5 1843.85  5089.2 1843.68  5237.8 1843.69  5247.8 1844.18
  5267.8 1851.72  5277.8 1851.85  5287.8 1851.11  5329.4 1841.59  5335.1  1839.9
  5380.7 1836.31    5418 1836.78  5468.1 1843.37  6066.9 1841.73  7627.8 1846.69
#Mann= 11 ,-1 , 0
  3135.9    .035       0  3242.7     .07       0  3598.2    .035       0
  3662.8     .07       0  4956.3     .07       0  4978.5     .07       0
  5042.5    .035       0  5089.2     .07       0  5329.4    .035       0
  5380.7     .07       0  6066.9    .045       0
Bank Sta=4956.3,4978.5
XS Rating Curve= 0 ,0
Exp/Cntr=0.3,0.1

Type RM Length L Ch R = 1 ,26300   ,337,337,337
BEGIN DESCRIPTION:
Mapping XS ab29fb0d
END DESCRIPTION:
XS GIS Cut Line= 5
      1433774.64      6935511.84      1434302.22      6933926.71
      1434770.48      6933391.44      1434256.42      6932899.88
       1434363.8      6931122.18
#Sta/Elev= 30
  3323.8 1857.89  3478.8 1855.47  3595.3 1854.25  3734.3 1850.14  3842.7  1847.4
  4139.4  1843.5  4222.9 1839.79  4317.8 1841.53  4386.4 1840.52  4444.4 1842.41
  4449.7 1841.28  4466.1 1842.87    4582 1841.64  4898.2 1842.78  4982.3 1837.54
  4991.7 1834.25  4992.2 1833.75  5013.9 1834.25    5017  1835.9  5052.1 1840.71
  5080.6 1841.49  5087.3 1843.43  5267.6 1842.61  5357.5 1842.01  5390.9 1841.84
  5467.7 1841.51    5719 1840.01  6129.1 1841.97  6634.2 1841.68  8197.8 1846.46
#Mann= 11 ,-1 , 0
  3323.8    .035       0  3478.8     .07       0  3734.3    .035       0
  3842.7     .07       0  4991.7     .07       0  5013.9     .07       0
  5267.6    .035       0  5357.5     .07       0  5390.9    .035       0
  5467.7     .07       0  6634.2    .045       0
Bank Sta=4991.7,5013.9
XS Rating Curve= 0 ,0
Exp/Cntr=0.3,0.1

Type RM Length L Ch R = 1 ,25963   ,706,706,706
BEGIN DESCRIPTION:
Mapping XS 8ec94002
END DESCRIPTION:
XS GIS Cut Line= 5
      1433993.14      6935071.11      1434481.91      6934176.71
      1434955.38      6933539.87      1434290.46      6932913.64
      1434352.94      6931912.17
#Sta/Elev= 30
  3973.1  1848.8  4058.4 1846.64  4322.6 1843.02  4469.7 1842.47  4529.5 1841.23
    4706 1840.82  4831.3 1836.86  4839.7  1838.5  4883.3  1841.5  4970.6 1841.93
  4994.6  1840.1  5007.7 1836.86  5011.2 1834.02  5011.7 1833.52  5033.4 1834.02
  5036.9 1836.02  5072.3 1839.43  5122.4 1842.64  5157.8  1843.1  5750.8 1839.52
  6063.2 1839.88  6091.6 1840.72  6247.3 1841.37  6296.7 1840.78  6544.3 1841.64
  6594.1 1840.72    6679 1841.71  6921.7 1841.58  7145.8 1841.61  7702.7 1844.14
#Mann= 5 ,-1 , 0
  3973.1    .035       0  4058.4     .07       0  5011.2     .07       0
  5033.4     .07       0  6921.7    .045       0
Bank Sta=5011.2,5033.4
XS Rating Curve= 0 ,0
Exp/Cntr=0.3,0.1

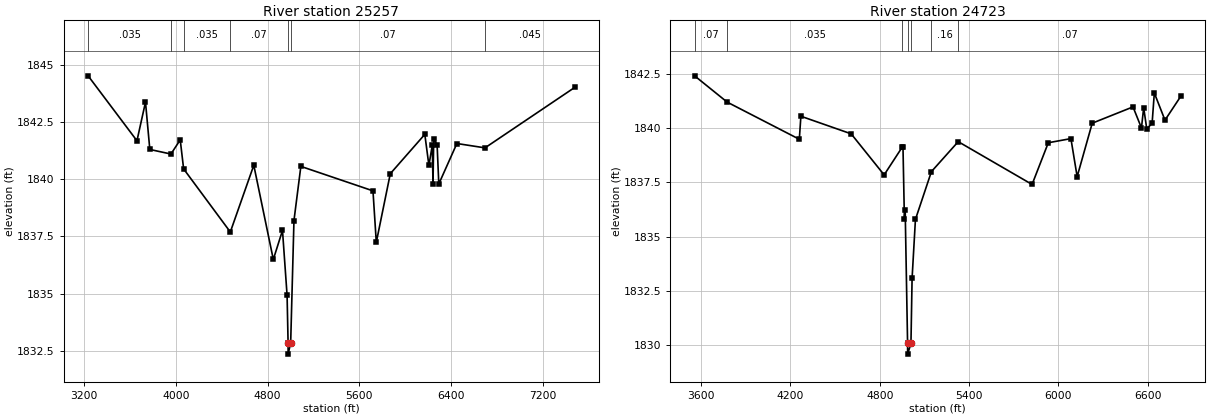
Type RM Length L Ch R = 1 ,25257   ,534,534,534
BEGIN DESCRIPTION:
Mapping XS 978b6191
END DESCRIPTION:
XS GIS Cut Line= 6
      1434740.15      6935785.45      1435018.13      6934425.42
      1434997.54       6934046.5      1434977.51      6933364.09
      1434312.96      6932897.95      1434387.72      6931917.86
#Sta/Elev= 30
  3233.3 1844.52  3659.4 1841.68  3733.9 1843.37  3771.7  1841.3    3956  1841.1
    4037 1841.72  4066.7 1840.45  4474.1 1837.69  4678.9 1840.61  4849.2 1836.49
  4929.3 1837.76  4969.4 1834.92  4978.1 1832.85  4978.6 1832.35  5000.7 1832.85
  5029.4 1838.19  5089.5 1840.56  5718.8 1839.49  5747.8 1837.24  5869.9 1840.24
  6171.1 1841.96  6206.9  1840.6  6236.4 1841.49  6242.6 1839.79  6248.7 1841.75
  6278.4 1841.51  6293.2 1839.79  6450.9 1841.56  6696.2 1841.37  7478.3 1844.01
#Mann= 7 ,-1 , 0
  3233.3    .035       0    3956     .07       0  4066.7    .035       0
  4474.1     .07       0  4978.1     .07       0  5000.7     .07       0
  6696.2    .045       0
Bank Sta=4978.1,5000.7
XS Rating Curve= 0 ,0
Exp/Cntr=0.3,0.1

Type RM Length L Ch R = 1 ,24723   ,1016,1016,1016
BEGIN DESCRIPTION:
Mapping XS 923fd5a8
END DESCRIPTION:
XS GIS Cut Line= 4
      1434909.43      6935644.79      1435367.33      6934283.48
      1435144.18      6933459.14      1434342.08      6932900.54
#Sta/Elev= 30
  3556.5  1842.4  3775.4 1841.19    4260 1839.48  4270.5 1840.54  4608.2 1839.73
  4829.7 1837.84  4952.3 1839.13  4956.3 1839.11  4965.7 1835.83    4971 1836.23
  4987.1 1830.09  4987.6 1829.59  5009.8 1830.09  5017.4 1833.08  5039.9 1835.79
  5147.1 1837.99  5327.3 1839.37  5823.3  1837.4  5932.3 1839.32  6084.2 1839.51
  6126.1 1837.76  6227.3 1840.22  6501.3 1840.97    6558    1840  6572.9 1840.93
  6593.8 1839.95  6629.6 1840.22  6644.4 1841.61    6716 1840.36  6824.2 1841.48
#Mann= 7 ,-1 , 0
  3556.5     .07       0  3775.4    .035       0  4952.3     .07       0
  4987.1     .07       0  5009.8     .07       0  5147.1     .16       0
  5327.3     .07       0
Bank Sta=4987.1,5009.8
XS Rating Curve= 0 ,0
Exp/Cntr=0.3,0.1