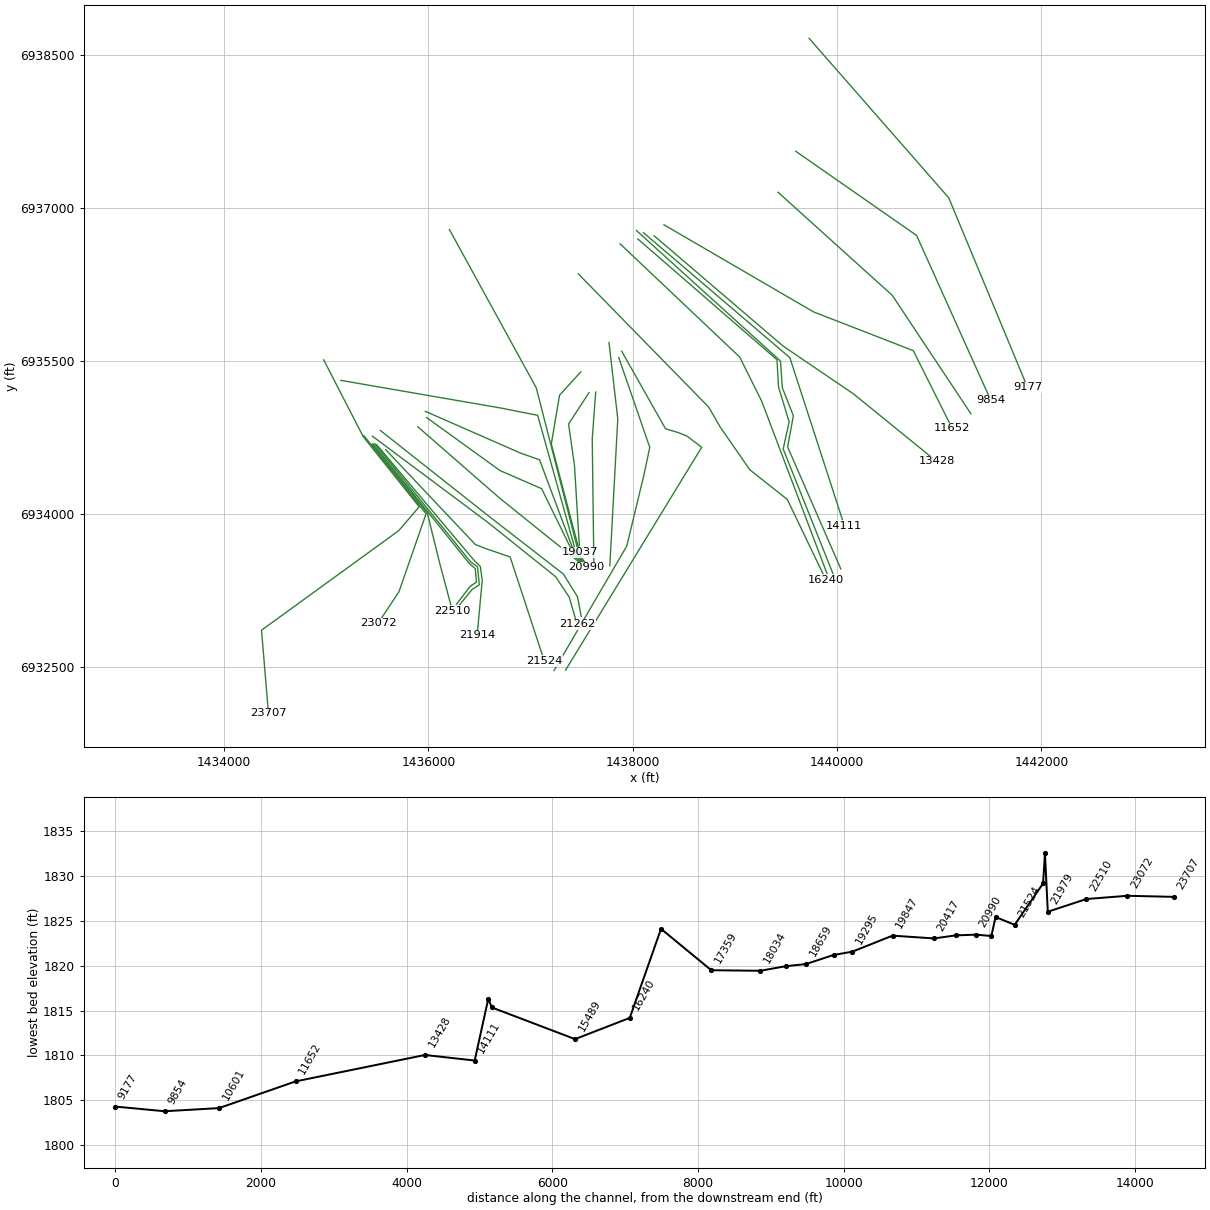
HEC-RAS study China Creek.prj: China Creek Base Level Engineering

--- China Creek.g01 (geometry) --- (continued)

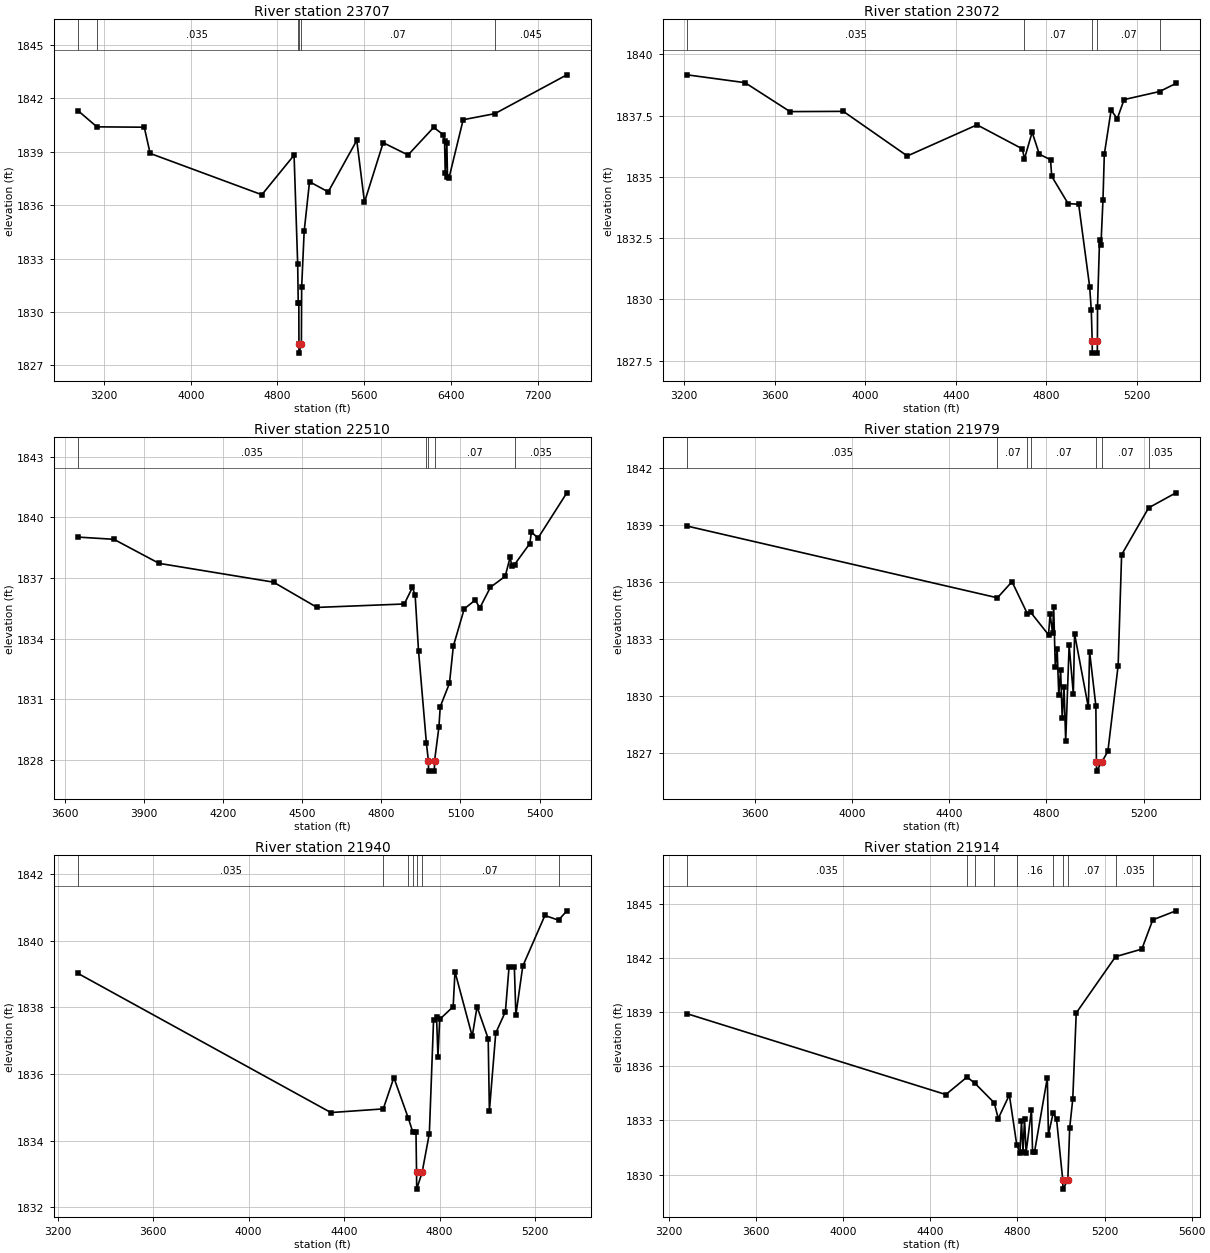
Type RM Length L Ch R = 1 ,23707   ,635,635,635
BEGIN DESCRIPTION:
Mapping XS 69f528a8
END DESCRIPTION:
XS GIS Cut Line= 6
      1434973.81       6935511.8      1435360.68      6934759.86
      1435909.02      6934071.64      1435708.47      6933838.17
      1434365.32      6932862.81      1434433.29      6932048.04
#Sta/Elev= 30
  2959.3  1841.3  3133.8 1840.39  3570.9 1840.37    3625  1838.9    4656 1836.58
  4953.2  1838.8  4986.5  1832.7  4991.5 1830.52  4997.1 1830.52    4998 1828.19
  4998.5 1827.69  5020.7 1828.19  5023.2  1831.4  5046.4 1834.53  5095.8 1837.31
  5268.2 1836.74  5531.8 1839.63  5602.9 1836.16  5775.5  1839.5  6004.9 1838.81
  6241.4 1840.36  6327.2 1839.96  6341.9 1839.59  6348.1 1837.78  6362.8 1839.48
  6368.9 1837.59  6383.6 1837.54  6513.5 1840.79  6805.8 1841.13  7470.2 1843.31
#Mann= 6 ,-1 , 0
  2959.3     .07       0  3133.8    .035       0  4986.5     .07       0
    4998     .07       0  5020.7     .07       0  6805.8    .045       0
Bank Sta=4998,5020.7
XS Rating Curve= 0 ,0
Exp/Cntr=0.3,0.1

Type RM Length L Ch R = 1 ,23072   ,562,562,562
BEGIN DESCRIPTION:
Mapping XS 12b94cb2
END DESCRIPTION:
XS GIS Cut Line= 4
      1435367.27      6934769.63      1435976.64        6934004.
      1435710.83      6933239.53      1435505.35      6932929.31
#Sta/Elev= 30
  3212.1 1839.16  3468.4 1838.84    3667 1837.66  3902.5 1837.67  4185.3 1835.85
  4493.4 1837.12  4693.7 1836.14  4702.7 1835.73  4736.9 1836.82  4768.7 1835.92
  4818.1  1835.7  4823.4 1835.02  4895.7 1833.91  4942.5 1833.88    4991 1830.52
  4998.2 1829.56  5002.2 1828.31  5002.7 1827.81  5024.8 1827.81  5025.3 1828.31
  5025.8 1829.71  5034.8 1832.44  5040.8  1832.2  5049.8 1834.05  5055.8 1835.92
  5085.8 1837.72    5113 1837.37  5143.1 1838.15  5300.4 1838.48  5372.1 1838.81
#Mann= 5 ,-1 , 0
  3212.1    .035       0  4702.7     .07       0  5002.2     .07       0
  5025.3     .07       0  5300.4    .045       0
Bank Sta=5002.2,5025.3
XS Rating Curve= 0 ,0
Exp/Cntr=0.3,0.1

Type RM Length L Ch R = 1 ,22510   ,531,531,531
BEGIN DESCRIPTION:
Mapping XS 47a7f259
END DESCRIPTION:
XS GIS Cut Line= 4
      1435448.37      6934683.37      1435988.85       6934010.6
       1436104.7      6933538.39      1436234.34      6933052.38
#Sta/Elev= 30
  3650.8 1839.03  3786.8 1838.92    3958 1837.73  4391.6  1836.8  4556.5 1835.55
  4887.1 1835.72    4918 1836.54  4928.3 1836.14    4941 1833.41    4971 1828.82
  4978.5 1827.95    4979 1827.45  5001.2 1827.45  5001.7 1827.95  5018.2 1829.62
  5023.4 1830.64  5058.3  1831.8  5072.9 1833.63  5114.2 1835.48  5155.6 1835.91
  5173.5 1835.53  5213.6 1836.55  5269.5 1837.09  5288.6 1838.06  5293.8 1837.58
  5304.8 1837.67  5362.6 1838.71  5368.8 1839.28  5393.7 1838.98    5503 1841.22
#Mann= 5 ,-1 , 0
  3650.8    .035       0    4971     .07       0  4978.5     .07       0
  5001.7     .07       0  5304.8    .035       0
Bank Sta=4978.5,5001.7
XS Rating Curve= 0 ,0
Exp/Cntr=0.3,0.1

Type RM Length L Ch R = 1 ,21979   ,39,39,39
BEGIN DESCRIPTION:
Mapping XS 23b04db7
END DESCRIPTION:
XS GIS Cut Line= 6
       1435456.4      6934690.89      1436398.58      6933517.86
      1436458.47      6933465.78      1436468.89      6933332.96
        1436409.       6933293.9      1436273.58      6933116.81
#Sta/Elev= 30
  3320.4 1838.94    4598 1835.16    4658 1836.01  4720.9 1834.33  4735.3 1834.39
  4808.4 1833.21  4814.8 1834.31    4825  1833.3  4829.6 1834.68  4836.2 1831.51
  4843.9 1832.47  4850.5 1830.04  4858.1 1831.38  4864.7 1828.81  4872.3 1830.44
    4879  1827.6  4893.2 1832.66  4910.5 1830.09  4915.6 1833.26  4972.3 1829.39
  4977.4 1832.32  5003.2 1829.47  5005.5 1826.53    5006 1826.03  5028.7 1826.53
  5052.7 1827.08  5094.9 1831.59  5109.2 1837.43  5220.5  1839.9  5332.7 1840.69
#Mann= 7 ,-1 , 0
  3320.4    .035       0    4598     .07       0  4720.9     .16       0
  4735.3     .07       0  5005.5     .07       0  5028.7     .07       0
  5220.5    .035       0
Bank Sta=5005.5,5028.7
XS Rating Curve= 0 ,0
Exp/Cntr=0.3,0.1

Type RM Length L Ch R = 1 ,21940   ,26,26,26
BEGIN DESCRIPTION:
Mapping XS f6119bab
END DESCRIPTION:
XS GIS Cut Line= 6
      1435475.49      6934689.17      1436414.02      6933530.47
      1436479.81      6933485.01      1436497.75      6933306.78
      1436428.37      6933263.72      1436294.43      6933098.67
#Sta/Elev= 30
    3285 1839.02  4344.5 1834.84  4563.8 1834.95  4608.2 1835.89  4668.3 1834.68
    4687 1834.27  4700.9 1834.25  4703.3 1833.04  4703.8 1832.54  4726.5 1833.04
  4756.9 1834.21  4774.5 1837.61  4787.1 1837.71  4792.9 1836.52  4800.2 1837.64
  4856.6 1838.02  4864.3 1839.07  4936.6 1837.13  4956.7 1838.02  5003.4 1837.06
  5008.4 1834.89  5035.1 1837.23  5075.5 1837.87  5090.6  1839.2  5112.9 1839.22
  5119.4 1837.77  5148.3 1839.24  5240.9 1840.76    5298 1840.62  5332.9  1840.9
#Mann= 7 ,-1 , 0
    3285    .035       0  4563.8     .07       0  4668.3     .16       0
    4687     .07       0  4703.3     .07       0  4726.5     .07       0
    5298    .035       0
Bank Sta=4703.3,4726.5
XS Rating Curve= 0 ,0
Exp/Cntr=0.3,0.1

Type RM Length L Ch R = 1 ,21914   ,390,390,390
BEGIN DESCRIPTION:
Mapping XS 9b7525b3
END DESCRIPTION:
XS GIS Cut Line= 5
       1435492.9      6934680.42      1436442.85      6933551.71
      1436507.95      6933486.61      1436526.18      6933351.19
      1436476.06      6932812.19
#Sta/Elev= 30
  3282.4 1838.91  4471.1 1834.43  4568.4  1835.4  4605.1 1835.05  4693.4 1833.97
  4711.7  1833.1  4762.7 1834.41  4796.9 1831.63  4811.3 1831.21  4818.4 1832.94
  4825.4 1831.25  4832.5 1833.07  4839.6 1831.21  4864.3 1833.59  4869.3 1831.24
  4878.6 1831.27  4937.1 1835.36  4942.1 1832.21  4964.3 1833.43  4979.5 1833.06
  5008.1 1829.69  5008.6 1829.19  5031.3 1829.69  5039.8 1832.58    5054 1834.18
  5069.9 1838.95  5250.5 1842.07  5371.2 1842.49  5421.4 1844.11  5527.7 1844.61
#Mann= 10 ,-1 , 0
  3282.4    .035       0  4568.4     .07       0  4605.1     .16       0
  4693.4     .07       0  4796.9     .16       0  4964.3     .07       0
  5008.1     .07       0  5031.3     .07       0  5250.5    .035       0
  5421.4     .07       0
Bank Sta=5008.1,5031.3
XS Rating Curve= 0 ,0
Exp/Cntr=0.3,0.1

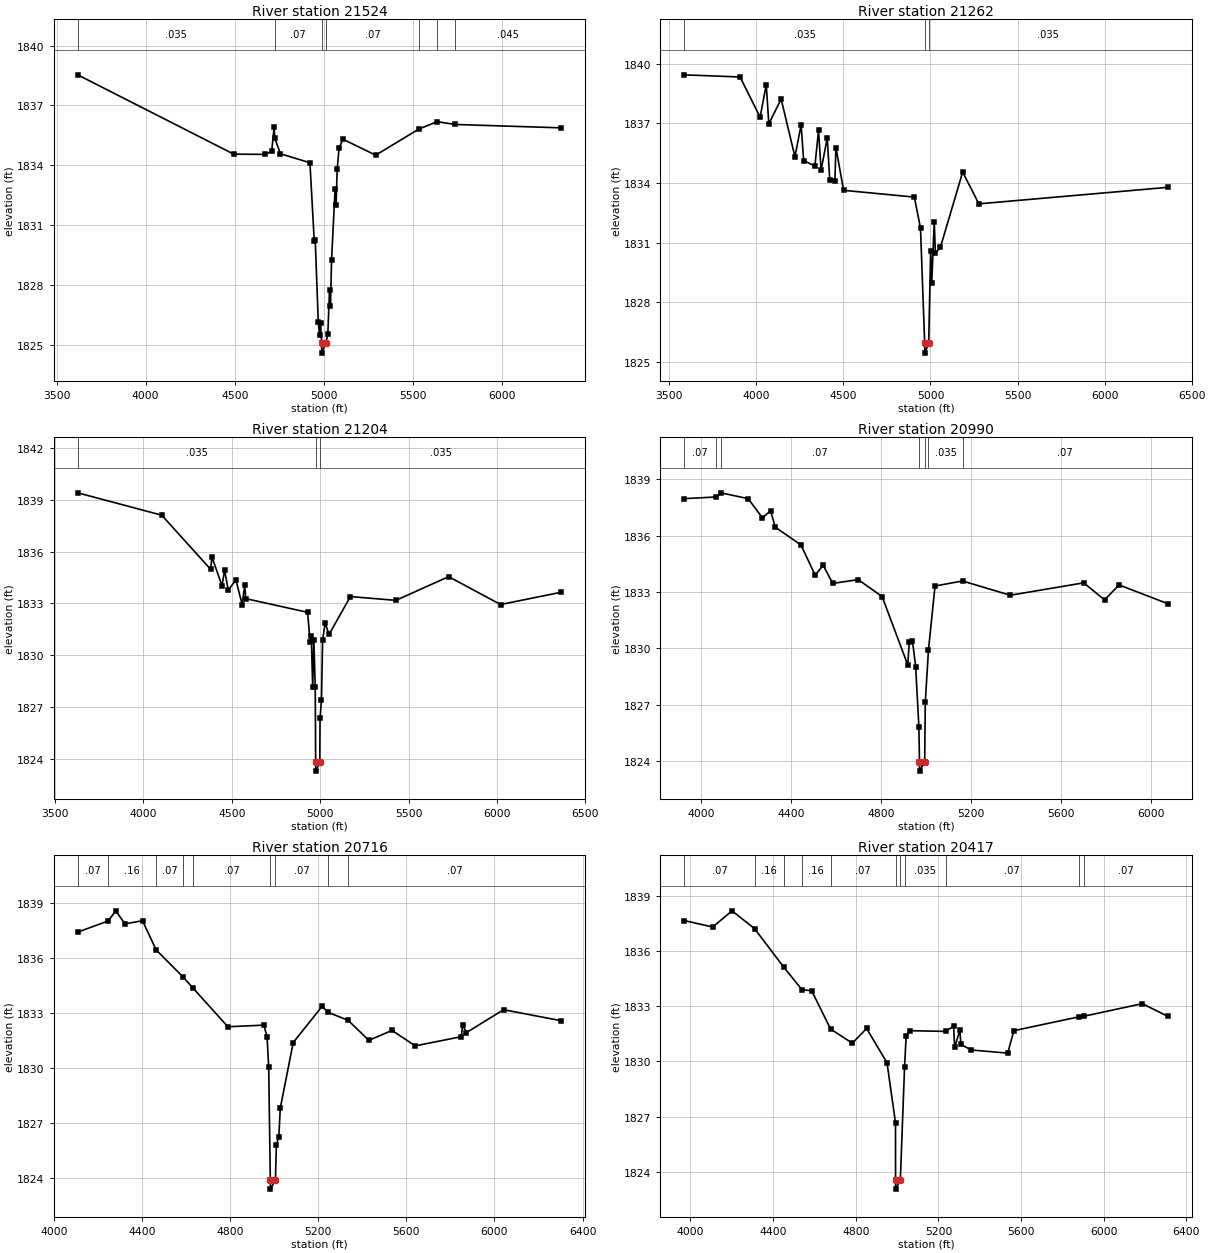
Type RM Length L Ch R = 1 ,21524   ,262,262,262
BEGIN DESCRIPTION:
Mapping XS 7becf89a
END DESCRIPTION:
XS GIS Cut Line= 5
       1435581.4      6934631.86      1436458.47      6933702.75
      1436556.76      6933663.93      1436799.61      6933580.22
      1437133.73      6932561.87
#Sta/Elev= 30
  3618.8 1838.53  4494.1 1834.55  4670.9 1834.54  4706.5 1834.69  4720.6 1835.91
    4724 1835.35  4755.8 1834.57  4921.3 1834.12  4945.7 1830.17  4951.1 1830.22
    4968 1826.13  4975.4 1825.46  4980.8 1826.06  4986.9 1825.07  4987.4 1824.57
  5010.1 1825.07  5021.5 1825.51  5031.2 1827.75  5036.5 1826.92  5042.6 1829.24
  5062.4 1832.82  5067.7 1831.98  5074.3 1833.83  5084.9 1834.85  5106.1  1835.3
    5290  1834.5  5532.3 1835.81  5634.4 1836.18  5736.5 1836.04  6330.8 1835.87
#Mann= 7 ,-1 , 0
  3618.8    .035       0    4724     .07       0  4986.9     .07       0
  5010.1     .07       0  5532.3    .035       0  5634.4     .07       0
  5736.5    .045       0
Bank Sta=4986.9,5010.1
XS Rating Curve= 0 ,0
Exp/Cntr=0.3,0.1

Type RM Length L Ch R = 1 ,21262   ,58,58,58
BEGIN DESCRIPTION:
Mapping XS fb2516fb
END DESCRIPTION:
XS GIS Cut Line= 5
      1435451.17      6934763.81      1436578.27       6933921.5
      1437244.03       6933387.9      1437378.32       6933186.3
       1437453.7      6932922.47
#Sta/Elev= 30
  3585.9 1839.44  3906.8 1839.33  4021.5 1837.31  4056.9 1838.95  4071.5 1836.97
  4142.4 1838.22  4221.6 1835.32    4257 1836.92  4271.6 1835.13  4336.2 1834.85
  4357.1 1836.65  4371.7 1834.64  4407.1 1836.27  4421.7 1834.13  4450.9 1834.12
  4457.1 1835.78  4500.9 1833.63  4907.3 1833.29  4942.8 1831.72  4966.6 1825.94
  4967.1 1825.44  4989.8 1825.94  5000.9 1830.59  5007.3 1828.99  5021.7 1832.05
  5028.1 1830.47  5056.9 1830.76  5184.9 1834.55  5277.8 1832.95  6362.8 1833.78
#Mann= 3 ,-1 , 0
  3585.9    .035       0  4966.6    .035       0  4989.8    .035       0
Bank Sta=4966.6,4989.8
XS Rating Curve= 0 ,0
Exp/Cntr=0.3,0.1

Type RM Length L Ch R = 1 ,21204   ,214,214,214
BEGIN DESCRIPTION:
Mapping XS d5a04e64
END DESCRIPTION:
XS GIS Cut Line= 5
       1435529.3      6934819.36       1436599.1      6933973.59
      1437321.03      6933412.86      1437459.05      6933190.21
       1437495.5      6932997.54
#Sta/Elev= 30
  3628.1 1839.39  4103.3  1838.1  4380.6 1834.97  4387.5 1835.69  4444.7 1834.02
  4459.1 1834.93    4480 1833.77  4523.3 1834.36  4558.5 1832.94  4572.9 1834.04
  4579.3 1833.28  4928.8 1832.49  4943.2 1830.78  4949.6 1831.14  4957.6 1828.17
    4964 1830.92  4972.1 1828.17  4974.4 1823.82  4974.9 1823.32  4997.6 1823.82
  4999.3  1826.4  5007.4 1827.42  5013.7  1830.9  5028.2 1831.87    5050 1831.21
  5171.2  1833.4  5428.2 1833.18  5726.9 1834.55  6020.7 1832.94    6364 1833.65
#Mann= 3 ,-1 , 0
  3628.1    .035       0  4974.4    .035       0  4997.6    .035       0
Bank Sta=4974.4,4997.6
XS Rating Curve= 0 ,0
Exp/Cntr=0.3,0.1

Type RM Length L Ch R = 1 ,20990   ,274,274,274
BEGIN DESCRIPTION:
Mapping XS 0e568efd
END DESCRIPTION:
XS GIS Cut Line= 3
      1435893.89      6934857.56      1436698.06      6934155.88
      1437539.76      6933477.98
#Sta/Elev= 30
  3924.9 1837.97  4066.5 1838.06  4087.8 1838.28  4208.7 1837.97  4272.3 1836.95
  4308.4 1837.33  4329.2 1836.45  4443.2 1835.51  4506.8 1833.89  4541.9 1834.43
  4584.6 1833.46  4697.6 1833.66  4803.9 1832.76  4917.8 1829.12  4924.4 1830.32
  4938.7  1830.4  4952.9 1829.03  4967.2 1825.83  4969.8 1823.97  4970.3 1823.47
    4993 1823.97  4995.7 1827.15  5009.7  1829.9  5038.9 1833.32    5161 1833.59
  5373.2 1832.83  5699.5 1833.49  5792.3 1832.58  5856.3 1833.38  6072.9 1832.38
#Mann= 7 ,-1 , 0
  3924.9     .07       0  4066.5     .16       0  4087.8     .07       0
  4969.8     .07       0    4993     .07       0  5009.7    .035       0
    5161     .07       0
Bank Sta=4969.8,4993
XS Rating Curve= 0 ,0
Exp/Cntr=0.3,0.1

Type RM Length L Ch R = 1 ,20716   ,299,299,299
BEGIN DESCRIPTION:
Mapping XS c08af9e5
END DESCRIPTION:
XS GIS Cut Line= 5
      1435982.48      6934946.06      1436700.66      6934426.71
      1437107.46       6934249.9      1437434.56      6933581.85
      1437525.89        6933502.
#Sta/Elev= 30
  4108.3  1837.4  4246.8 1838.01  4281.1 1838.56  4322.8 1837.85  4402.5 1838.02
  4464.4 1836.43  4588.5 1834.93  4630.1 1834.37  4790.1 1832.24  4953.2 1832.33
  4967.9  1831.7  4975.3 1830.02  4982.6 1823.89  4983.1 1823.39  5005.8 1823.89
  5010.2 1825.82  5021.1 1826.22  5027.8  1827.8  5086.6 1831.38  5217.4 1833.35
  5246.3 1833.02    5336 1832.59  5430.2  1831.5  5534.9 1832.04  5640.7  1831.2
    5850  1831.7  5855.5 1832.35  5872.5 1831.92  6041.5 1833.17  6303.3 1832.57
#Mann= 9 ,-1 , 0
  4108.3     .07       0  4246.8     .16       0  4464.4     .07       0
  4588.5     .16       0  4630.1     .07       0  4982.6     .07       0
  5005.8     .07       0  5246.3    .035       0    5336     .07       0
Bank Sta=4982.6,5005.8
XS Rating Curve= 0 ,0
Exp/Cntr=0.3,0.1

Type RM Length L Ch R = 1 ,20417   ,570,570,570
BEGIN DESCRIPTION:
Mapping XS b20ed11d
END DESCRIPTION:
XS GIS Cut Line= 5
      1435970.33      6935006.83      1436906.39      6934595.98
      1437087.21      6934532.81      1437433.61      6933607.89
       1437530.1      6933508.88
#Sta/Elev= 30
  3970.1 1837.66  4107.9 1837.31  4201.3 1838.19  4310.4 1837.22  4451.3 1835.13
  4539.6  1833.9  4586.8 1833.84  4678.1 1831.76  4783.3 1830.99  4852.4 1831.79
  4951.3 1829.92  4992.4 1826.65  4992.5 1823.55    4993 1823.05  5015.7 1823.55
  5036.2 1829.71  5043.8 1831.37  5060.9 1831.67  5236.5 1831.63  5273.3 1831.92
  5278.6 1830.76  5303.5 1831.69  5308.9 1830.92  5358.7 1830.62    5535 1830.45
  5565.3 1831.67  5878.2 1832.42  5906.1 1832.46  6186.5 1833.14  6309.8 1832.45
#Mann= 11 ,-1 , 0
  3970.1     .07       0  4310.4     .16       0  4451.3     .07       0
  4539.6     .16       0  4678.1     .07       0  4992.5     .07       0
  5015.7     .07       0  5036.2    .035       0  5236.5     .07       0
  5878.2    .035       0  5906.1     .07       0
Bank Sta=4992.5,5015.7
XS Rating Curve= 0 ,0
Exp/Cntr=0.3,0.1

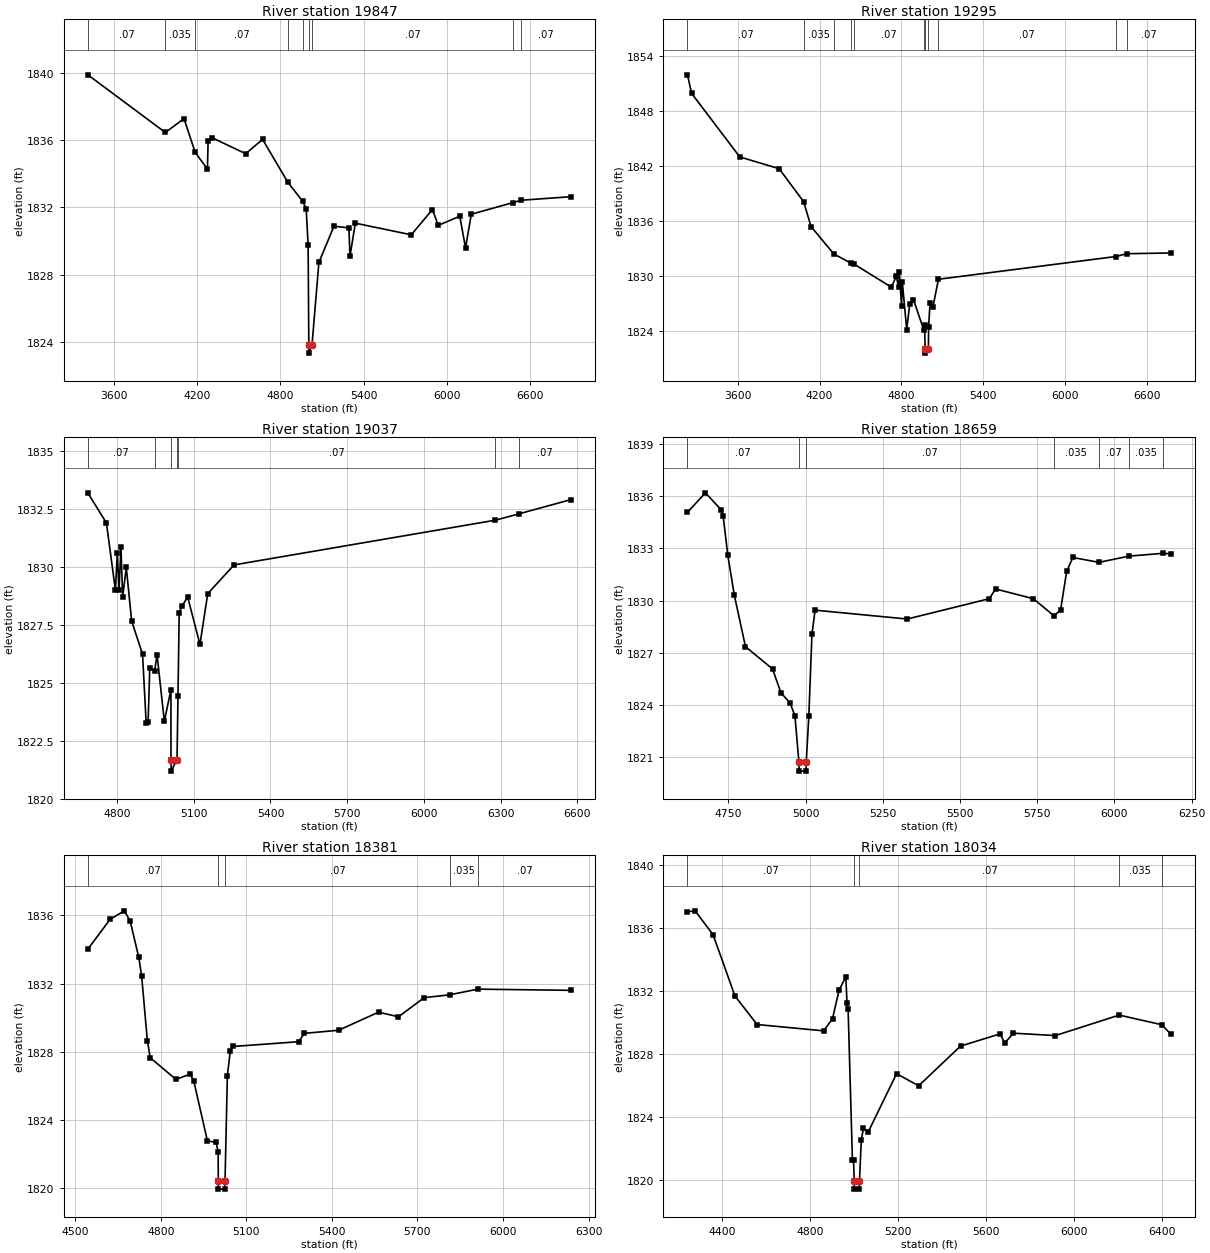
Type RM Length L Ch R = 1 ,19847   ,552,552,552
BEGIN DESCRIPTION:
Mapping XS 78674b83
END DESCRIPTION:
XS GIS Cut Line= 5
      1435142.23      6935310.65      1436708.74      6935039.56
      1437069.15      6934968.38      1437444.48       6933623.6
      1437527.54      6933518.51
#Sta/Elev= 30
  3410.2 1839.87  3969.6 1836.45  4104.2 1837.27    4185 1835.27  4273.3 1834.28
  4278.4 1835.96  4306.1 1836.14  4549.7 1835.19  4671.4 1836.04  4852.6 1833.51
  4960.4 1832.37  4986.1 1831.92    5000 1829.76    5005 1823.86  5005.5 1823.36
  5028.2 1823.86  5077.7 1828.74  5186.7 1830.89  5294.4 1830.79    5302  1829.1
  5340.6 1831.07  5744.6 1830.38  5897.3 1831.88  5938.8 1830.94  6094.5 1831.48
    6136  1829.6  6177.6  1831.6  6478.5 1832.29  6537.7 1832.43  6897.5 1832.64
#Mann= 9 ,-1 , 0
  3410.2     .07       0  3969.6    .035       0    4185     .07       0
  4852.6     .16       0  4960.4     .07       0    5005     .07       0
  5028.2     .07       0  6478.5    .035       0  6537.7     .07       0
Bank Sta=5005,5028.2
XS Rating Curve= 0 ,0
Exp/Cntr=0.3,0.1

Type RM Length L Ch R = 1 ,19295   ,258,258,258
BEGIN DESCRIPTION:
China Creek 12.0
END DESCRIPTION:
XS GIS Cut Line= 4
      1436204.98      6936788.04        1437055.        6935238.
      1437474.78      6933602.51      1437527.54      6933534.48
#Sta/Elev= 30
  3232.2 1851.97  3262.1 1849.95  3615.6    1843  3903.8 1841.72  4083.4 1838.12
  4137.9  1835.4  4305.1  1832.4  4430.8  1831.4  4450.7 1831.32  4726.3 1828.78
  4763.5 1829.96  4779.6 1828.74  4785.3 1830.38  4801.4 1826.69  4807.1 1829.31
  4839.3 1824.15  4861.1 1826.89  4888.6 1827.42  4965.5 1824.06  4970.2 1824.62
  4974.5 1822.07    4975 1821.57  4998.1 1822.07    5000 1824.45  5010.3  1827.1
    5031 1826.58  5071.9 1829.64  6371.2 1832.12  6454.1 1832.43  6774.6 1832.51
#Mann= 11 ,-1 , 0
  3232.2     .07       0  4083.4    .035       0  4305.1     .07       0
  4430.8    .035       0  4450.7     .07       0  4965.5     .16       0
  4974.5     .07       0  4998.1     .16       0  5071.9     .07       0
  6371.2    .035       0  6454.1     .07       0
Bank Sta=4974.5,4998.1
XS Rating Curve= 0 ,0
Exp/Cntr=0.3,0.1

Type RM Length L Ch R = 1 ,19037   ,378,378,378
BEGIN DESCRIPTION:
Mapping XS 4976b646
END DESCRIPTION:
XS GIS Cut Line= 4
      1437491.38      6935394.09      1437283.02      6935164.89
      1437202.54       6934687.6      1437479.89      6933627.67
#Sta/Elev= 30
  4685.9 1833.21  4758.6 1831.91  4793.8 1829.01  4801.2 1830.62  4807.9 1829.03
  4815.4 1830.86  4822.1 1828.72  4836.3 1829.99  4857.3 1827.67  4899.8 1826.25
    4914 1823.28  4921.5 1823.32  4928.2 1825.67    4947 1825.52  4956.6 1826.23
    4985 1823.35  5010.8 1824.71  5011.1  1821.7  5011.6  1821.2  5034.7  1821.7
  5038.4 1824.46  5043.2 1828.04  5053.3 1828.31  5076.3 1828.71  5124.3 1826.67
  5154.8 1828.86  5257.8  1830.1  6279.6 1832.03  6370.9  1832.3  6575.3 1832.92
#Mann= 7 ,-1 , 0
  4685.9     .07       0    4947     .16       0  5011.1     .07       0
  5034.7     .16       0  5038.4     .07       0  6279.6    .035       0
  6370.9     .07       0
Bank Sta=5011.1,5034.7
XS Rating Curve= 0 ,0
Exp/Cntr=0.3,0.1

Type RM Length L Ch R = 1 ,18659   ,278,278,278
BEGIN DESCRIPTION:
Mapping XS b9d4fa95
END DESCRIPTION:
XS GIS Cut Line= 4
      1437572.09      6935190.93      1437371.56      6934883.64
      1437429.59      6934474.71      1437477.19      6933691.91
#Sta/Elev= 30
  4617.8 1835.08  4675.8  1836.2  4727.1 1835.22  4733.1 1834.89  4748.2 1832.62
  4769.3 1830.32  4805.5 1827.35    4893 1826.07  4920.1 1824.71  4950.3 1824.09
  4965.5 1823.38  4978.6 1820.69  4979.1 1820.19  5001.7 1820.19  5002.2 1820.69
  5010.6 1823.38  5020.7 1828.06  5030.8 1829.45  5329.1 1828.94  5594.8 1830.11
  5614.9 1830.67  5737.1 1830.11  5803.8 1829.13  5825.3 1829.44  5845.3 1831.69
  5865.3 1832.48  5949.7  1832.2  6047.6 1832.56  6156.8 1832.72    6182 1832.69
#Mann= 7 ,-1 , 0
  4617.8     .07       0  4978.6     .07       0  5002.2     .07       0
  5803.8    .035       0  5949.7     .07       0  6047.6    .035       0
  6156.8     .07       0
Bank Sta=4978.6,5002.2
XS Rating Curve= 0 ,0
Exp/Cntr=0.3,0.1

Type RM Length L Ch R = 1 ,18381   ,347,347,347
BEGIN DESCRIPTION:
Mapping XS 9b6a43f5
END DESCRIPTION:
XS GIS Cut Line= 3
      1437637.19      6935196.18      1437603.34      6934737.81
       1437619.2      6933502.83
#Sta/Elev= 30
  4544.1 1834.01  4622.5 1835.77  4672.6 1836.26  4692.7 1835.65  4722.8 1833.53
  4732.8 1832.45  4752.8 1828.66  4762.9 1827.65  4853.1 1826.38  4903.3 1826.69
  4915.8 1826.28  4963.4 1822.78  4993.5 1822.69  5001.1 1822.15  5001.7 1820.45
  5002.2 1819.95  5024.8 1819.95  5025.3 1820.45  5033.5  1826.6  5043.5 1828.02
  5053.5 1828.31  5283.6 1828.59  5303.6 1829.08  5423.6 1829.26  5563.6 1830.32
  5633.6 1830.05  5723.6 1831.17  5813.7 1831.34  5911.5 1831.67  6238.8  1831.6
#Mann= 5 ,-1 , 0
  4544.1     .07       0  5001.7     .07       0  5025.3     .07       0
  5813.7    .035       0  5911.5     .07       0
Bank Sta=5001.7,5025.3
XS Rating Curve= 0 ,0
Exp/Cntr=0.3,0.1

Type RM Length L Ch R = 1 ,18034   ,675,675,675
BEGIN DESCRIPTION:
Mapping XS aac6aa18
END DESCRIPTION:
XS GIS Cut Line= 3
      1437767.18      6935682.19      1437853.34      6934933.12
      1437775.46      6933494.94
#Sta/Elev= 30
  4243.7 1837.05  4278.1 1837.11  4359.8  1835.6  4459.3  1831.7    4560 1829.89
  4861.9 1829.49  4902.2 1830.26  4932.4 1832.09  4962.6 1832.91  4968.1 1831.28
  4973.1 1830.85  4992.7 1821.27  4997.7 1821.27  5001.1 1819.94  5001.6 1819.44
  5024.2 1819.44  5024.7 1819.94  5032.9 1822.57  5042.9 1823.31  5063.7 1823.05
  5193.1 1826.77  5293.3    1826  5483.5 1828.52  5663.8  1829.3  5683.8 1828.71
  5723.9 1829.34  5914.2 1829.19  6204.1 1830.49  6396.6 1829.88    6438 1829.29
#Mann= 5 ,-1 , 0
  4243.7     .07       0  5001.1     .07       0  5024.7     .07       0
  6204.1    .035       0  6396.6     .07       0
Bank Sta=5001.1,5024.7
XS Rating Curve= 0 ,0
Exp/Cntr=0.3,0.1

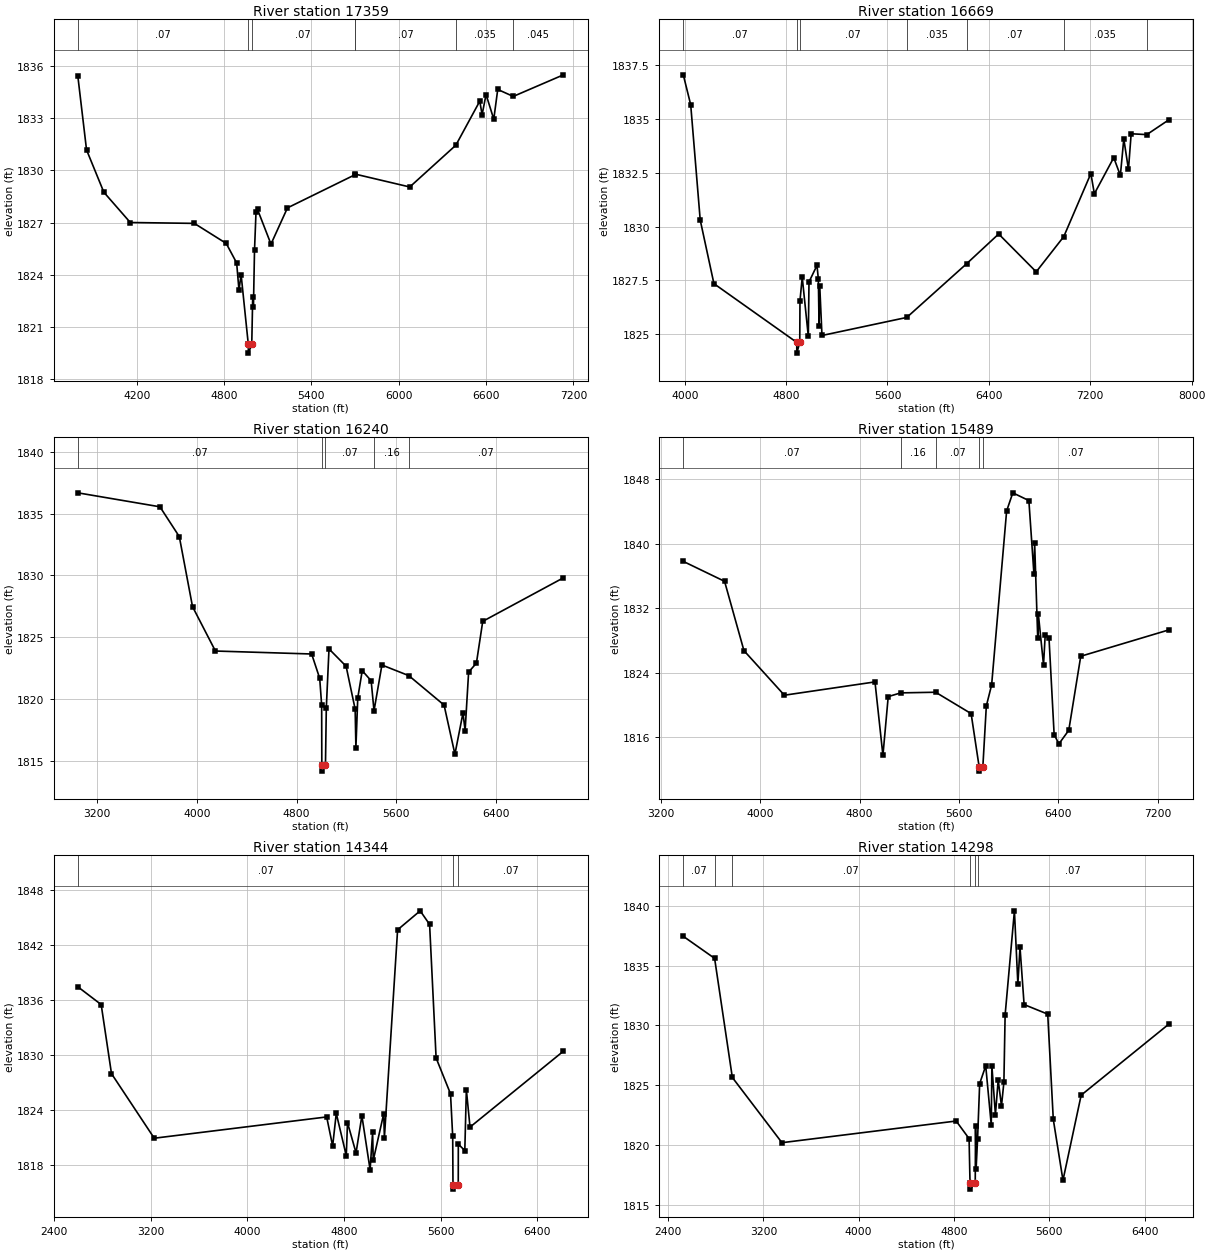
Type RM Length L Ch R = 1 ,17359   ,690,690,690
BEGIN DESCRIPTION:
Mapping XS 16ef2bd3
END DESCRIPTION:
XS GIS Cut Line= 5
      1437862.65      6935534.66      1438166.49      6934654.41
      1438110.01      6934387.12      1437941.29      6933687.16
      1437229.76      6932468.01
#Sta/Elev= 30
  3795.6 1835.41  3855.5 1831.17  3974.3 1828.74  4156.1    1827  4596.1 1826.95
  4815.1  1825.8  4886.7 1824.68  4902.7 1823.12  4917.3 1824.01  4966.8    1820
  4967.3  1819.5  4990.5    1820    4997 1822.73  5002.1 1822.17  5009.4  1825.4
  5019.7  1827.6    5030 1827.75  5122.5 1825.76  5235.7 1827.84  5696.4 1829.73
  5700.6 1829.78  6075.9 1829.04  6392.7 1831.44  6557.1 1833.97  6572.8 1833.19
  6600.1 1834.35  6653.1 1832.93  6680.3 1834.64  6786.9 1834.24  7131.6 1835.48
#Mann= 7 ,-1 , 0
  3795.6     .07       0  4966.8     .07       0  4990.5     .07       0
  5696.4    .035       0  5700.6     .07       0  6392.7    .035       0
  6786.9    .045       0
Bank Sta=4966.8,4990.5
XS Rating Curve= 0 ,0
Exp/Cntr=0.3,0.1

Type RM Length L Ch R = 1 ,16669   ,429,429,429
BEGIN DESCRIPTION:
Mapping XS 97e15d74
END DESCRIPTION:
XS GIS Cut Line= 6
      1437892.17       6935595.4        1438321.       6934836.7
      1438448.62      6934798.02      1438532.81      6934763.78
       1438674.8      6934655.04      1437342.67      6932472.43
#Sta/Elev= 30
  3988.8 1837.06  4047.2 1835.67  4122.3 1830.31  4230.5 1827.35    4884 1824.62
  4884.5 1824.12  4907.7 1824.62  4909.5 1826.56  4927.2 1827.65  4975.3  1824.9
  4980.6 1827.43  5043.7  1828.2  5054.5 1827.56    5060 1825.38  5065.4 1827.25
    5083 1824.94  5752.3 1825.78  6224.9 1828.28  6477.2 1829.66  6773.4  1827.9
  6991.1 1829.54  7204.7 1832.47  7232.2 1831.53  7385.2 1833.21  7437.4 1832.38
  7464.5 1834.08  7501.3 1832.66  7522.6 1834.32  7645.9 1834.28  7820.4 1834.97
#Mann= 7 ,-1 , 0
  3988.8     .07       0    4884     .07       0  4907.7     .07       0
  5752.3    .035       0  6224.9     .07       0  6991.1    .035       0
  7645.9    .045       0
Bank Sta=4884,4907.7
XS Rating Curve= 0 ,0
Exp/Cntr=0.3,0.1

Type RM Length L Ch R = 1 ,16240   ,751,751,751
BEGIN DESCRIPTION:
Mapping XS 80bbc28c
END DESCRIPTION:
XS GIS Cut Line= 6
      1437468.04      6936353.26      1438743.53       6935048.7
      1438856.38      6934853.39      1439145.77      6934434.81
      1439513.21      6934144.12      1439889.88      6933358.51
#Sta/Elev= 30
  3043.8 1836.68    3703 1835.55  3858.6 1833.14  3964.6 1827.48  4148.5 1823.89
  4921.1 1823.65  4985.8 1821.68  5001.5 1819.51  5002.7 1814.68  5003.2 1814.18
    5032 1814.68  5038.8 1819.29  5060.4 1824.06  5197.7 1822.66  5270.3 1819.19
  5276.4 1816.08  5291.3  1820.1  5327.1  1822.3  5398.7 1821.49  5421.8 1819.06
  5485.2 1822.76  5701.3  1821.9  5984.3 1819.52  6071.3 1815.55  6136.1 1818.88
  6153.2 1817.46  6181.4 1822.19  6243.9 1822.91  6294.7 1826.29  6942.5 1829.81
#Mann= 5 ,-1 , 0
  3043.8     .07       0  5002.7     .07       0    5032     .07       0
  5421.8     .16       0  5701.3     .07       0
Bank Sta=5002.7,5032
XS Rating Curve= 0 ,0
Exp/Cntr=0.3,0.1

Type RM Length L Ch R = 1 ,15489   ,1145,1145,1145
BEGIN DESCRIPTION:
Mapping XS 6d55e781
END DESCRIPTION:
XS GIS Cut Line= 4
      1437876.01      6936648.41      1439047.35      6935539.15
       1439262.2       6935107.3      1439902.92      6933414.89
#Sta/Elev= 30
  3382.8 1837.81  3714.7 1835.34  3870.5 1826.75  4195.7 1821.22  4924.3 1822.87
  4988.2 1813.76  5030.8 1821.05  5131.4 1821.51  5412.1 1821.59  5697.5 1818.94
  5762.3 1812.31  5762.8 1811.81  5791.7 1812.31  5819.8 1819.89  5862.4  1822.5
    5983 1844.06  6032.7 1846.31  6161.9 1845.35  6202.9 1836.19  6208.3 1840.09
  6233.1 1828.29  6238.4 1831.24  6279.6 1824.99  6293.4 1828.71  6323.6 1828.37
  6365.1 1816.34  6403.4 1815.19  6482.7 1816.87    6579 1826.05    7288 1829.32
#Mann= 5 ,-1 , 0
  3382.8     .07       0  5131.4     .16       0  5412.1     .07       0
  5762.3     .07       0  5791.7     .07       0
Bank Sta=5762.3,5791.7
XS Rating Curve= 0 ,0
Exp/Cntr=0.3,0.1

Type RM Length L Ch R = 1 ,14344   ,46,46,46
BEGIN DESCRIPTION:
Mapping XS 755d4580
END DESCRIPTION:
XS GIS Cut Line= 6
      1438049.65      6936696.13      1439411.93      6935512.98
      1439427.12      6935246.05      1439531.29      6934903.17
      1439472.69      6934638.41      1439959.35      6933419.22
#Sta/Elev= 30
  2595.2 1837.41  2788.7 1835.47  2874.1 1827.94  3228.3  1820.9  4656.8 1823.22
  4706.3 1820.05  4736.3 1823.61  4819.3    1819  4829.3 1822.61  4900.1  1819.3
  4948.5 1823.35  5016.6 1817.46  5037.4 1821.53  5042.5 1818.48  5129.7 1823.59
  5134.9 1820.94  5244.4 1843.62  5431.4 1845.69  5509.5 1844.21  5563.4 1829.65
  5682.8 1825.74  5700.9 1821.09  5703.2 1815.85  5704.2 1815.35    5747 1815.85
  5747.4 1820.25  5801.2 1819.56    5814 1826.19  5844.3 1822.11  6618.2 1830.39
#Mann= 3 ,-1 , 0
  2595.2     .07       0  5703.2     .07       0    5747     .07       0
Bank Sta=5703.2,5747
XS Rating Curve= 0 ,0
Exp/Cntr=0.3,0.1

Type RM Length L Ch R = 1 ,14298   ,187,187,187
BEGIN DESCRIPTION:
Mapping XS d59c1568
END DESCRIPTION:
XS GIS Cut Line= 6
       1438036.6      6936778.63      1439446.65      6935499.96
      1439464.01      6935239.54      1439572.52      6934963.94
      1439516.35      6934658.55      1440037.38      6933462.85
#Sta/Elev= 30
  2527.8 1837.45  2790.6 1835.61  2939.4 1825.66  3355.9 1820.21  4818.4 1822.02
  4926.7 1820.55  4934.6 1816.83  4935.6 1816.33  4978.4 1816.83  4980.9 1821.58
  4985.8 1818.05  4997.9  1820.5  5015.6 1825.15  5066.4 1826.63  5112.9 1821.69
    5118 1826.64  5147.8 1822.55  5171.1 1825.45  5198.6 1823.28  5218.9 1825.25
  5229.2 1830.88  5307.3 1839.58  5336.2 1833.47  5354.2 1836.53  5388.5 1831.75
  5586.8 1830.95  5633.6 1822.15  5714.8 1817.07  5867.5 1824.18    6604 1830.12
#Mann= 6 ,-1 , 0
  2527.8     .07       0  2790.6    .035       0  2939.4     .07       0
  4934.6     .07       0  4978.4     .07       0  4997.9     .07       0
Bank Sta=4934.6,4978.4
XS Rating Curve= 0 ,0
Exp/Cntr=0.3,0.1

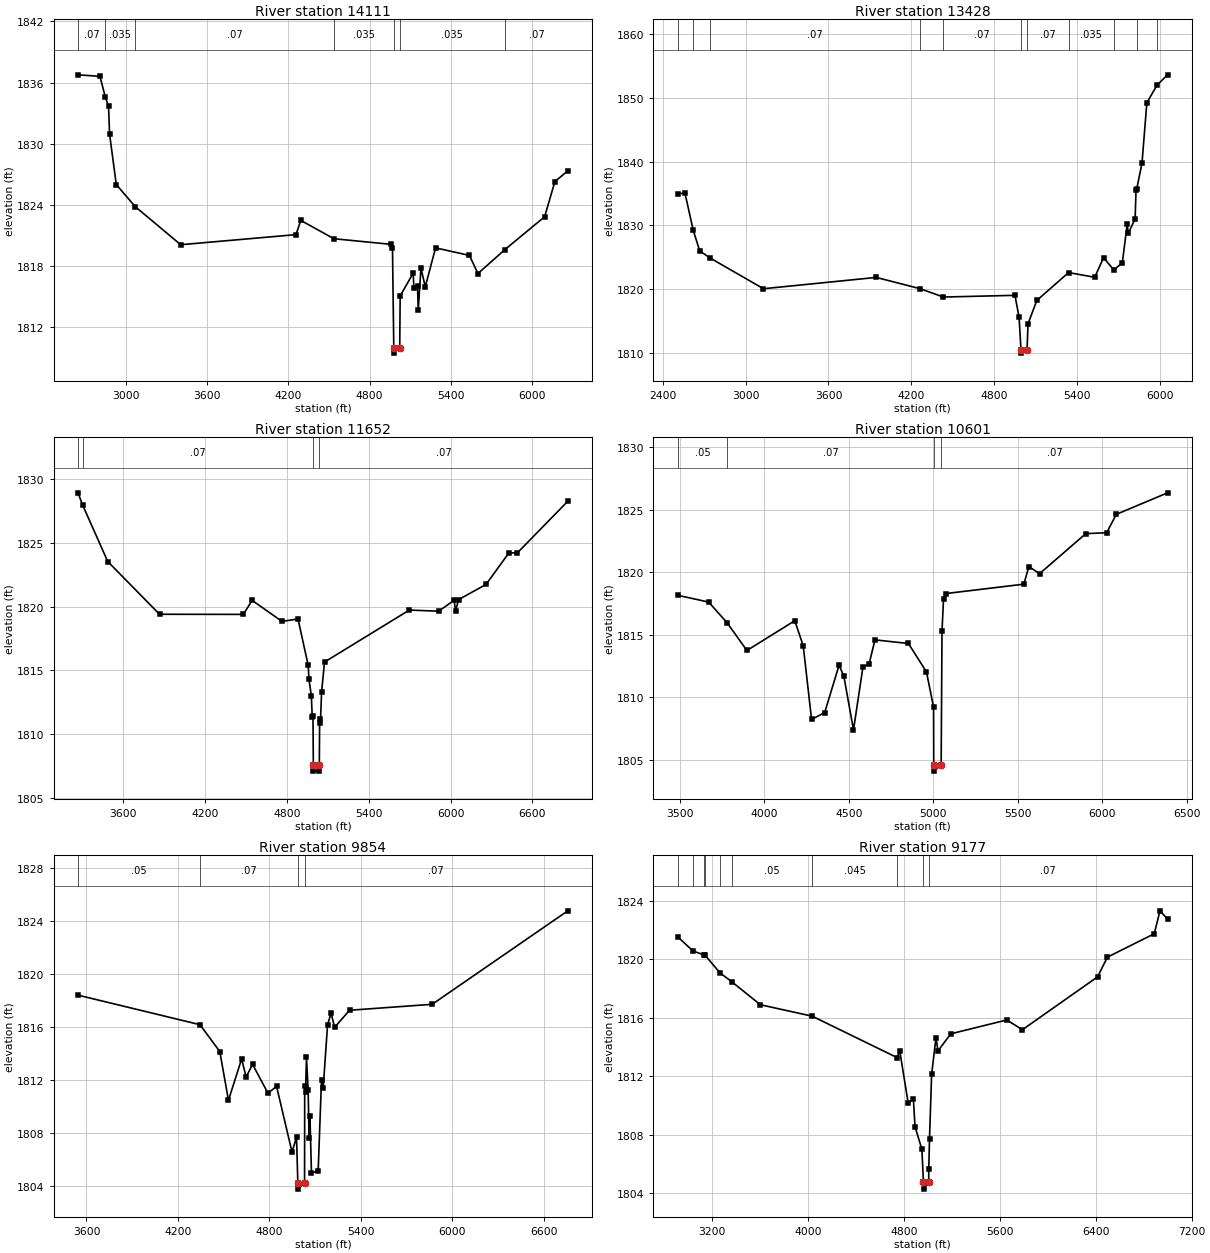
Type RM Length L Ch R = 1 ,14111   ,683,683,683
BEGIN DESCRIPTION:
Mapping XS 03016d05
END DESCRIPTION:
XS GIS Cut Line= 3
      1438106.08       6936756.9      1439538.33      6935532.97
      1440071.66      6933887.51
#Sta/Elev= 30
  2648.9 1836.76  2810.4 1836.61  2851.2 1834.54    2874 1833.67  2881.7 1830.93
  2931.1 1825.98  3070.4 1823.82  3406.5 1820.07  4257.3 1821.06  4292.4 1822.46
  4536.7 1820.66  4956.6 1820.11  4969.1 1819.74  4978.7 1809.92  4979.7 1809.42
  5022.5 1809.92  5025.8 1815.04  5121.8 1817.28    5127 1815.81  5153.8 1815.98
    5159 1813.66  5179.3 1817.77  5210.9 1815.93    5287 1819.76  5536.7 1819.02
  5599.8 1817.24  5798.5 1819.59  6091.8 1822.82  6167.5 1826.28  6262.6 1827.32
#Mann= 7 ,-1 , 0
  2648.9     .07       0  2851.2    .035       0  3070.4     .07       0
  4536.7    .035       0  4978.7    .035       0  5022.5    .035       0
  5798.5     .07       0
Bank Sta=4978.7,5022.5
XS Rating Curve= 0 ,0
Exp/Cntr=0.3,0.1

Type RM Length L Ch R = 1 ,13428   ,1776,1776,1776
BEGIN DESCRIPTION:
Mapping XS 5e7dde01
END DESCRIPTION:
XS GIS Cut Line= 4
      1438210.22      6936726.54      1439473.23      6935645.82
      1440160.63      6935178.78      1440974.42      6934516.89
#Sta/Elev= 30
  2510.5    1835  2562.5 1835.02  2622.2 1829.23    2669 1826.03  2742.7 1824.93
    3130 1820.11  3945.6 1821.88  4264.1 1820.11  4430.7 1818.81  4948.8 1819.08
  4978.7 1815.65  4992.5 1810.54  4993.5 1810.04  5036.4 1810.54  5043.2 1814.62
  5107.1 1818.28  5336.6 1822.64  5525.8  1821.9  5589.7 1824.97  5664.3 1823.04
  5725.5 1824.19  5760.7 1830.18  5768.6 1828.75  5818.2 1831.08  5824.6 1835.57
  5829.4 1835.69  5867.7 1839.75  5902.9  1849.2  5977.9 1851.99  6052.8 1853.56
#Mann= 11 ,-1 , 0
  2510.5     .07       0  2622.2    .035       0  2742.7     .07       0
  4264.1    .035       0  4430.7     .07       0  4992.5     .07       0
  5036.4     .07       0  5336.6    .035       0  5664.3     .07       0
  5829.4    .035       0  5977.9     .07       0
Bank Sta=4992.5,5036.4
XS Rating Curve= 0 ,0
Exp/Cntr=0.3,0.1

Type RM Length L Ch R = 1 ,11652   ,1051,1051,1051
BEGIN DESCRIPTION:
Mapping XS c5808348
END DESCRIPTION:
XS GIS Cut Line= 4
      1438305.73      6936835.03        1439770.      6935981.73
      1440746.56      6935601.96      1441126.17      6934842.74
#Sta/Elev= 30
  3267.7 1828.93  3300.7 1827.99  3485.6 1823.54  3865.2  1819.4  4479.8 1819.39
  4544.3 1820.49  4763.5 1818.84    4881 1819.03  4955.4 1815.39  4961.2 1814.31
  4978.6 1812.99  4985.2 1811.34  4990.6 1811.41  4993.2 1807.59  4994.2 1807.09
  5036.1 1807.09  5037.1 1807.59  5039.6 1811.19    5045 1810.86  5053.7 1813.28
  5075.1 1815.65  5697.4 1819.73    5912 1819.64  6025.9  1820.5  6035.9 1819.66
  6058.2 1820.55  6259.5 1821.74  6428.4 1824.23  6488.7 1824.21  6859.1 1828.27
#Mann= 4 ,-1 , 0
  3267.7    .035       0  3300.7     .07       0  4993.2     .07       0
  5037.1     .07       0
Bank Sta=4993.2,5037.1
XS Rating Curve= 0 ,0
Exp/Cntr=0.3,0.1

Type RM Length L Ch R = 1 ,10601   ,747,747,747
BEGIN DESCRIPTION:
Mapping XS dba37d8b
END DESCRIPTION:
XS GIS Cut Line= 3
      1439422.75      6937153.63       1440540.4      6936144.49
      1441310.41      6934984.05
#Sta/Elev= 30
  3487.5 1818.16    3670 1817.62  3779.5 1815.96  3896.4 1813.75  4179.6 1816.13
  4229.7 1814.12    4279 1808.24  4356.7 1808.79  4441.9 1812.58  4470.3 1811.68
  4527.1  1807.4  4583.2 1812.44    4619 1812.65  4654.2  1814.6  4852.2 1814.31
    4959 1812.04  5001.1 1809.22    5002 1804.61    5003 1804.11  5045.9 1804.61
    5051 1815.29    5060 1817.87  5073.1  1818.3  5535.2 1819.05  5565.2 1820.46
  5628.4 1819.89  5902.1 1823.09  6025.4 1823.16  6082.5 1824.63    6386 1826.35
#Mann= 4 ,-1 , 0
  3487.5     .05       0  3779.5     .07       0    5002     .07       0
  5045.9     .07       0
Bank Sta=5002,5045.9
XS Rating Curve= 0 ,0
Exp/Cntr=0.3,0.1

Type RM Length L Ch R = 1 ,9854    ,677,677,677
BEGIN DESCRIPTION:
Mapping XS 64ef5510
END DESCRIPTION:
XS GIS Cut Line= 3
      1439596.37      6937555.09      1440779.12      6936730.43
       1441506.1      6935113.72
#Sta/Elev= 30
  3544.9 1818.41  4345.3 1816.18  4475.5 1814.15  4532.2 1810.47  4618.6 1813.59
  4648.3 1812.22  4690.1 1813.19  4791.4 1811.01  4848.1 1811.52  4949.3 1806.56
    4979 1807.68  4987.5 1804.26  4988.5 1803.76  5031.7 1804.26  5032.7 1811.54
  5038.2 1811.07  5044.2 1813.72  5055.2 1811.24  5061.4 1807.63  5066.9 1809.32
  5077.1 1804.99    5121 1805.13  5142.9 1812.04  5153.9 1811.39  5182.6 1816.15
  5205.8 1817.06    5229 1815.98  5327.1 1817.27  5869.4 1817.72  6759.4 1824.78
#Mann= 4 ,-1 , 0
  3544.9     .05       0  4345.3     .07       0  4987.5     .07       0
  5031.7     .07       0
Bank Sta=4987.5,5031.7
XS Rating Curve= 0 ,0
Exp/Cntr=0.3,0.1

Type RM Length L Ch R = 1 ,9177    ,921,921,921
BEGIN DESCRIPTION:
Mapping XS 45e43f21
END DESCRIPTION:
XS GIS Cut Line= 3
      1439726.58      6938661.88      1441093.79      6937099.35
      1441864.19      6935243.87
#Sta/Elev= 30
  2913.3 1821.54  3040.4 1820.58  3132.2 1820.31  3138.1 1820.32  3265.1 1819.08
  3361.2 1818.49  3602.3  1816.9  4033.7 1816.12  4740.8 1813.29    4765 1813.72
  4835.2 1810.15  4877.9 1810.47  4892.2 1808.54  4949.1 1807.01  4962.1 1804.78
  4963.1 1804.28  5006.3 1804.78  5006.5 1805.63  5012.7 1807.74  5030.4 1812.14
  5066.8 1814.65  5083.5 1813.74  5189.8 1814.91  5657.3 1815.86  5787.5 1815.19
  6414.4 1818.81  6496.8 1820.16  6887.3 1821.76    6935 1823.33  6998.6 1822.76
#Mann= 10 ,-1 , 0
  2913.3     .07       0  3040.4     .05       0  3132.2     .07       0
  3138.1     .05       0  3265.1     .07       0  3361.2     .05       0
  4033.7    .045       0  4740.8     .07       0  4962.1     .07       0
  5006.3     .07       0
Bank Sta=4962.1,5006.3
XS Rating Curve= 0 ,0
Exp/Cntr=0.3,0.1