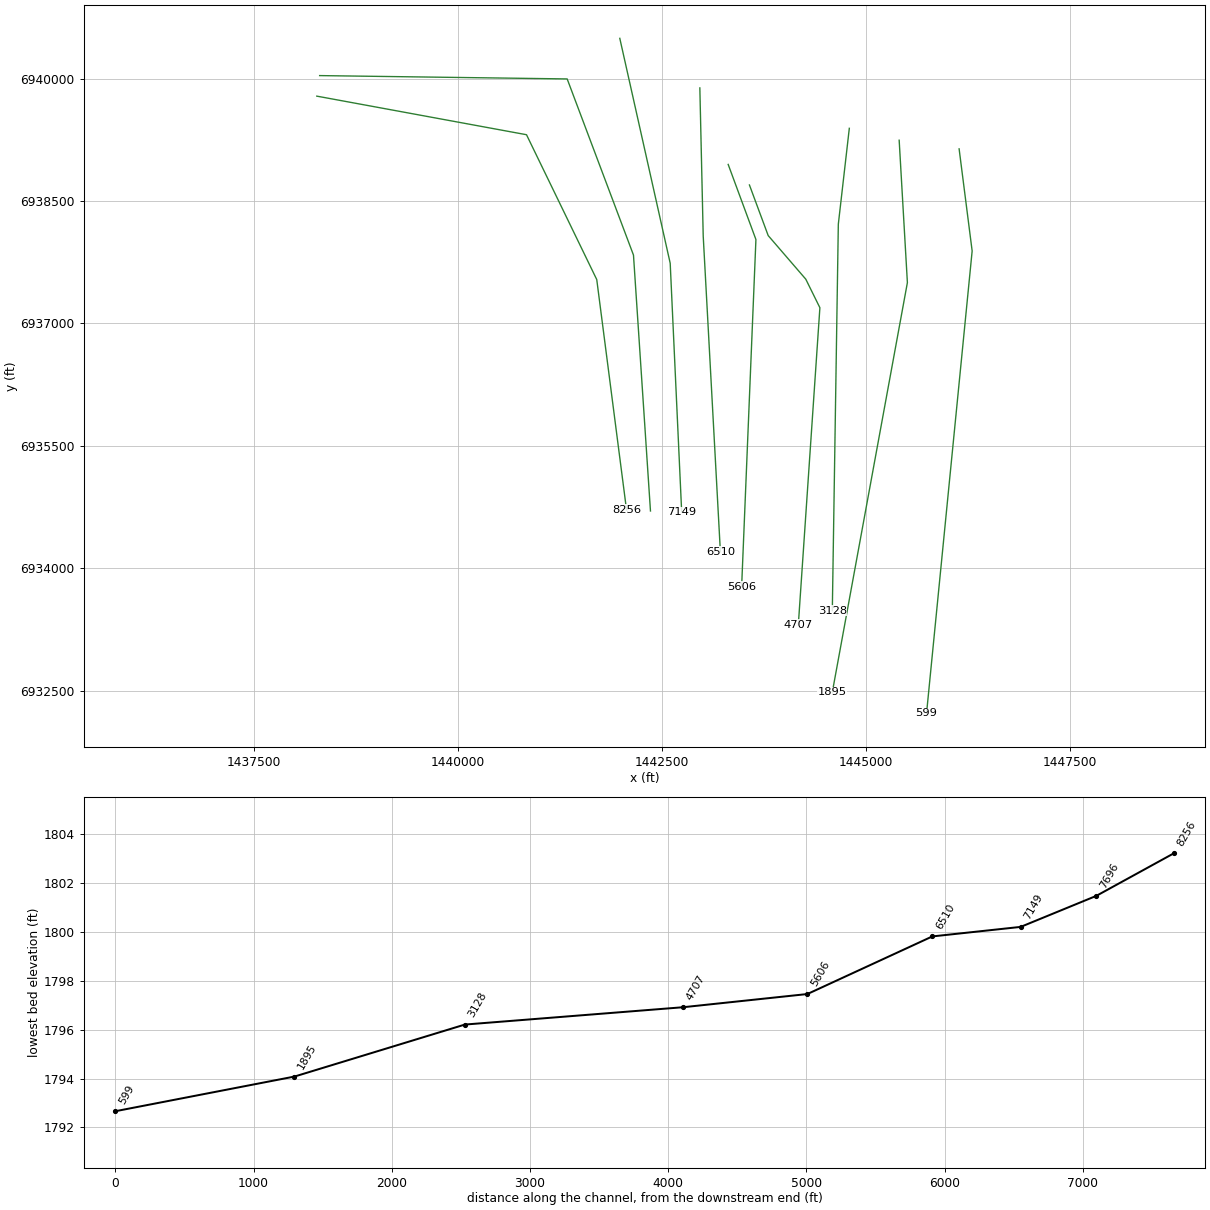
HEC-RAS study China Creek.prj: China Creek Base Level Engineering

--- China Creek.g01 (geometry) --- (continued)

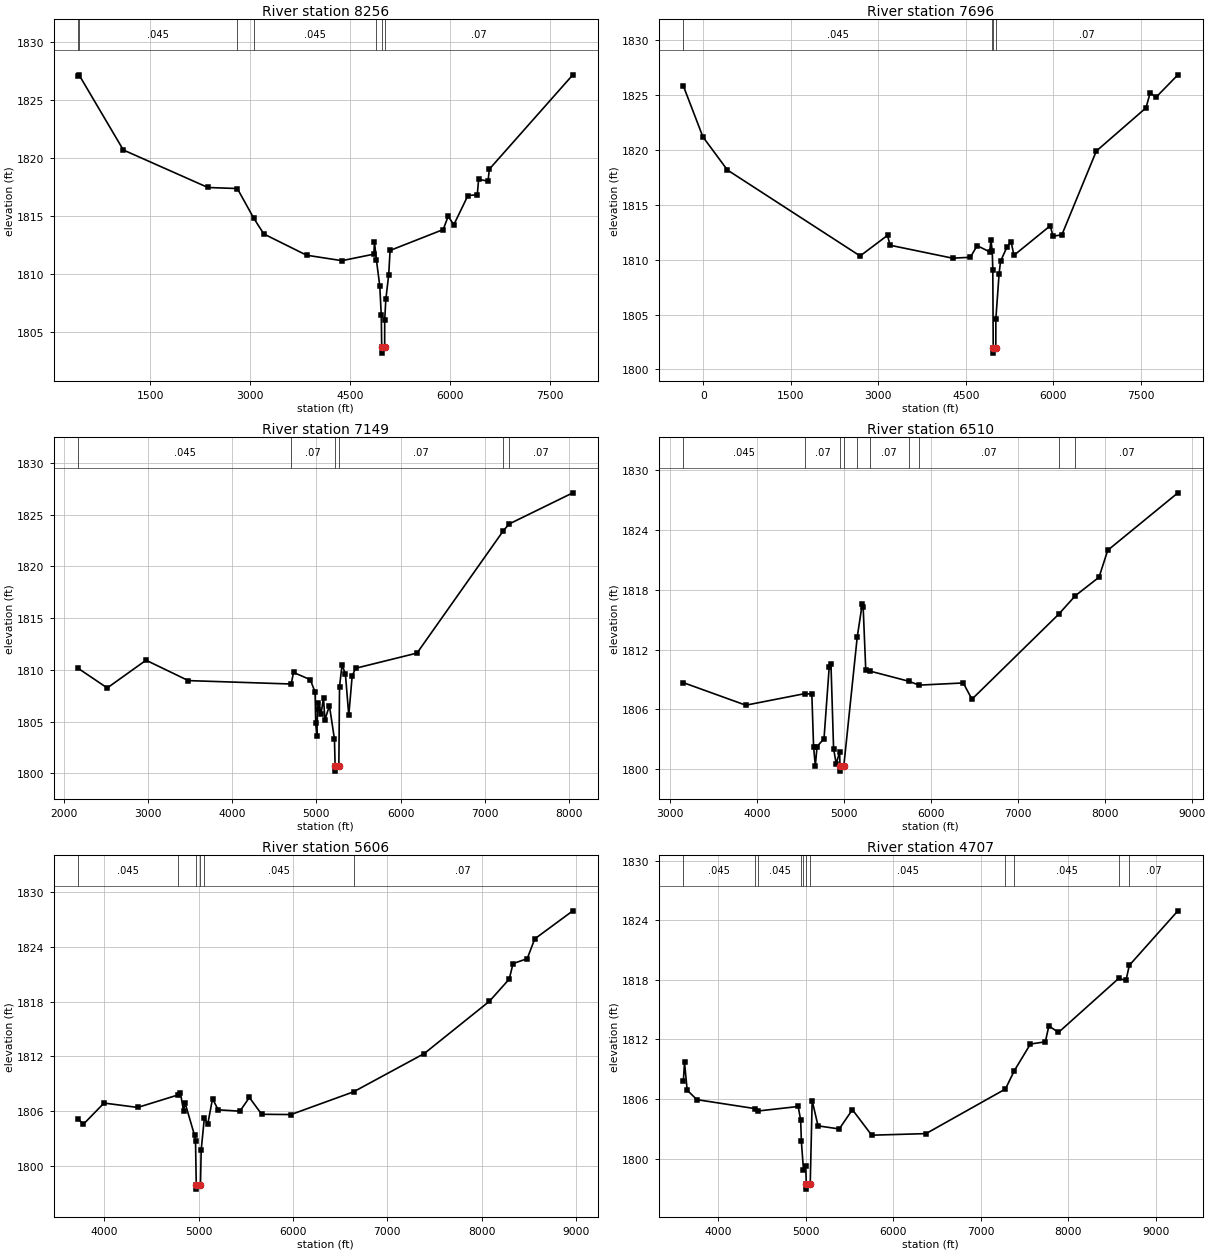
Type RM Length L Ch R = 1 ,8256    ,560,560,560
BEGIN DESCRIPTION:
China Creek 7.0
END DESCRIPTION:
XS GIS Cut Line= 4
      1438274.64      6939785.68      1440844.22      6939312.89
        1441705.        6937538.      1442070.13      6934713.92
#Sta/Elev= 30
   414.7 1827.07   427.7 1827.16  1091.9 1820.71  2362.9 1817.48  2805.3 1817.39
  3050.6 1814.85  3203.1 1813.48  3846.2 1811.65  4377.6 1811.18  4856.1 1811.74
  4866.7 1812.75  4896.4 1811.21  4946.4 1808.99  4968.9 1806.46    4975 1803.72
    4976 1803.22  5019.4 1803.72  5020.2 1806.06  5037.2 1807.86  5080.7 1809.98
  5100.9 1812.06  5899.7 1813.86    5974    1815  6058.8 1814.27  6270.5 1816.78
  6411.7 1816.86  6431.8 1818.19    6573 1818.02  6593.2 1819.06  7847.6 1827.18
#Mann= 7 ,-1 , 0
   414.7     .07       0   427.7    .045       0  2805.3     .05       0
  3050.6    .045       0  4896.4     .07       0    4975     .07       0
  5019.4     .07       0
Bank Sta=4975,5019.4
XS Rating Curve= 0 ,0
Exp/Cntr=0.3,0.1

Type RM Length L Ch R = 1 ,7696    ,547,547,547
BEGIN DESCRIPTION:
China Creek 6.0
END DESCRIPTION:
XS GIS Cut Line= 4
      1438309.38      6940037.41      1441342.53      6939996.52
        1442155.        6937838.      1442363.26       6934702.2
#Sta/Elev= 30
    -344 1825.85    -8.4  1821.2   411.7 1818.18  2688.2 1810.34    3158 1812.22
  3200.7 1811.32  4273.2 1810.14    4579 1810.22  4694.5 1811.28  4910.3 1810.72
  4931.7  1811.8    4954 1810.81  4963.7 1809.07  4970.9 1801.98  4971.9 1801.48
  5015.3 1801.98  5015.8 1804.58  5071.1 1808.68    5096 1809.85  5206.3 1811.15
  5276.4 1811.66  5326.5  1810.4  5947.9 1813.09    5998 1812.14  6148.3 1812.27
  6739.6 1819.91  7591.5 1823.85  7661.6 1825.21  7761.9 1824.81  8138.5 1826.86
#Mann= 4 ,-1 , 0
    -344    .045       0    4954     .07       0  4970.9     .07       0
  5015.3     .07       0
Bank Sta=4970.9,5015.3
XS Rating Curve= 0 ,0
Exp/Cntr=0.3,0.1

Type RM Length L Ch R = 1 ,7149    ,639,639,639
BEGIN DESCRIPTION:
China Creek 5.0
END DESCRIPTION:
XS GIS Cut Line= 3
      1441987.33      6940493.93        1442605.        6937738.
       1442745.7      6934688.34
#Sta/Elev= 30
  2170.5 1810.14  2514.8 1808.25  2975.9 1810.93  3478.1 1808.96    4701 1808.63
  4728.3 1809.75  4927.2 1809.05  4984.6 1807.86  4992.2 1804.88  5004.8 1803.61
  5014.8 1806.21  5024.8 1806.79  5054.9 1805.74  5084.9 1807.29  5101.6 1805.16
    5155 1806.54    5215  1803.3  5222.8 1800.71  5223.8 1800.21  5267.3 1800.71
  5275.1 1808.36  5305.1 1810.48  5345.2 1809.58  5385.2  1805.6  5425.3 1809.39
  5465.3 1810.15  6196.1 1811.62  7222.5 1823.45  7291.2  1824.1  8047.7 1827.11
#Mann= 6 ,-1 , 0
  2170.5    .045       0    4701     .07       0  5222.8     .07       0
  5267.3     .07       0  7222.5    .035       0  7291.2     .07       0
Bank Sta=5222.8,5267.3
XS Rating Curve= 0 ,0
Exp/Cntr=0.3,0.1

Type RM Length L Ch R = 1 ,6510    ,904,904,904
BEGIN DESCRIPTION:
Mapping XS 477c0f30
END DESCRIPTION:
XS GIS Cut Line= 3
      1442968.24      6939886.23      1443009.59      6938070.27
      1443219.91      6934201.71
#Sta/Elev= 30
  3150.5 1808.69  3868.9 1806.43    4555  1807.6  4629.1 1807.52  4649.1 1802.27
  4669.1 1800.33  4689.1 1802.28  4769.1 1803.08  4829.2 1810.29  4849.2 1810.54
  4879.2 1802.08  4909.2 1800.57  4949.2 1801.73  4952.1 1800.32  4953.1 1799.82
  4996.7 1800.32  5151.3 1813.26  5209.6 1816.62  5219.6 1816.27  5249.6 1809.93
  5292.9 1809.86  5744.6 1808.83  5862.4 1808.44  6371.3 1808.66  6471.4 1807.03
  7469.5 1815.55  7661.4 1817.41  7933.6 1819.26  8033.7 1821.96  8841.2 1827.72
#Mann= 10 ,-1 , 0
  3150.5    .045       0    4555     .07       0  4952.1     .07       0
  4996.7     .07       0  5151.3    .045       0  5292.9     .07       0
  5744.6    .035       0  5862.4     .07       0  7469.5    .035       0
  7661.4     .07       0
Bank Sta=4952.1,4996.7
XS Rating Curve= 0 ,0
Exp/Cntr=0.3,0.1

Type RM Length L Ch R = 1 ,5606    ,899,899,899
BEGIN DESCRIPTION:
Mapping XS 521d1bac
END DESCRIPTION:
XS GIS Cut Line= 3
      1443315.45      6938948.79      1443655.42      6938028.61
      1443480.39      6933775.19
#Sta/Elev= 30
  3726.6 1805.12  3780.7 1804.57  3999.4 1806.89  4356.4 1806.41  4783.6 1807.78
  4808.3    1808  4841.3 1806.06  4858.3 1806.89  4958.4 1803.34  4968.4 1802.77
  4976.1 1797.96  4977.1 1797.46  5020.8 1797.96  5028.5 1801.74  5061.6 1805.22
  5098.5 1804.61  5148.6 1807.36  5208.6 1806.15  5438.8    1806  5538.9  1807.5
    5669 1805.66  5979.3 1805.63  6642.1 1808.12  7390.5 1812.31    8081 1818.04
  8291.2 1820.47  8331.3 1822.17  8481.4 1822.71  8561.4 1824.88  8964.6 1827.95
#Mann= 6 ,-1 , 0
  3726.6    .045       0  4783.6     .07       0  4976.1     .07       0
  5020.8     .07       0  5061.6    .045       0  6642.1     .07       0
Bank Sta=4976.1,5020.8
XS Rating Curve= 0 ,0
Exp/Cntr=0.3,0.1

Type RM Length L Ch R = 1 ,4707    ,1579,1579,1579
BEGIN DESCRIPTION:
Mapping XS f2ab2951
END DESCRIPTION:
XS GIS Cut Line= 5
      1443575.87      6938697.04      1443805.83       6938076.9
      1444266.53      6937542.49      1444439.27      6937192.89
      1444174.83      6933306.41
#Sta/Elev= 30
  3600.5 1807.76  3613.9 1809.69  3644.3 1806.88  3755.2 1805.93  4424.4 1805.02
  4458.1 1804.79  4912.8 1805.24  4941.3 1803.89  4949.6 1801.72  4973.7 1798.82
  4999.1 1799.29  5005.9 1797.42  5006.9 1796.92  5050.6 1797.42  5072.9 1805.84
  5139.8 1803.29  5382.4 1802.98  5532.7 1804.92  5753.2 1802.35  6373.8 1802.51
  7281.8    1807    7383 1808.84  7567.4 1811.53  7737.8 1811.75  7777.9 1813.35
  7888.2  1812.7  8576.7 1818.14  8659.9 1817.93  8697.1 1819.45  9252.9 1824.94
#Mann= 11 ,-1 , 0
  3600.5    .045       0  4424.4     .07       0  4458.1    .045       0
  4949.6     .07       0  4973.7    .045       0  5005.9    .045       0
  5050.6    .045       0  7281.8     .07       0    7383    .045       0
  8576.7    .035       0  8697.1     .07       0
Bank Sta=5005.9,5050.6
XS Rating Curve= 0 ,0
Exp/Cntr=0.3,0.1

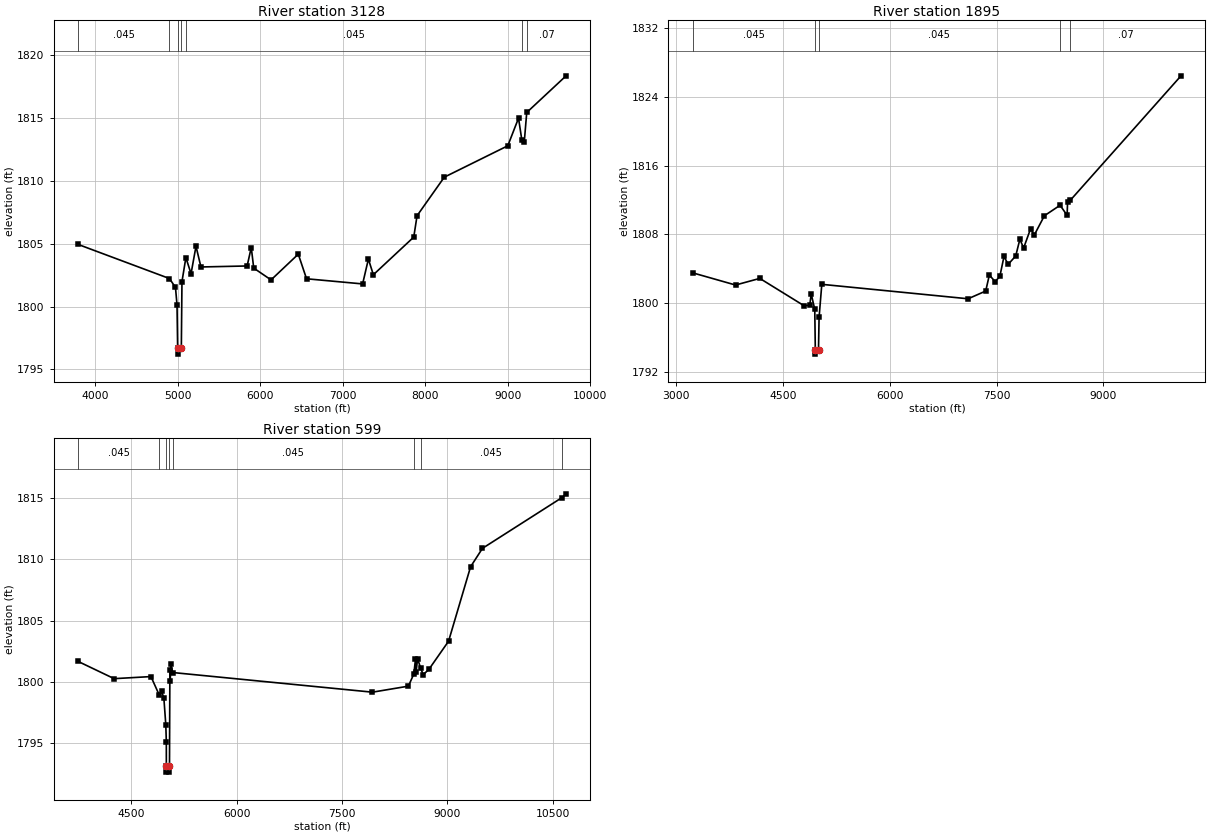
Type RM Length L Ch R = 1 ,3128    ,1233,1233,1233
BEGIN DESCRIPTION:
Mapping XS 4855cbf6
END DESCRIPTION:
XS GIS Cut Line= 3
      1444799.84      6939391.48      1444665.13      6938216.56
      1444591.53      6933481.55
#Sta/Elev= 30
  3788.8 1804.95  4897.9 1802.23  4971.4 1801.52    4990 1800.12  4997.6 1796.71
  4998.6 1796.21  5042.3 1796.71    5050 1801.98  5097.5  1803.9    5160 1802.61
    5220  1804.8    5280 1803.15  5840.1 1803.23  5890.1  1804.7  5920.1 1803.06
  6130.1 1802.12  6460.2 1804.17  6560.2 1802.21  7240.3  1801.8  7310.3 1803.78
  7370.3 1802.53  7860.3 1805.53  7900.3 1807.23  8230.4  1810.3  9000.5  1812.8
  9130.5    1815    9170 1813.29  9200.5 1813.13  9230.1 1815.45    9707 1818.37
#Mann= 7 ,-1 , 0
  3788.8    .045       0  4897.9     .07       0  4997.6     .07       0
  5042.3     .07       0  5097.5    .045       0    9170    .035       0
  9230.1     .07       0
Bank Sta=4997.6,5042.3
XS Rating Curve= 0 ,0
Exp/Cntr=0.3,0.1

Type RM Length L Ch R = 1 ,1895    ,1296,1296,1296
BEGIN DESCRIPTION:
Mapping XS 776bed95
END DESCRIPTION:
XS GIS Cut Line= 3
      1445410.73      6939245.51      1445511.48      6937500.41
      1444591.61      6932482.33
#Sta/Elev= 30
  3238.5 1803.53    3837 1802.12  4177.6 1802.89  4798.6 1799.71  4878.7 1799.78
  4898.8 1801.08  4948.8 1799.28  4956.5 1794.58  4957.5 1794.08  5001.2 1794.58
  5009.3 1798.35  5047.5  1802.2  7100.4 1800.52  7347.6 1801.42  7398.4 1803.28
  7479.8 1802.52  7545.9 1803.12  7604.1 1805.44  7662.8 1804.53  7768.6  1805.5
  7826.9 1807.44    7880 1806.43  7977.9 1808.68  8028.8 1807.93  8171.1 1810.18
  8391.2  1811.4  8490.1 1810.23  8496.4 1811.77  8532.6 1811.96 10088.2 1826.46
#Mann= 5 ,-1 , 0
  3238.5    .045       0  4956.5    .045       0  5001.2    .045       0
  8391.2    .035       0  8532.6     .07       0
Bank Sta=4956.5,5001.2
XS Rating Curve= 0 ,0
Exp/Cntr=0.3,0.1

Type RM Length L Ch R = 1 ,599     ,0,0,0
BEGIN DESCRIPTION:
China Creek 1.0
END DESCRIPTION:
XS GIS Cut Line= 3
      1446145.32      6939139.71        1446305.        6937888.
       1445746.1      6932222.15
#Sta/Elev= 30
  3737.7 1801.68  4253.7 1800.27  4777.8 1800.44  4897.7 1798.92    4929 1799.27
  4962.2 1798.67  4989.5 1796.52    4997 1795.13  4997.3 1793.16  4998.3 1792.66
  5041.1 1792.66  5042.1 1793.16  5047.6    1801  5052.7 1800.06  5059.8 1801.45
  5087.6 1800.77  7933.7 1799.17  8446.2 1799.66  8524.3 1800.66  8546.7 1801.84
  8556.7 1800.83  8576.8 1801.91  8619.5 1801.14  8657.2  1800.6  8737.6 1801.02
  9018.6 1803.32  9332.2 1809.38  9501.3 1810.88 10636.3 1815.02 10692.9 1815.32
#Mann= 8 ,-1 , 0
  3737.7    .045       0  4897.7     .07       0  4997.3     .07       0
  5042.1     .07       0  5087.6    .045       0  8524.3    .035       0
  8619.5    .045       0 10636.3    .035       0
Bank Sta=4997.3,5042.1
XS Rating Curve= 0 ,0
Exp/Cntr=0.3,0.1

Chan Stop Cuts=-1
Use User Specified Reach Order=0
Composite Channel Slope=5