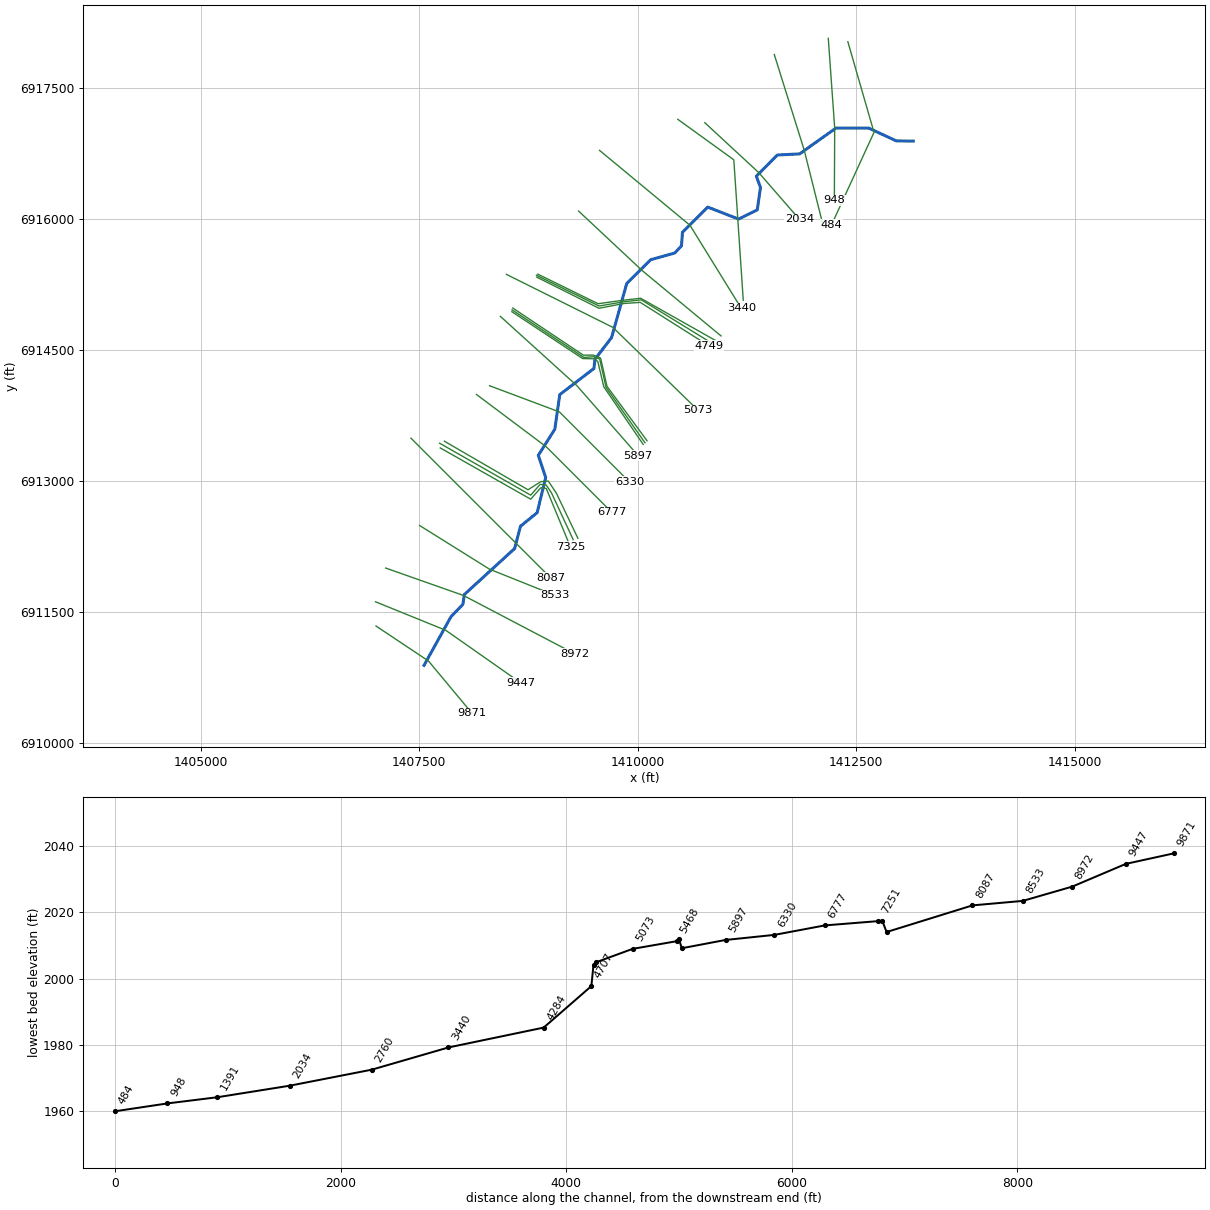
--- China Creek Trib1.prj (project) ---

Proj Title=China Creek Trib1 Base Level Engineering
Current Plan=p01
Default Exp/Contr=0.3,0.1
English Units
Geom File=g01
Flow File=f01
Plan File=p01
BEGIN DESCRIPTION:
China Creek Trib1
END DESCRIPTION:

--- China Creek Trib1.p01 (plan) ---

Plan Title=Multiple Run
Short Identifier=Multiple
Geom File=g01
Flow File=f01
Subcritical Flow
K Sum by GR= 0
Std Step Tol= 0.01
Critical Tol= 0.01
Num of Std Step Trials= 20
Max Error Tol= 0.3
Flow Tol Ratio= 0.001
Split Flow NTrial= 30
Split Flow Tol= 0.02
Split Flow Ratio= 0.02
Log Output Level= 0
Friction Slope Method= 1
Unsteady Friction Slope Method= 2
Unsteady Bridges Friction Slope Method= 1
Parabolic Critical Depth
Global Vel Dist=  1 , 1 , 1
Global Log Level= 0
CheckData=True
Encroach Param= -1, 0, 0, 0
BEGIN DESCRIPTION:
Multiple Run
END DESCRIPTION:

--- China Creek Trib1.f01 (steady flow) ---

Flow Title=Multiple
Number of Profiles=7
Profile Names=10-year,25-year,50-year,1pct_min,100-year,1pct_plu,500-year
River Rch & RM= China Creek Trib,Reach-1,9871
     221     306     376     230     459     917     693
River Rch & RM= China Creek Trib,Reach-1,9447
     344     489     612     380     758    1513    1180
River Rch & RM= China Creek Trib,Reach-1,5509
     447     645     816     512    1021    2038    1623
River Rch & RM= China Creek Trib,Reach-1,2034
     490     712     902     567    1132    2258    1806
Boundary for River Rch & Prof#=China Creek Trib,Reach-1,1
Up Type=0
Dn Type=3
Dn Slope=0.005
Boundary for River Rch & Prof#=China Creek Trib,Reach-1,2
Up Type=0
Dn Type=3
Dn Slope=0.005
Boundary for River Rch & Prof#=China Creek Trib,Reach-1,3
Up Type=0
Dn Type=3
Dn Slope=0.005
Boundary for River Rch & Prof#=China Creek Trib,Reach-1,4
Up Type=0
Dn Type=3
Dn Slope=0.005
Boundary for River Rch & Prof#=China Creek Trib,Reach-1,5
Up Type=0
Dn Type=3
Dn Slope=0.005
Boundary for River Rch & Prof#=China Creek Trib,Reach-1,6
Up Type=0
Dn Type=3
Dn Slope=0.005
Boundary for River Rch & Prof#=China Creek Trib,Reach-1,7
Up Type=0
Dn Type=3
Dn Slope=0.005

--- China Creek Trib1.g01 (geometry) ---

Geom Title=Existing Conditions

River Reach=China Creek Trib,Reach-1
Reach XY= 30
      1407555.00      6910888.00      1407862.86      6911444.17
      1407999.48      6911585.57      1408015.52      6911697.79
      1408591.63      6912224.68      1408658.51      6912479.52
      1408849.48      6912635.57      1408947.44      6913038.00
      1408862.81      6913291.41      1409051.24      6913589.56
      1409108.53      6913986.55      1409499.48      6914285.57
      1409510.54      6914390.42      1409701.38      6914639.50
      1409874.60      6915258.16      1410148.83      6915530.14
      1410425.20      6915607.61      1410501.46      6915689.46
      1410512.82      6915844.19      1410802.57      6916132.60
      1411155.08      6915995.30      1411368.73      6916101.23
      1411405.35      6916358.15      1411358.13      6916486.37
      1411598.33      6916728.70      1411853.44      6916741.76
      1412270.16      6917037.61      1412644.50      6917036.80
      1412960.93      6916890.25      1413155.00      6916888.00

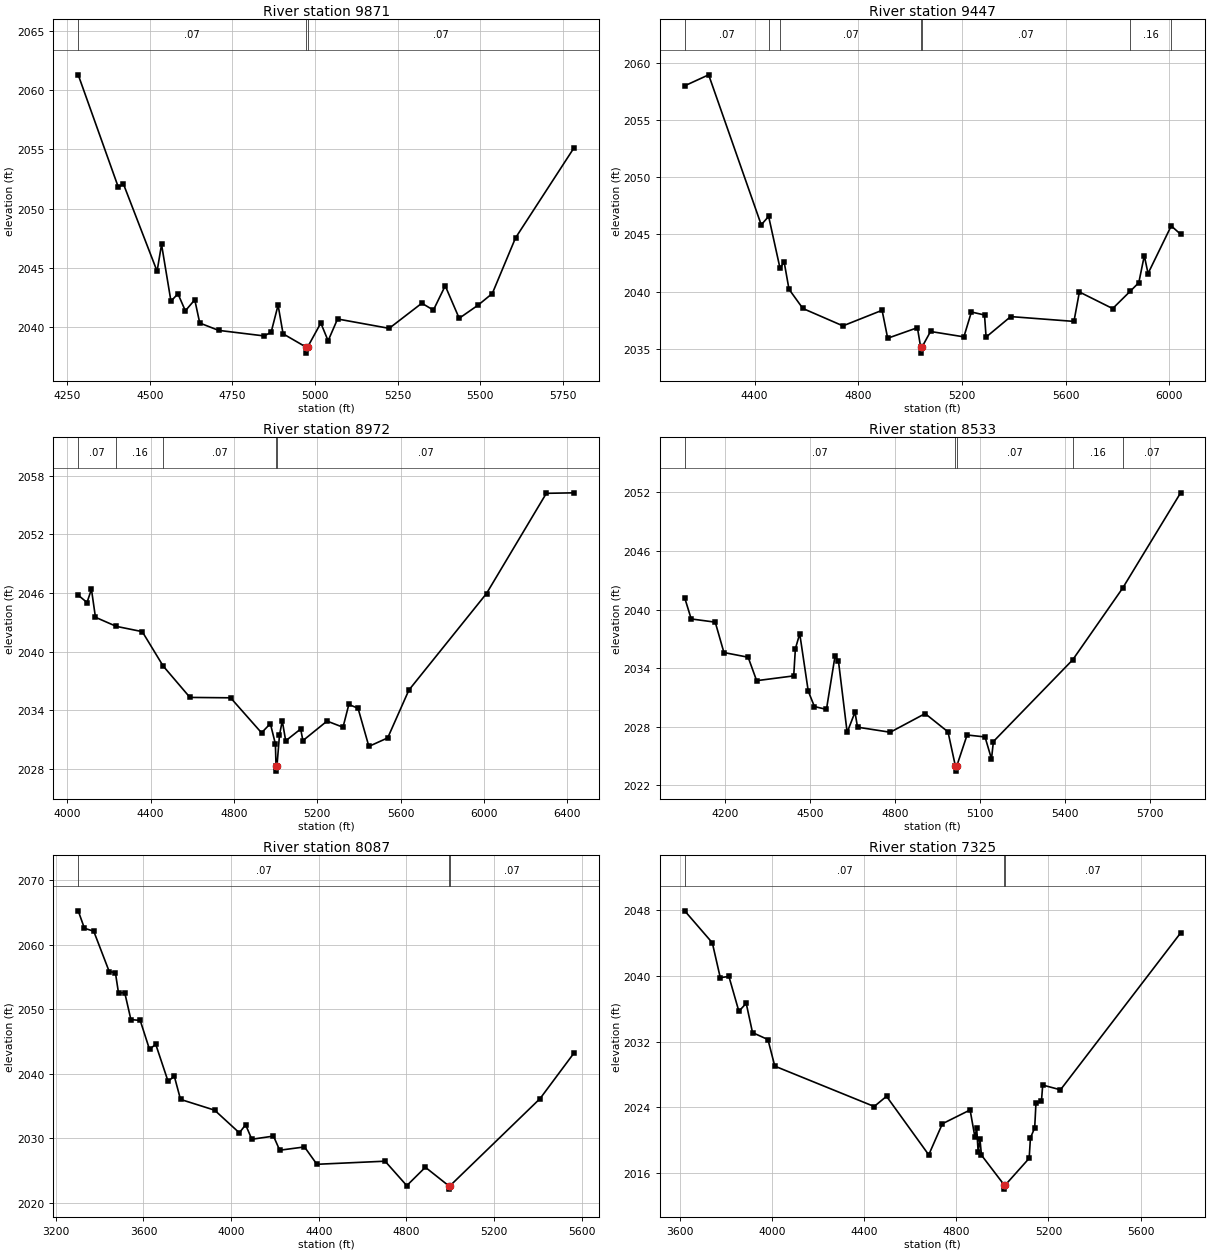
Type RM Length L Ch R = 1,9871,424,424,424
BEGIN DESCRIPTION:
China Creek Trib1 22.0
END DESCRIPTION:
XS GIS Cut Line= 3
      1407005.00      6911338.00      1407605.00      6910938.00
      1408104.98      6910338.03
#Sta/Elev= 30
  4282.7 2061.28  4404.4 2051.78  4419.4 2052.09  4521.6 2044.71  4535.1 2046.97
  4563.6 2042.18  4584.7 2042.81  4607.2 2041.37  4635.7 2042.30  4650.8 2040.34
  4707.9 2039.72  4846.1 2039.25  4867.1 2039.57  4888.1 2041.85  4903.2 2039.43
  4973.3 2038.30  4973.5 2037.80  4977.3 2038.30  5017.5 2040.34  5039.6 2038.84
  5068.2 2040.68  5224.5 2039.89  5323.4 2042.01  5358.5 2041.43  5394.3 2043.48
  5436.6 2040.74  5493.9 2041.85  5536.9 2042.83  5607.2 2047.52  5784.8 2055.14
#Mann=3,-1,0
  4282.7    0.07       0  4973.3    0.07       0  4977.3    0.07       0
Bank Sta=4973.3,4977.3
Exp/Cntr=0.3,0.1

Type RM Length L Ch R = 1,9447,475,475,475
BEGIN DESCRIPTION:
China Creek Trib1 21.0
END DESCRIPTION:
XS GIS Cut Line= 3
      1406999.29      6911615.37      1407805.00      6911288.00
      1408659.71      6910688.63
#Sta/Elev= 30
  4130.3 2057.98  4222.8 2058.94  4425.7 2045.84  4454.2 2046.58  4498.1 2042.06
  4514.2 2042.59  4532.8 2040.22  4586.3 2038.54  4740.9 2037.02  4892.0 2038.38
  4913.6 2035.94  5028.3 2036.86  5041.0 2035.14  5041.3 2034.64  5045.3 2035.14
  5078.9 2036.53  5207.6 2036.06  5236.6 2038.23  5287.2 2037.97  5293.3 2036.04
  5388.3 2037.83  5632.3 2037.41  5653.3 2039.98  5781.7 2038.53  5849.7 2040.05
  5882.5 2040.79  5903.8 2043.15  5918.2 2041.59  6007.7 2045.75  6043.9 2045.02
#Mann=7,-1,0
  4130.3    0.07       0  4454.2    0.16       0  4498.1    0.07       0
  5041.0    0.07       0  5045.3    0.07       0  5849.7    0.16       0
  6007.7    0.07       0
Bank Sta=5041,5045.3
Exp/Cntr=0.3,0.1

Type RM Length L Ch R = 1,8972,439,439,439
BEGIN DESCRIPTION:
China Creek Trib1 20.0
END DESCRIPTION:
XS GIS Cut Line= 3
      1407115.08      6912001.56      1408005.00      6911688.00
      1409277.61      6911020.70
#Sta/Elev= 30
  4052.5 2045.78  4094.8 2045.03  4116.0 2046.39  4135.2 2043.52  4235.2 2042.59
  4359.9 2042.05  4460.0 2038.54  4588.8 2035.32  4784.0 2035.28  4932.4 2031.70
  4974.8 2032.64  4998.9 2030.57  5002.1 2028.28  5002.4 2027.78  5006.4 2028.28
  5018.6 2031.47  5032.0 2032.92  5048.4 2030.88  5120.3 2032.09  5131.0 2030.90
  5246.9 2032.90  5323.5 2032.27  5351.5 2034.60  5395.7 2034.21  5447.7 2030.31
  5538.0 2031.18  5639.7 2036.07  6012.3 2045.95  6299.5 2056.20  6433.0 2056.25
#Mann=5,-1,0
  4052.5    0.07       0  4235.2    0.16       0  4460.0    0.07       0
  5002.1    0.07       0  5006.4    0.07       0
Bank Sta=5002.1,5006.4
Exp/Cntr=0.3,0.1

Type RM Length L Ch R = 1,8533,446,446,446
BEGIN DESCRIPTION:
China Creek Trib1 19.0
END DESCRIPTION:
XS GIS Cut Line= 3
      1407505.00      6912488.00      1408305.00      6911988.00
      1409055.03      6911687.99
#Sta/Elev= 30
  4057.0 2041.21  4080.0 2039.04  4164.9 2038.71  4195.6 2035.60  4281.1 2035.12
  4311.1 2032.72  4442.0 2033.21  4447.9 2035.99  4463.3 2037.53  4493.3 2031.65
  4515.1 2030.07  4557.6 2029.78  4587.7 2035.20  4600.0 2034.73  4630.7 2027.42
  4658.4 2029.50  4667.3 2027.96  4782.8 2027.44  4906.1 2029.35  4986.8 2027.48
  5013.0 2023.96  5013.3 2023.46  5017.5 2023.96  5054.2 2027.16  5117.5 2026.96
  5140.4 2024.71  5147.1 2026.49  5427.0 2034.85  5603.2 2042.18  5808.2 2051.95
#Mann=5,-1,0
  4057.0    0.07       0  5013.0    0.07       0  5017.5    0.07       0
  5427.0    0.16       0  5603.2    0.07       0
Bank Sta=5013,5017.5
Exp/Cntr=0.3,0.1

Type RM Length L Ch R = 1,8087,762,762,762
BEGIN DESCRIPTION:
China Creek Trib1 18.0
END DESCRIPTION:
XS GIS Cut Line= 3
      1407404.98      6913488.02      1408605.00      6912288.00
      1409005.02      6911887.98
#Sta/Elev= 30
  3302.4 2065.25  3330.7 2062.54  3373.1 2062.10  3443.8 2055.84  3472.1 2055.65
  3486.3 2052.51  3514.6 2052.57  3542.8 2048.39  3585.3 2048.26  3627.7 2043.77
  3656.0 2044.57  3712.5 2038.81  3740.8 2039.62  3769.1 2036.02  3924.7 2034.35
  4037.8 2030.83  4066.1 2032.10  4094.4 2029.84  4193.4 2030.33  4221.7 2028.14
  4334.8 2028.65  4391.4 2025.96  4702.5 2026.44  4801.5 2022.65  4886.3 2025.50
  4993.6 2022.61  4994.0 2022.11  4998.2 2022.61  5409.6 2036.14  5565.2 2043.24
#Mann=3,-1,0
  3302.4    0.07       0  4993.6    0.07       0  4998.2    0.07       0
Bank Sta=4993.6,4998.2
Exp/Cntr=0.3,0.1

Type RM Length L Ch R = 1,7325,38,38,38
BEGIN DESCRIPTION:
Mapping XS 6bce5885
END DESCRIPTION:
XS GIS Cut Line= 5
      1407740.70      6913376.28      1408775.60      6912789.32
      1408891.45      6912920.61      1408953.24      6912912.89
      1409230.20      6912243.56
#Sta/Elev= 30
  3621.7 2047.91  3741.6 2044.02  3776.1 2039.78  3813.6 2039.93  3856.8 2035.69
  3888.6 2036.66  3916.0 2033.10  3983.0 2032.25  4012.6 2029.02  4443.9 2024.11
  4497.3 2025.35  4680.5 2018.23  4739.6 2022.01  4859.9 2023.69  4880.8 2020.39
  4888.4 2021.47  4895.0 2018.54  4902.6 2020.16  4909.3 2018.19  5008.0 2014.56
  5008.4 2014.06  5012.6 2014.56  5116.2 2017.81  5121.7 2020.30  5140.1 2021.50
  5145.6 2024.51  5169.4 2024.73  5174.9 2026.72  5252.0 2026.14  5773.2 2045.22
#Mann=3,-1,0
  3621.7    0.07       0  5008.0    0.07       0  5012.6    0.07       0
Bank Sta=5008,5012.6
Exp/Cntr=0.3,0.1

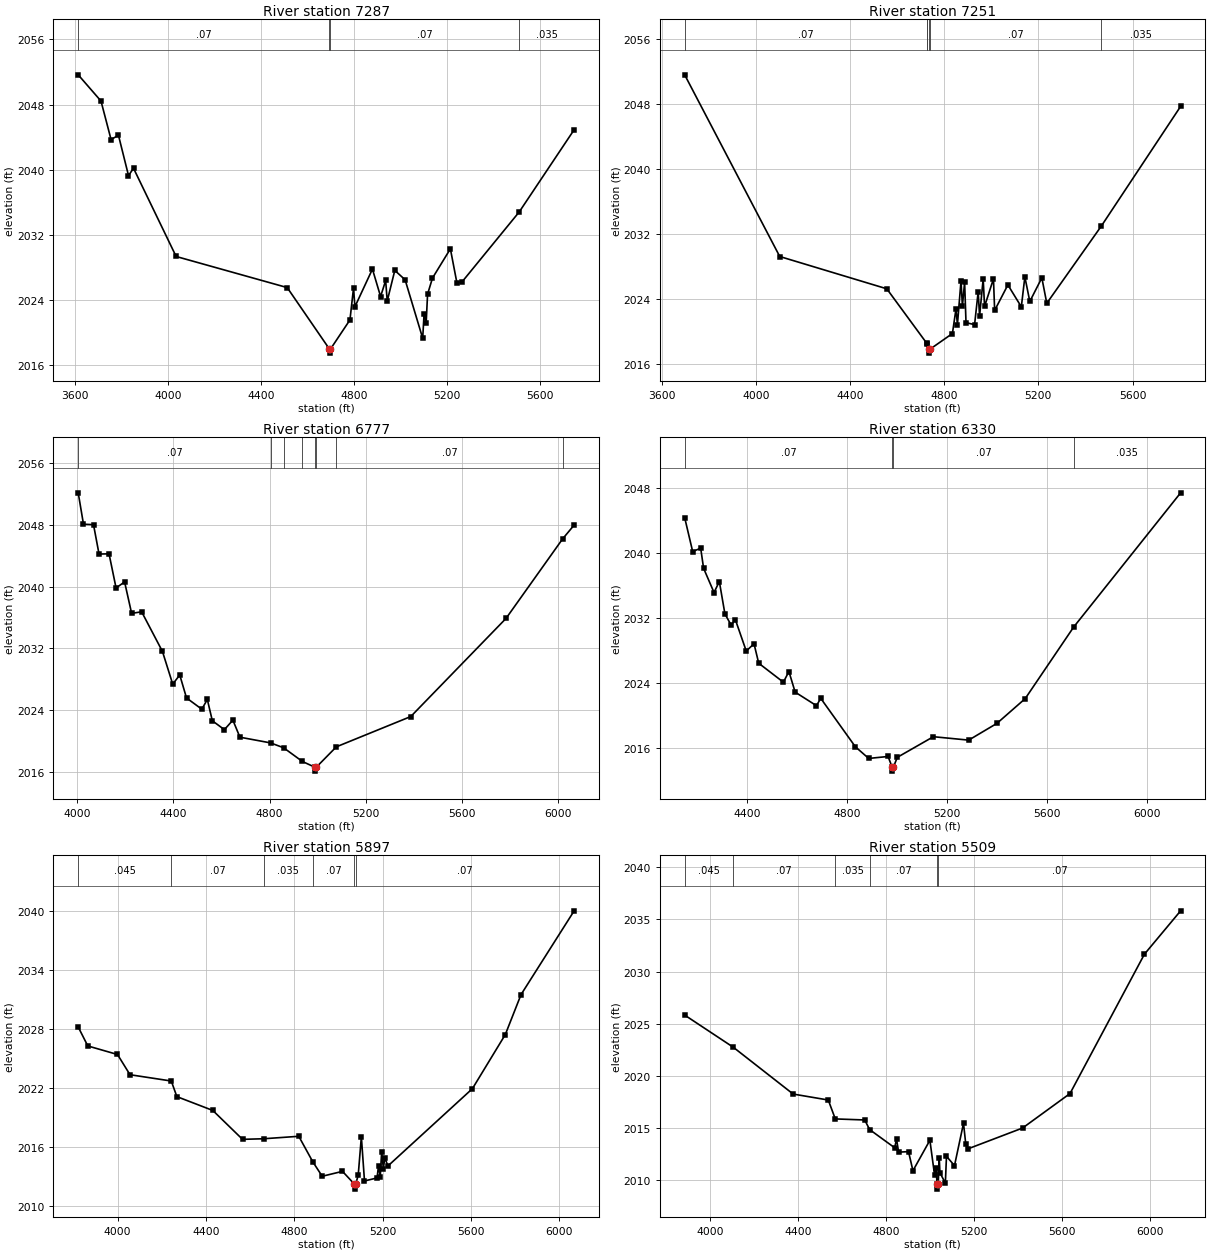
Type RM Length L Ch R = 1,7287,36,36,36
BEGIN DESCRIPTION:
Mapping XS e9718137
END DESCRIPTION:
XS GIS Cut Line= 6
      1407732.95      6913430.35      1408775.60      6912835.65
      1408883.73      6912959.23      1408953.24      6912951.50
      1409015.02      6912858.82      1409262.15      6912325.96
#Sta/Elev= 30
  3614.3 2051.65  3712.3 2048.43  3755.6 2043.70  3787.4 2044.23  3830.6 2039.28
  3852.3 2040.17  4035.5 2029.34  4513.3 2025.52  4694.9 2017.97  4695.3 2017.47
  4699.5 2017.97  4783.2 2021.55  4798.6 2025.47  4804.5 2023.16  4879.9 2027.79
  4915.0 2024.42  4936.8 2026.39  4943.5 2023.87  4976.1 2027.63  5020.4 2026.48
  5096.1 2019.29  5102.1 2022.31  5111.1 2021.23  5117.1 2024.71  5138.2 2026.69
  5215.2 2030.28  5243.6 2026.05  5266.5 2026.26  5511.5 2034.82  5747.6 2044.91
#Mann=4,-1,0
  3614.3    0.07       0  4694.9    0.07       0  4699.5    0.07       0
  5511.5   0.035       0
Bank Sta=4694.9,4699.5
Exp/Cntr=0.3,0.1

Type RM Length L Ch R = 1,7251,474,474,474
BEGIN DESCRIPTION:
Mapping XS f180415e
END DESCRIPTION:
XS GIS Cut Line= 6
      1407787.06      6913453.50      1408744.71      6912897.44
      1408891.45      6912990.12      1408976.41      6912997.84
      1409069.08      6912858.82      1409315.85      6912342.16
#Sta/Elev= 30
  3698.4 2051.58  4102.1 2029.24  4556.6 2025.27  4725.3 2018.61  4726.8 2018.51
  4736.4 2017.86  4736.8 2017.36  4741.0 2017.86  4835.3 2019.77  4850.6 2022.82
  4856.5 2020.84  4871.8 2026.26  4877.7 2023.14  4887.1 2026.10  4893.0 2021.11
  4929.4 2020.86  4944.7 2024.92  4950.6 2021.91  4965.9 2026.49  4971.8 2023.10
  5009.6 2026.50  5014.6 2022.61  5070.8 2025.75  5127.9 2023.05  5142.9 2026.74
  5163.9 2023.71  5215.0 2026.62  5236.0 2023.49  5468.0 2033.00  5804.3 2047.70
#Mann=6,-1,0
  3698.4    0.07       0  4725.3   0.035       0  4726.8    0.07       0
  4736.4    0.07       0  4741.0    0.07       0  5468.0   0.035       0
Bank Sta=4736.4,4741
Exp/Cntr=0.3,0.1

Type RM Length L Ch R = 1,6777,447,447,447
BEGIN DESCRIPTION:
China Creek Trib1 15.0
END DESCRIPTION:
XS GIS Cut Line= 3
      1408154.98      6913988.01      1408955.00      6913388.00
      1409705.01      6912637.99
#Sta/Elev= 30
  4004.5 2052.15  4026.4 2048.08  4068.1 2048.02  4091.0 2044.21  4132.6 2044.24
  4161.8 2039.81  4197.2 2040.60  4226.4 2036.52  4268.1 2036.72  4354.5 2031.58
  4397.2 2027.34  4426.4 2028.53  4454.5 2025.55  4518.1 2024.09  4541.0 2025.35
  4561.8 2022.59  4611.8 2021.44  4647.2 2022.67  4676.4 2020.46  4803.9 2019.72
  4857.9 2019.09  4936.1 2017.31  4988.5 2016.56  4988.9 2016.06  4993.5 2016.56
  5077.0 2019.21  5386.4 2023.14  5782.3 2035.87  6017.6 2046.19  6065.2 2047.97
#Mann=8,-1,0
  4004.5    0.07       0  4803.9   0.035       0  4857.9    0.07       0
  4936.1   0.035       0  4988.5   0.035       0  4993.5   0.035       0
  5077.0    0.07       0  6017.6   0.035       0
Bank Sta=4988.5,4993.5
Exp/Cntr=0.3,0.1

Type RM Length L Ch R = 1,6330,433,433,433
BEGIN DESCRIPTION:
China Creek Trib1 14.0
END DESCRIPTION:
XS GIS Cut Line= 3
      1408305.00      6914088.00      1409105.00      6913788.00
      1409905.02      6912987.98
#Sta/Elev= 30
  4149.7 2044.35  4181.7 2040.18  4213.8 2040.60  4225.4 2038.13  4267.2 2035.15
  4288.5 2036.50  4310.8 2032.52  4335.7 2031.15  4352.6 2031.82  4396.2 2027.96
  4427.4 2028.85  4446.1 2026.46  4544.9 2024.13  4567.1 2025.44  4592.0 2022.91
  4677.5 2021.24  4694.4 2022.15  4833.2 2016.19  4886.6 2014.76  4964.1 2015.00
  4980.2 2013.70  4980.6 2013.20  4985.3 2013.70  5001.4 2014.90  5145.5 2017.43
  5286.9 2017.01  5400.1 2019.07  5513.2 2022.11  5707.1 2030.90  6135.5 2047.40
#Mann=4,-1,0
  4149.7    0.07       0  4980.2    0.07       0  4985.3    0.07       0
  5707.1   0.035       0
Bank Sta=4980.2,4985.3
Exp/Cntr=0.3,0.1

Type RM Length L Ch R = 1,5897,388,388,388
BEGIN DESCRIPTION:
China Creek Trib1 13.0
END DESCRIPTION:
XS GIS Cut Line= 3
      1408428.07      6914882.30      1409305.00      6914088.00
      1410005.00      6913288.00
#Sta/Elev= 30
  3821.3 2028.18  3864.7 2026.25  3999.2 2025.38  4055.9 2023.32  4242.8 2022.68
  4268.1 2021.09  4431.0 2019.68  4565.5 2016.74  4661.3 2016.80  4820.3 2017.05
  4883.8 2014.45  4926.4 2012.98  5018.2 2013.48  5072.6 2012.17  5073.0 2011.67
  5077.7 2012.17  5089.4 2013.07  5103.7 2017.00  5117.9 2012.50  5174.8 2012.81
  5181.5 2014.07  5189.1 2012.91  5195.7 2015.49  5203.3 2013.77  5210.0 2014.85
  5224.2 2014.03  5606.7 2021.90  5755.7 2027.41  5826.9 2031.48  6067.5 2040.01
#Mann=6,-1,0
  3821.3   0.045       0  4242.8    0.07       0  4661.3   0.035       0
  4883.8    0.07       0  5072.6    0.07       0  5077.7    0.07       0
Bank Sta=5072.6,5077.7
Exp/Cntr=0.3,0.1

Type RM Length L Ch R = 1,5509,25,25,25
BEGIN DESCRIPTION:
Mapping XS 6522d94a
END DESCRIPTION:
XS GIS Cut Line= 6
      1408560.16      6914935.56      1409370.02      6914399.12
      1409508.04      6914396.52      1409544.50      6914362.67
      1409612.20      6914076.21      1410062.71      6913417.37
#Sta/Elev= 30
  3885.1 2025.83  4105.9 2022.75  4377.7 2018.27  4537.1 2017.70  4568.9 2015.89
  4702.6 2015.79  4724.9 2014.87  4838.5 2013.13  4847.0 2013.95  4856.5 2012.71
  4901.5 2012.76  4921.5 2010.93  4998.5 2013.85  5019.5 2010.55  5026.8 2011.19
  5030.9 2009.67  5031.4 2009.17  5036.3 2009.67  5041.0 2012.13  5044.1 2010.74
  5068.7 2009.74  5073.8 2012.31  5110.2 2011.42  5151.1 2015.47  5161.4 2013.48
  5173.0 2013.04  5419.4 2015.02  5634.7 2018.32  5972.6 2031.66  6136.9 2035.81
#Mann=6,-1,0
  3885.1   0.045       0  4105.9    0.07       0  4568.9   0.035       0
  4724.9    0.07       0  5030.9    0.07       0  5036.3    0.07       0
Bank Sta=5030.9,5036.3
Exp/Cntr=0.3,0.1

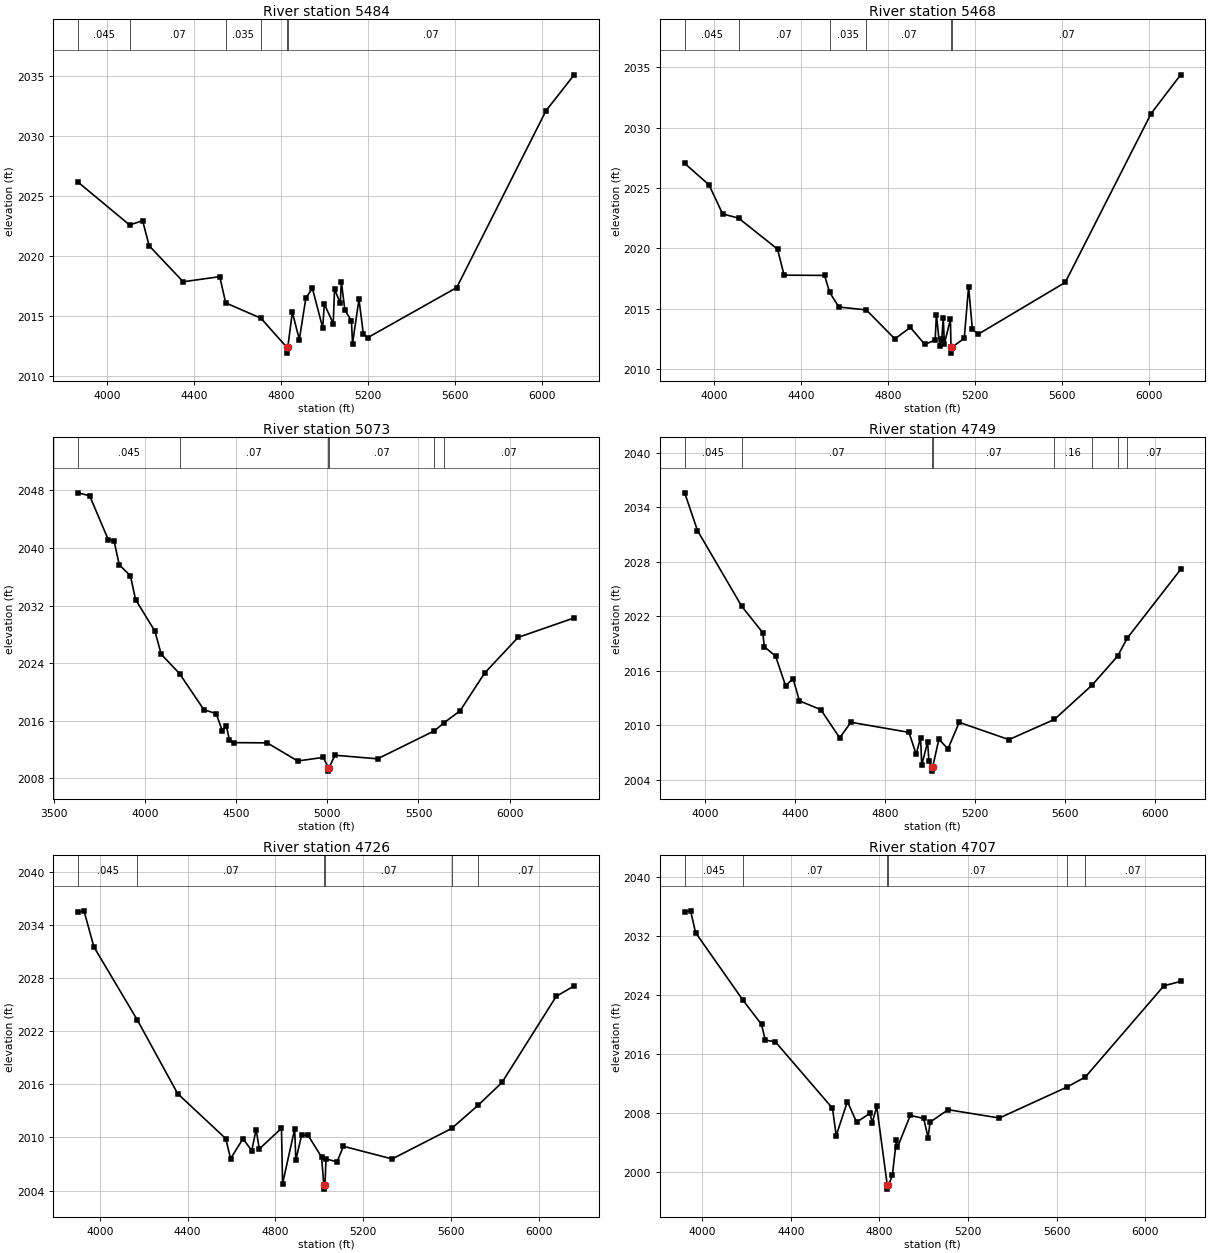
Type RM Length L Ch R = 1,5484,16,16,16
BEGIN DESCRIPTION:
Mapping XS 72d1a662
END DESCRIPTION:
XS GIS Cut Line= 6
      1408562.69      6914956.44      1409383.04      6914412.15
      1409500.23      6914419.96      1409565.33      6914393.92
      1409638.25      6914068.40      1410083.54      6913435.60
#Sta/Elev= 30
  3868.4 2026.14  4104.5 2022.58  4164.6 2022.93  4194.7 2020.84  4351.2 2017.84
  4519.2 2018.27  4546.4 2016.08  4708.5 2014.80  4826.6 2012.39  4827.0 2011.89
  4832.0 2012.39  4852.9 2015.30  4884.9 2013.02  4915.0 2016.49  4945.1 2017.29
  4992.5 2014.00  4999.9 2015.98  5040.9 2014.36  5046.9 2017.24  5073.1 2016.04
  5078.1 2017.85  5094.3 2015.49  5124.5 2014.59  5129.6 2012.68  5159.1 2016.38
  5179.7 2013.45  5200.3 2013.19  5608.7 2017.36  6018.9 2032.10  6148.5 2035.10
#Mann=6,-1,0
  3868.4   0.045       0  4104.5    0.07       0  4546.4   0.035       0
  4708.5    0.07       0  4826.6    0.07       0  4832.0    0.07       0
Bank Sta=4826.6,4832
Exp/Cntr=0.3,0.1

Type RM Length L Ch R = 1,5468,395,395,395
BEGIN DESCRIPTION:
Mapping XS 51c45858
END DESCRIPTION:
XS GIS Cut Line= 6
      1408570.54      6914977.25      1409377.83      6914438.19
      1409495.02      6914438.19      1409575.75      6914404.33
      1409648.66      6914081.42      1410107.00      6913459.01
#Sta/Elev= 30
  3864.7 2027.04  3976.3 2025.27  4039.4 2022.85  4112.3 2022.51  4291.7 2019.94
  4321.8 2017.78  4508.0 2017.76  4531.2 2016.36  4574.1 2015.14  4700.0 2014.90
  4831.1 2012.50  4902.6 2013.45  4969.2 2012.04  5016.7 2012.41  5022.4 2014.52
  5037.3 2011.93  5047.2 2012.47  5053.9 2014.26  5059.1 2012.10  5086.9 2014.12
  5089.4 2011.82  5089.8 2011.32  5094.8 2011.82  5150.4 2012.54  5170.5 2016.82
  5187.8 2013.29  5214.7 2012.89  5614.9 2017.18  6009.8 2031.17  6145.5 2034.38
#Mann=6,-1,0
  3864.7   0.045       0  4112.3    0.07       0  4531.2   0.035       0
  4700.0    0.07       0  5089.4    0.07       0  5094.8    0.07       0
Bank Sta=5089.4,5094.8
Exp/Cntr=0.3,0.1

Type RM Length L Ch R = 1,5073,324,324,324
BEGIN DESCRIPTION:
Mapping XS 7aba1aee
END DESCRIPTION:
XS GIS Cut Line= 3
      1408497.59      6915362.68      1409716.37      6914755.90
      1410690.13      6913808.17
#Sta/Elev= 30
  3633.5 2047.67  3696.1 2047.26  3798.2 2041.17  3830.4 2040.96  3858.4 2037.68
  3920.0 2036.12  3947.9 2032.84  4054.3 2028.43  4088.6 2025.23  4189.2 2022.54
  4323.0 2017.51  4390.2 2016.98  4423.7 2014.60  4446.1 2015.24  4462.9 2013.34
  4485.3 2012.94  4670.0 2012.91  4837.1 2010.39  4977.9 2010.89  5004.1 2009.48
  5004.5 2008.98  5009.5 2009.48  5042.0 2011.19  5275.3 2010.69  5587.2 2014.58
  5638.9 2015.68  5728.0 2017.36  5862.3 2022.60  6046.2 2027.57  6353.8 2030.28
#Mann=6,-1,0
  3633.5   0.045       0  4189.2    0.07       0  5004.1    0.07       0
  5009.5    0.07       0  5587.2    0.16       0  5638.9    0.07       0
Bank Sta=5004.1,5009.5
Exp/Cntr=0.3,0.1

Type RM Length L Ch R = 1,4749,23,23,23
BEGIN DESCRIPTION:
Mapping XS 812f6f42
END DESCRIPTION:
XS GIS Cut Line= 5
      1408844.00      6915331.40      1409557.52      6914974.65
      1409841.37      6915029.33      1410028.87      6915042.35
      1410815.32      6914544.96
#Sta/Elev= 30
  3909.0 2035.59  3966.0 2031.43  4162.6 2023.10  4256.7 2020.17  4262.8 2018.64
  4313.1 2017.61  4357.8 2014.34  4390.9 2015.13  4419.3 2012.68  4514.3 2011.71
  4598.2 2008.61  4648.5 2010.32  4906.1 2009.21  4938.4 2006.81  4958.0 2008.64
  4963.1 2005.61  4989.3 2008.15  4995.1 2006.06  5006.8 2005.44  5007.2 2004.94
  5012.2 2005.44  5039.5 2008.47  5079.6 2007.38  5129.8 2010.31  5350.8 2008.41
  5552.9 2010.63  5720.0 2014.40  5834.4 2017.61  5876.7 2019.58  6114.3 2027.15
#Mann=8,-1,0
  3909.0   0.045       0  4162.6    0.07       0  5006.8    0.07       0
  5012.2    0.07       0  5552.9    0.16       0  5720.0    0.07       0
  5834.4    0.16       0  5876.7    0.07       0
Bank Sta=5006.8,5012.2
Exp/Cntr=0.3,0.1

Type RM Length L Ch R = 1,4726,19,19,19
BEGIN DESCRIPTION:
Mapping XS dd70d45c
END DESCRIPTION:
XS GIS Cut Line= 5
      1408841.40      6915352.24      1409557.52      6915000.69
      1409849.18      6915050.17      1410041.89      6915071.00
      1410871.32      6914561.38
#Sta/Elev= 30
  3901.3 2035.42  3927.7 2035.60  3972.7 2031.53  4170.0 2023.30  4354.9 2014.94
  4573.7 2009.87  4596.0 2007.61  4652.8 2009.86  4692.2 2008.50  4712.3 2010.89
  4726.9 2008.70  4827.9 2011.03  4832.9 2004.78  4888.2 2010.96  4893.3 2007.44
  4919.6 2010.24  4948.5 2010.26  5010.8 2007.78  5020.9 2004.66  5021.3 2004.16
  5026.3 2004.66  5030.9 2007.57  5081.2 2007.24  5110.3 2009.00  5332.5 2007.57
  5604.0 2011.02  5725.4 2013.66  5833.2 2016.21  6080.6 2025.94  6162.2 2027.12
#Mann=6,-1,0
  3901.3   0.045       0  4170.0    0.07       0  5020.9    0.07       0
  5026.3    0.07       0  5604.0    0.16       0  5725.4    0.07       0
Bank Sta=5020.9,5026.3
Exp/Cntr=0.3,0.1

Type RM Length L Ch R = 1,4707,423,423,423
BEGIN DESCRIPTION:
Mapping XS 7f7ae682
END DESCRIPTION:
XS GIS Cut Line= 5
      1408857.03      6915365.25      1409547.10      6915026.73
      1409846.58      6915068.40      1410034.08      6915089.23
      1410888.24      6914607.46
#Sta/Elev= 30
  3920.1 2035.35  3946.8 2035.47  3969.3 2032.51  4183.8 2023.34  4267.2 2020.07
  4284.2 2017.93  4329.2 2017.73  4587.7 2008.71  4604.6 2005.00  4655.2 2009.61
  4696.7 2006.82  4757.3 2008.01  4767.4 2006.74  4787.6 2008.95  4835.4 1998.24
  4835.8 1997.74  4840.8 1998.24  4858.2 1999.62  4876.4 2004.38  4881.4 2003.41
  4939.0 2007.73  4999.6 2007.33  5019.7 2004.73  5028.8 2006.83  5110.2 2008.51
  5341.5 2007.38  5645.4 2011.55  5730.1 2012.94  6085.1 2025.31  6160.4 2025.90
#Mann=6,-1,0
  3920.1   0.045       0  4183.8    0.07       0  4835.4    0.07       0
  4840.8    0.07       0  5645.4    0.16       0  5730.1    0.07       0
Bank Sta=4835.4,4840.8
Exp/Cntr=0.3,0.1

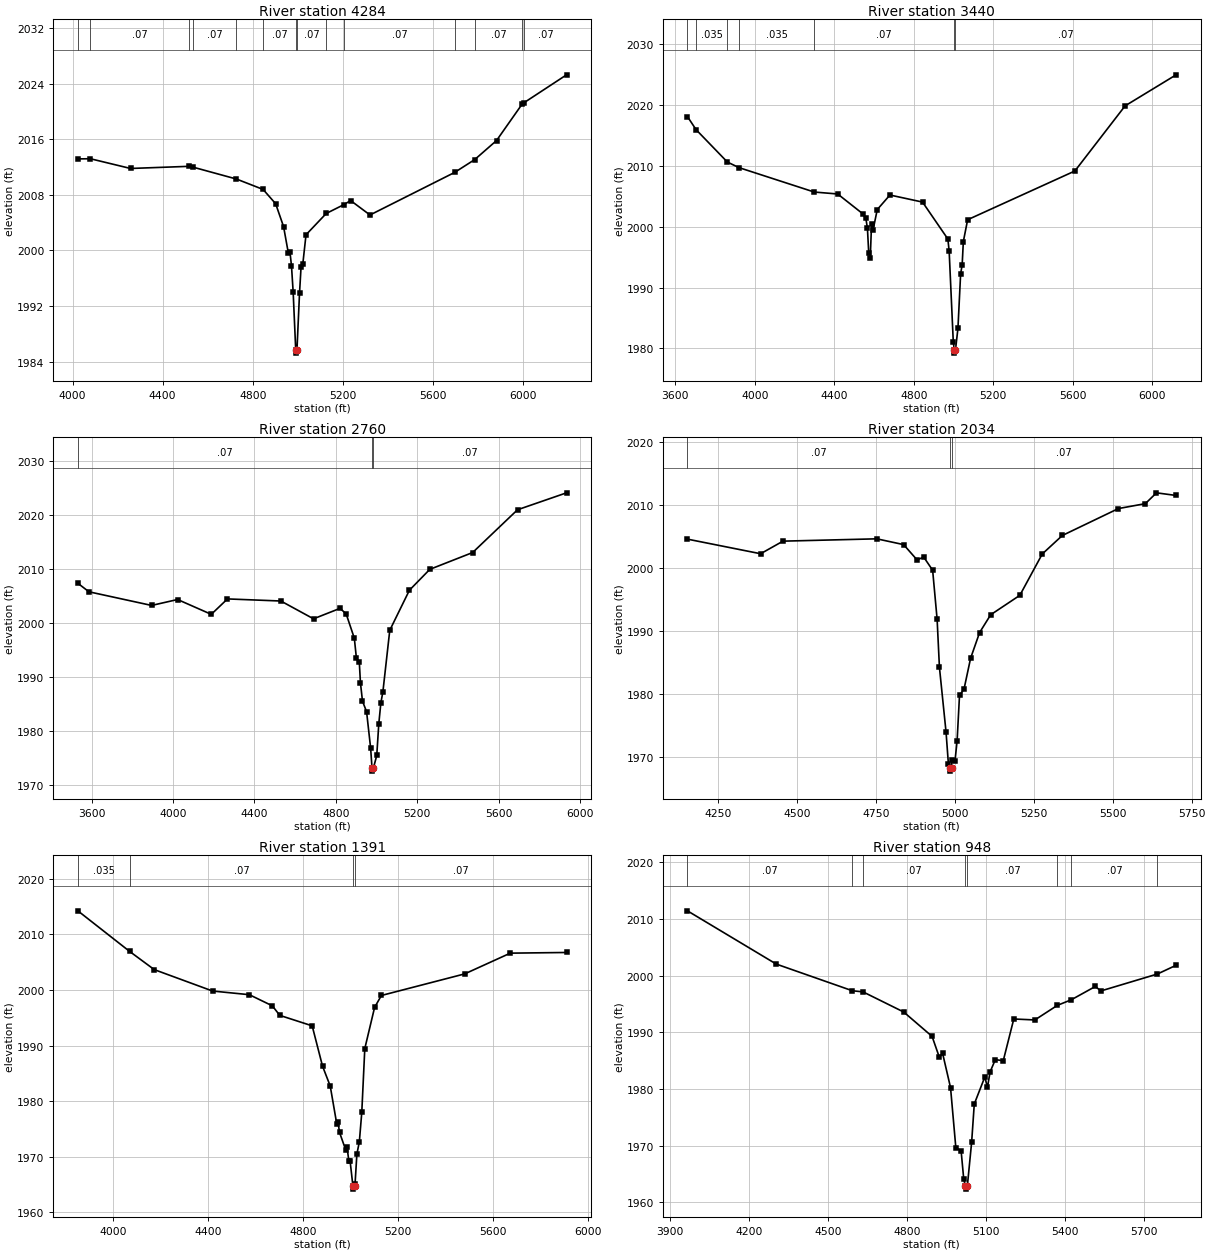
Type RM Length L Ch R = 1,4284,844,844,844
BEGIN DESCRIPTION:
Mapping XS 7857eebc
END DESCRIPTION:
XS GIS Cut Line= 3
      1409323.98      6916087.10      1410049.93      6915407.49
      1410953.55      6914658.33
#Sta/Elev= 30
  4023.6 2013.19  4079.4 2013.21  4257.4 2011.81  4518.0 2012.12  4533.5 2012.01
  4727.2 2010.29  4845.5 2008.79  4901.2 2006.73  4936.4 2003.43  4957.4 1999.64
  4964.7 1999.81  4971.5 1997.76  4978.9 1994.01  4990.2 1985.71  4990.7 1985.21
  4995.8 1985.71  5007.2 1993.90  5014.0 1997.65  5021.6 1998.02  5035.9 2002.26
  5125.7 2005.33  5205.1 2006.62  5233.8 2007.19  5319.8 2005.11  5695.3 2011.24
  5784.4 2013.09  5881.1 2015.83  5995.6 2021.12  6003.5 2021.29  6191.8 2025.30
#Mann=14,-1,0
  4023.6   0.035       0  4079.4    0.07       0  4518.0   0.035       0
  4533.5    0.07       0  4727.2   0.035       0  4845.5    0.07       0
  4990.2    0.07       0  4995.8    0.07       0  5125.7    0.16       0
  5205.1    0.07       0  5695.3    0.16       0  5784.4    0.07       0
  5995.6    0.16       0  6003.5    0.07       0
Bank Sta=4990.2,4995.8
Exp/Cntr=0.3,0.1

Type RM Length L Ch R = 1,3440,680,680,680
BEGIN DESCRIPTION:
Mapping XS 3ec16134
END DESCRIPTION:
XS GIS Cut Line= 3
      1409563.37      6916782.22      1410598.28      6915924.94
      1411185.23      6914975.01
#Sta/Elev= 30
  3660.7 2018.09  3704.5 2015.93  3861.7 2010.62  3919.6 2009.71  4299.2 2005.69
  4417.2 2005.37  4545.8 2002.06  4559.1 2001.35  4567.0 1999.74  4573.5 1995.68
  4581.3 1994.92  4587.8 2000.49  4595.6 1999.50  4616.5 2002.81  4680.3 2005.20
  4844.4 2004.04  4972.0 1997.97  4978.5 1995.99  4999.2 1981.10  5004.5 1979.72
  5004.9 1979.22  5010.2 1979.72  5022.7 1983.28  5036.2 1992.23  5044.0 1993.73
  5049.9 1997.55  5071.5 2001.14  5611.5 2009.15  5864.4 2019.85  6121.2 2024.95
#Mann=7,-1,0
  3660.7    0.07       0  3704.5   0.035       0  3861.7    0.07       0
  3919.6   0.035       0  4299.2    0.07       0  5004.5    0.07       0
  5010.2    0.07       0
Bank Sta=5004.5,5010.2
Exp/Cntr=0.3,0.1

Type RM Length L Ch R = 1,2760,726,726,726
BEGIN DESCRIPTION:
Mapping XS c9e23413
END DESCRIPTION:
XS GIS Cut Line= 3
      1410459.26      6917137.49      1411100.29      6916674.09
      1411208.41      6915067.71
#Sta/Elev= 30
  3532.3 2007.34  3586.9 2005.76  3894.7 2003.23  4022.3 2004.33  4187.9 2001.58
  4267.4 2004.44  4529.8 2004.05  4690.2 2000.75  4820.5 2002.69  4850.6 2001.66
  4890.7 1997.15  4900.7 1993.53  4915.2 1992.69  4920.7 1988.91  4930.8 1985.47
  4950.8 1983.55  4970.8 1976.78  4977.7 1973.01  4978.2 1972.51  4984.0 1973.01
  5000.9 1975.42  5010.9 1981.29  5021.0 1985.15  5031.0 1987.21  5064.8 1998.62
  5161.3 2006.05  5261.5 2009.92  5472.0 2013.04  5692.5 2020.97  5933.3 2024.11
#Mann=3,-1,0
  3532.3    0.07       0  4977.7    0.07       0  4984.0    0.07       0
Bank Sta=4977.7,4984
Exp/Cntr=0.3,0.1

Type RM Length L Ch R = 1,2034,643,643,643
BEGIN DESCRIPTION:
Mapping XS f837016b
END DESCRIPTION:
XS GIS Cut Line= 3
      1410768.17      6917098.89      1411386.05      6916527.35
      1411849.46      6915994.44
#Sta/Elev= 30
  4152.9 2004.55  4384.7 2002.23  4455.6 2004.23  4752.7 2004.60  4837.7 2003.68
  4880.3 2001.25  4901.3 2001.70  4929.6 1999.61  4943.8 1991.80  4951.1 1984.18
  4972.1 1973.87  4979.5 1968.83  4983.2 1968.18  4983.7 1967.68  4989.5 1968.18
  4990.5 1969.38  5000.5 1969.33  5007.1 1972.49  5014.7 1979.71  5029.0 1980.72
  5049.8 1985.61  5078.3 1989.70  5113.4 1992.53  5205.8 1995.62  5276.8 2002.19
  5340.4 2005.13  5518.0 2009.41  5603.3 2010.19  5638.6 2011.91  5700.8 2011.49
#Mann=3,-1,0
  4152.9    0.07       0  4983.2    0.07       0  4989.5    0.07       0
Bank Sta=4983.2,4989.5
Exp/Cntr=0.3,0.1

Type RM Length L Ch R = 1,1391,443,443,443
BEGIN DESCRIPTION:
China Creek Trib1 3.0
END DESCRIPTION:
XS GIS Cut Line= 3
      1411563.69      6917878.89      1411905.00      6916788.00
      1412127.32      6915902.42
#Sta/Elev= 30
  3852.3 2014.23  4070.5 2006.92  4173.8 2003.66  4419.0 1999.81  4573.8 1999.15
  4670.5 1997.15  4702.0 1995.43  4838.2 1993.55  4881.7 1986.31  4914.2 1982.72
  4941.4 1975.97  4946.6 1976.27  4953.4 1974.38  4979.1 1971.25  4984.9 1971.73
  4992.7 1969.19  4997.9 1969.19  5009.8 1964.69  5010.3 1964.19  5016.8 1964.69
  5018.5 1965.03  5026.3 1970.50  5036.6 1972.68  5046.9 1977.98  5059.6 1989.46
  5100.8 1996.86  5129.4 1999.01  5479.9 2002.89  5671.8 2006.62  5908.4 2006.74
#Mann=4,-1,0
  3852.3   0.035       0  4070.5    0.07       0  5009.8    0.07       0
  5016.8    0.07       0
Bank Sta=5009.8,5016.8
Exp/Cntr=0.3,0.1

Type RM Length L Ch R = 1,948,464,464,464
BEGIN DESCRIPTION:
China Creek Trib1 2.0
END DESCRIPTION:
XS GIS Cut Line= 3
      1412181.54      6918064.29      1412255.00      6917038.00
      1412251.06      6916211.83
#Sta/Elev= 30
  3966.8 2011.44  4304.0 2002.04  4593.1 1997.33  4633.1 1997.14  4787.9 1993.58
  4895.5 1989.28  4923.1 1985.59  4935.6 1986.26  4965.6 1980.23  4985.7 1969.63
  5005.7 1969.09  5015.7 1964.09  5022.2 1962.82  5022.7 1962.32  5029.3 1962.82
  5045.7 1970.60  5055.7 1977.34  5095.7 1982.11  5105.7 1980.27  5115.7 1983.01
  5135.7 1985.18  5165.7 1984.98  5205.7 1992.35  5285.7 1992.18  5370.9 1994.75
  5424.4 1995.75  5515.7 1998.10  5535.7 1997.29  5751.0 2000.29  5821.9 2001.83
#Mann=8,-1,0
  3966.8    0.07       0  4593.1    0.16       0  4633.1    0.07       0
  5022.2    0.07       0  5029.3    0.07       0  5370.9   0.035       0
  5424.4    0.07       0  5751.0   0.035       0
Bank Sta=5022.2,5029.3
Exp/Cntr=0.3,0.1

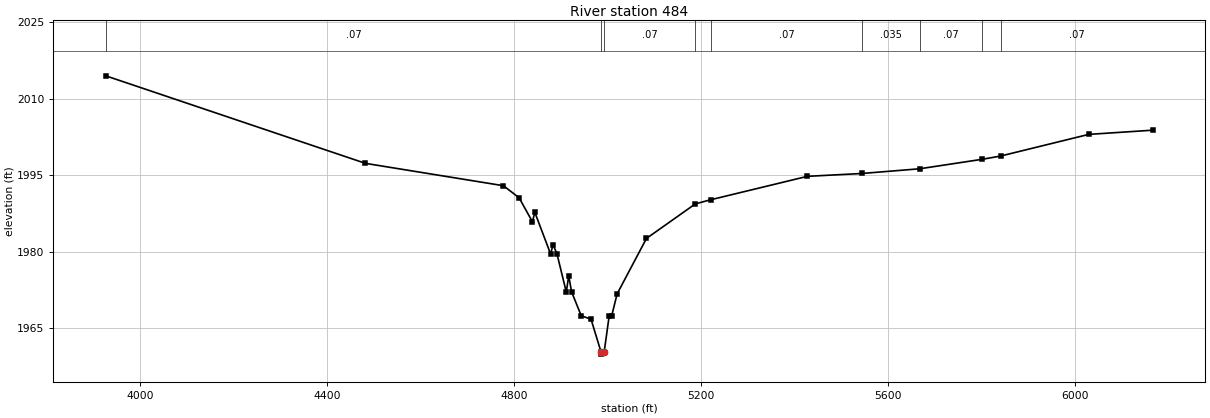
Type RM Length L Ch R = 1,484,0,0,0
BEGIN DESCRIPTION:
China Creek Trib1 1.0
END DESCRIPTION:
XS GIS Cut Line= 3
      1412405.51      6918025.66      1412705.00      6916988.00
      1412220.24      6915932.85
#Sta/Elev= 30
  3926.1 2014.51  4481.9 1997.35  4777.1 1992.97  4810.7 1990.60  4839.1 1985.91
  4844.3 1987.75  4878.0 1979.60  4883.2 1981.40  4891.6 1979.64  4911.6 1972.13
  4916.8 1975.32  4922.9 1972.18  4943.7 1967.46  4964.5 1966.82  4985.7 1960.46
  4986.2 1959.96  4992.8 1960.46  5003.5 1967.52  5008.9 1967.52  5020.4 1971.77
  5083.2 1982.64  5187.8 1989.41  5220.7 1990.22  5427.6 1994.81  5544.5 1995.37
  5667.8 1996.29  5801.8 1998.15  5841.2 1998.79  6029.6 2003.03  6167.3 2003.86
#Mann=9,-1,0
  3926.1    0.07       0  4985.7    0.07       0  4992.8    0.07       0
  5187.8   0.035       0  5220.7    0.07       0  5544.5   0.035       0
  5667.8    0.07       0  5801.8   0.035       0  5841.2    0.07       0
Bank Sta=4985.7,4992.8
Exp/Cntr=0.3,0.1

Chan Stop Cuts=-1