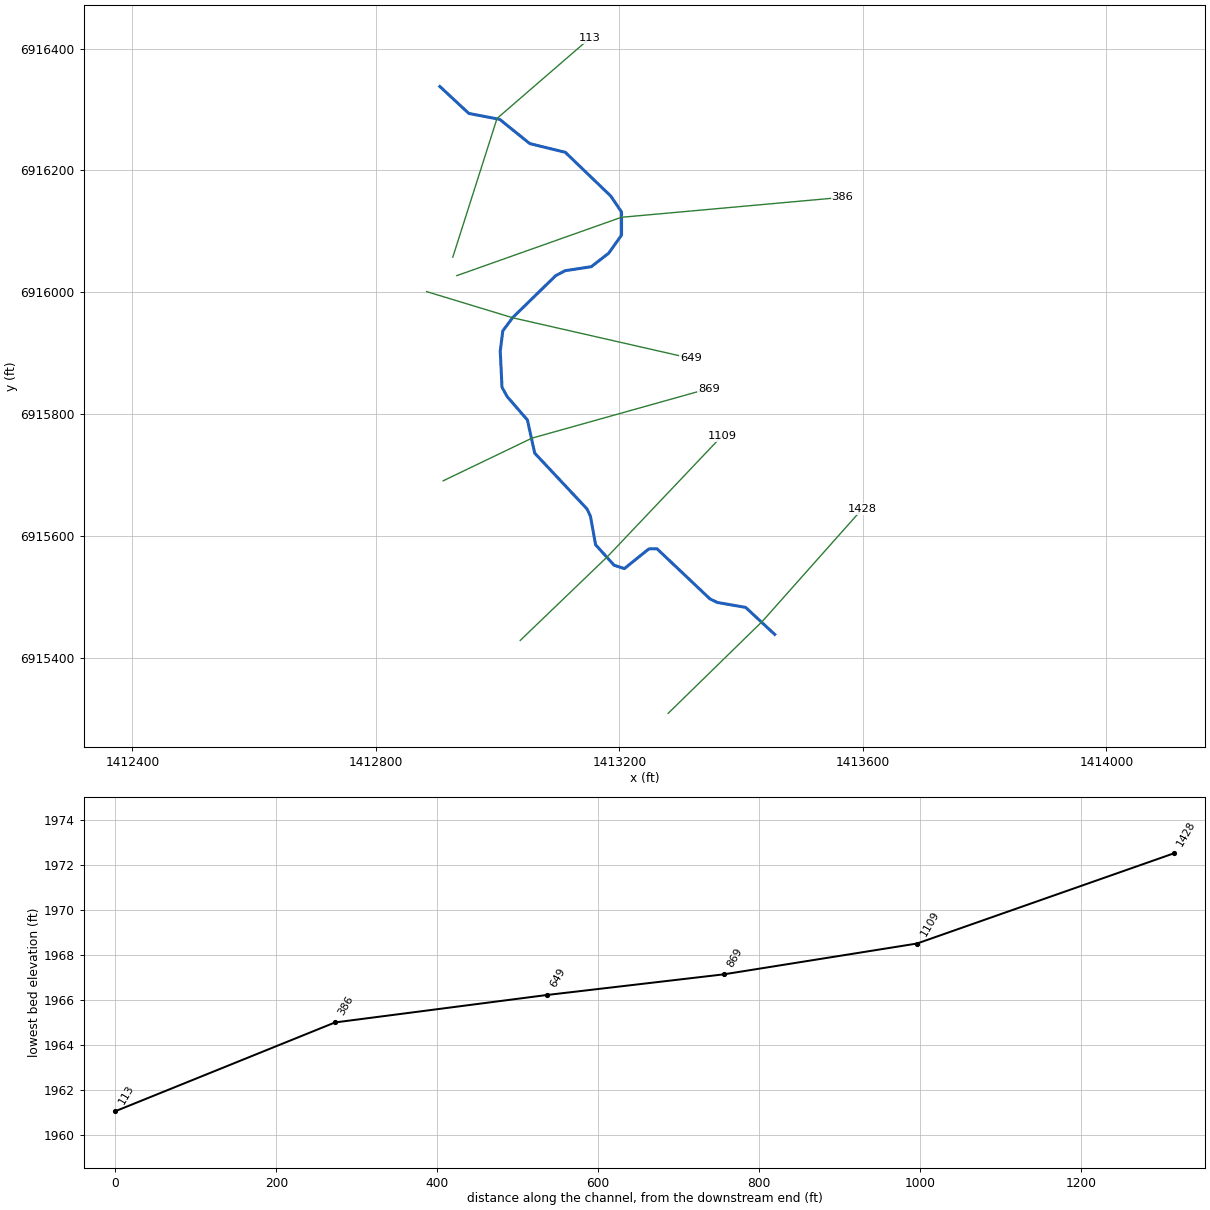
--- China Creek Trib2.prj (project) ---

Proj Title=China Creek Trib2 Base Level Engineering
Current Plan=p01
Default Exp/Contr=0.3,0.1
English Units
Geom File=g01
Flow File=f01
Plan File=p01
BEGIN DESCRIPTION:
China Creek Trib2
END DESCRIPTION:

--- China Creek Trib2.p01 (plan) ---

Plan Title=Multiple Run
Short Identifier=Multiple
Geom File=g01
Flow File=f01
Subcritical Flow
K Sum by GR= 0
Std Step Tol= 0.01
Critical Tol= 0.01
Num of Std Step Trials= 20
Max Error Tol= 0.3
Flow Tol Ratio= 0.001
Split Flow NTrial= 30
Split Flow Tol= 0.02
Split Flow Ratio= 0.02
Log Output Level= 0
Friction Slope Method= 1
Unsteady Friction Slope Method= 2
Unsteady Bridges Friction Slope Method= 1
Parabolic Critical Depth
Global Vel Dist=  1 , 1 , 1
Global Log Level= 0
CheckData=True
Encroach Param= -1, 0, 0, 0
BEGIN DESCRIPTION:
Multiple Run
END DESCRIPTION:

--- China Creek Trib2.f01 (steady flow) ---

Flow Title=Multiple
Number of Profiles=7
Profile Names=10-year,25-year,50-year,1pct_min,100-year,1pct_plu,500-year
River Rch & RM= China Creek Trib,Reach-1,1428
     277     391     487     302     603    1202     933
River Rch & RM= China Creek Trib,Reach-1,649
     278     393     490     304     606    1209     939
Boundary for River Rch & Prof#=China Creek Trib,Reach-1,1
Up Type=0
Dn Type=3
Dn Slope=0.005
Boundary for River Rch & Prof#=China Creek Trib,Reach-1,2
Up Type=0
Dn Type=3
Dn Slope=0.005
Boundary for River Rch & Prof#=China Creek Trib,Reach-1,3
Up Type=0
Dn Type=3
Dn Slope=0.005
Boundary for River Rch & Prof#=China Creek Trib,Reach-1,4
Up Type=0
Dn Type=3
Dn Slope=0.005
Boundary for River Rch & Prof#=China Creek Trib,Reach-1,5
Up Type=0
Dn Type=3
Dn Slope=0.005
Boundary for River Rch & Prof#=China Creek Trib,Reach-1,6
Up Type=0
Dn Type=3
Dn Slope=0.005
Boundary for River Rch & Prof#=China Creek Trib,Reach-1,7
Up Type=0
Dn Type=3
Dn Slope=0.005

--- China Creek Trib2.g01 (geometry) ---

Geom Title=Existing Conditions

River Reach=China Creek Trib,Reach-1
Reach XY= 30
      1413455.00      6915438.00      1413407.35      6915482.30
      1413360.97      6915490.36      1413348.91      6915496.09
      1413261.65      6915578.68      1413248.31      6915578.37
      1413208.15      6915546.08      1413191.32      6915551.50
      1413160.86      6915585.17      1413152.46      6915631.87
      1413146.82      6915644.00      1413060.84      6915735.71
      1413048.85      6915790.17      1413015.75      6915828.35
      1413007.14      6915843.97      1413004.23      6915903.09
      1413008.45      6915936.52      1413024.57      6915958.20
      1413095.32      6916027.22      1413111.08      6916035.45
      1413153.63      6916041.89      1413182.45      6916064.16
      1413203.50      6916093.87      1413203.44      6916131.92
      1413185.60      6916158.12      1413111.08      6916229.87
      1413052.81      6916244.10      1413003.33      6916283.96
      1412952.64      6916293.67      1412905.00      6916338.00

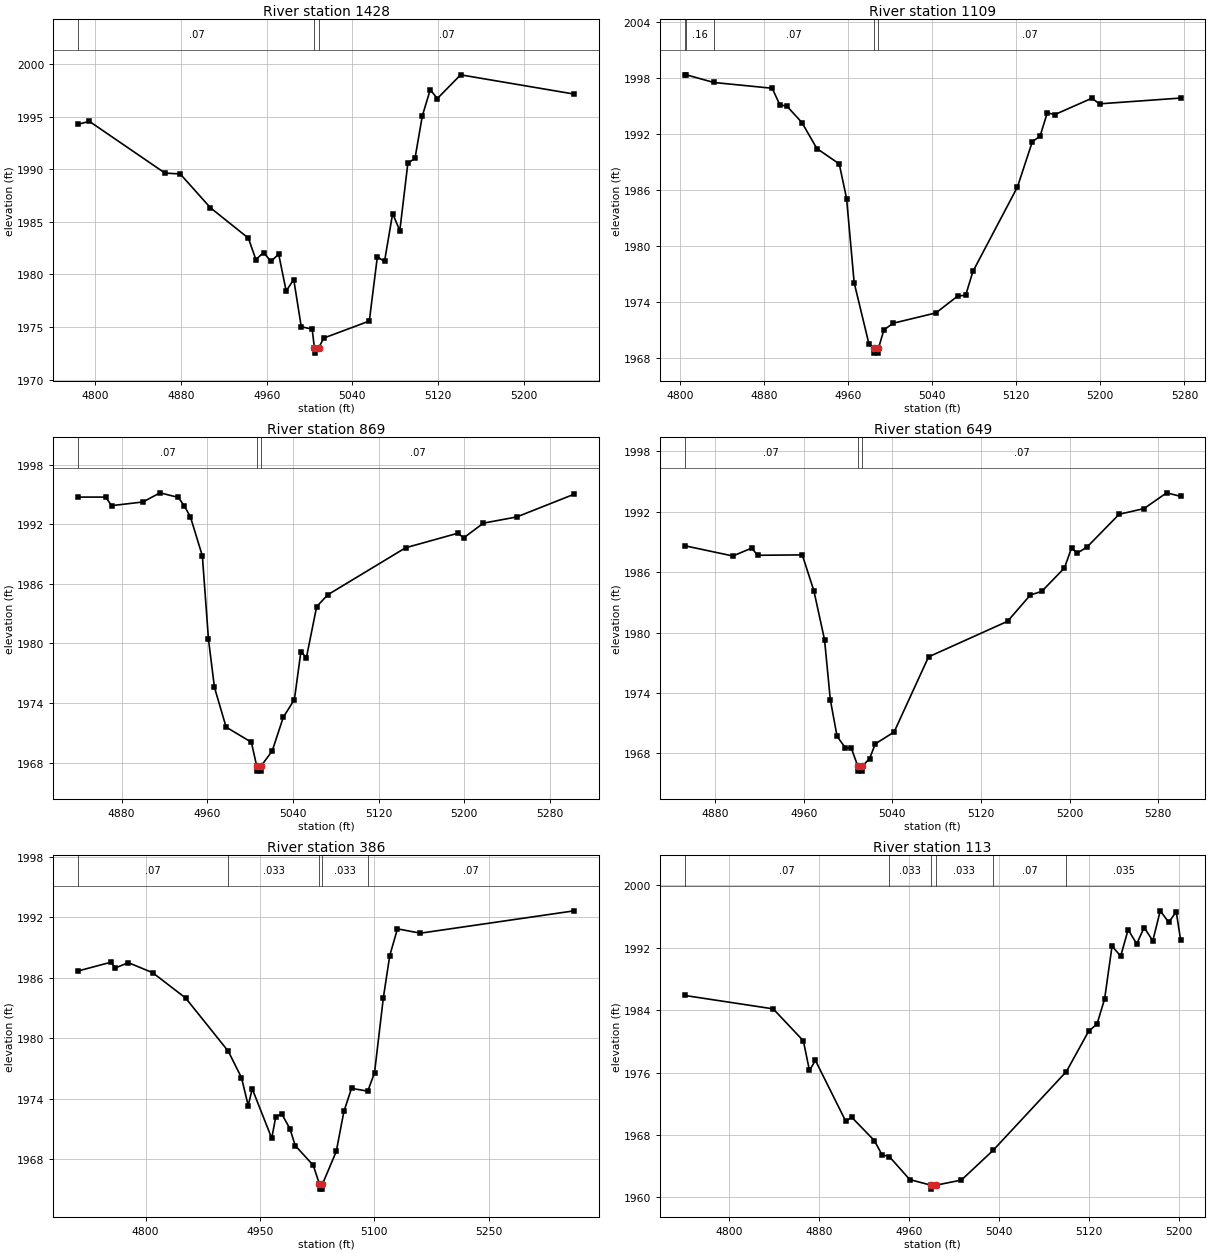
Type RM Length L Ch R = 1,1428,319,319,319
BEGIN DESCRIPTION:
China Creek Trib2 3.0
END DESCRIPTION:
XS GIS Cut Line= 3
      1413280.01      6915308.23      1413434.61      6915459.22
      1413598.95      6915644.01
#Sta/Elev= 30
  4783.9 1994.27  4794.3 1994.55  4865.0 1989.63  4879.2 1989.55  4907.5 1986.33
  4942.9 1983.45  4949.9 1981.41  4957.1 1982.08  4964.0 1981.24  4971.2 1981.93
  4978.2 1978.43  4985.3 1979.51  4992.3 1975.03  5002.5 1974.80  5004.6 1973.02
  5004.8 1972.52  5008.6 1973.02  5013.3 1973.95  5055.9 1975.57  5063.4 1981.67
  5070.1 1981.23  5077.7 1985.79  5084.4 1984.15  5091.9 1990.56  5098.6 1991.04
  5105.4 1995.05  5112.8 1997.55  5119.5 1996.72  5141.2 1998.97  5247.3 1997.14
#Mann=3,-1,0
  4783.9    0.07       0  5004.6    0.07       0  5008.6    0.07       0
Bank Sta=5004.6,5008.6
Exp/Cntr=0.3,0.1

Type RM Length L Ch R = 1,1109,240,240,240
BEGIN DESCRIPTION:
Mapping XS bd679abd
END DESCRIPTION:
XS GIS Cut Line= 3
      1413037.05      6915428.04      1413180.57      6915565.91
      1413368.47      6915763.94
#Sta/Elev= 30
  4804.4 1998.34  4805.9 1998.34  4832.1 1997.52  4887.7 1996.90  4894.9 1995.14
  4901.9 1994.96  4916.0 1993.22  4930.2 1990.44  4951.5 1988.79  4958.5 1985.08
  4965.7 1976.06  4979.8 1969.48  4984.8 1969.01  4985.0 1968.51  4988.5 1968.51
  4988.8 1969.01  4994.0 1971.01  5003.0 1971.72  5043.5 1972.82  5064.5 1974.65
  5071.8 1974.70  5078.7 1977.26  5121.1 1986.32  5135.3 1991.19  5142.6 1991.75
  5149.5 1994.27  5156.7 1994.08  5191.9 1995.83  5199.2 1995.23  5276.4 1995.85
#Mann=5,-1,0
  4804.4    0.07       0  4805.9    0.16       0  4832.1    0.07       0
  4984.8    0.07       0  4988.8    0.07       0
Bank Sta=4984.8,4988.8
Exp/Cntr=0.3,0.1

Type RM Length L Ch R = 1,869,220,220,220
BEGIN DESCRIPTION:
Mapping XS 525bd17d
END DESCRIPTION:
XS GIS Cut Line= 3
      1412910.43      6915690.21      1413056.25      6915760.29
      1413346.68      6915841.66
#Sta/Elev= 30
  4839.4 1994.72  4865.0 1994.72  4870.6 1993.86  4899.9 1994.23  4915.8 1995.15
  4932.9 1994.69  4938.5 1993.84  4944.3 1992.71  4955.4 1988.80  4961.1 1980.42
  4966.7 1975.57  4977.6 1971.57  5001.2 1970.05  5006.2 1967.64  5006.4 1967.14
  5009.9 1967.14  5010.2 1967.64  5020.7 1969.18  5031.0 1972.56  5041.4 1974.34
  5047.5 1979.18  5052.6 1978.55  5062.2 1983.70  5072.6 1984.89  5145.3 1989.62
  5194.3 1991.09  5199.5 1990.61  5218.0 1992.10  5249.1 1992.72  5302.8 1995.01
#Mann=3,-1,0
  4839.4    0.07       0  5006.2    0.07       0  5010.2    0.07       0
Bank Sta=5006.2,5010.2
Exp/Cntr=0.3,0.1

Type RM Length L Ch R = 1,649,263,263,263
BEGIN DESCRIPTION:
Mapping XS 861e77f5
END DESCRIPTION:
XS GIS Cut Line= 3
      1412883.36      6916001.01      1413024.61      6915958.07
      1413317.28      6915891.40
#Sta/Elev= 30
  4852.5 1988.63  4896.0 1987.61  4913.1 1988.40  4918.3 1987.68  4958.7 1987.72
  4969.2 1984.13  4978.8 1979.27  4984.0 1973.32  4990.1 1969.68  4997.7 1968.52
  5002.9 1968.52  5008.8 1966.72  5009.0 1966.22  5012.5 1966.22  5012.8 1966.72
  5019.4 1967.44  5024.6 1968.93  5041.6 1970.11  5072.7 1977.58  5144.1 1981.12
  5164.6 1983.73  5174.9 1984.09  5195.4 1986.42  5201.8 1988.41  5206.9 1987.89
  5215.9 1988.51  5244.8 1991.76  5267.2 1992.32  5287.7 1993.89  5300.3 1993.54
#Mann=3,-1,0
  4852.5    0.07       0  5008.8    0.07       0  5012.8    0.07       0
Bank Sta=5008.8,5012.8
Exp/Cntr=0.3,0.1

Type RM Length L Ch R = 1,386,273,273,273
BEGIN DESCRIPTION:
Mapping XS 1fe9f0c6
END DESCRIPTION:
XS GIS Cut Line= 3
      1412933.02      6916027.31      1413203.17      6916123.07
      1413565.98      6916155.85
#Sta/Elev= 30
  4711.5 1986.67  4754.6 1987.54  4759.9 1986.96  4777.3 1987.49  4809.1 1986.50
  4852.5 1983.98  4908.4 1978.70  4925.8 1976.07  4934.6 1973.30  4939.9 1974.96
  4965.5 1970.05  4970.8 1972.20  4978.8 1972.45  4989.4 1970.99  4996.3 1969.33
  5020.0 1967.36  5028.1 1965.50  5028.3 1965.00  5031.8 1965.00  5032.1 1965.50
  5050.2 1968.75  5060.2 1972.71  5070.2 1975.01  5091.5 1974.73  5100.4 1976.55
  5112.0 1984.02  5120.4 1988.20  5130.5 1990.85  5160.6 1990.42  5362.4 1992.64
#Mann=5,-1,0
  4711.5    0.07       0  4908.4   0.033       0  5028.1   0.033       0
  5032.1   0.033       0  5091.5    0.07       0
Bank Sta=5028.1,5032.1
Exp/Cntr=0.3,0.1

Type RM Length L Ch R = 1,113,0,0,0
BEGIN DESCRIPTION:
China Creek Trib2 1.0
END DESCRIPTION:
XS GIS Cut Line= 3
      1412926.30      6916057.56      1412998.95      6916285.46
      1413151.16      6916417.04
#Sta/Elev= 30
  4760.8 1985.88  4839.4 1984.16  4866.2 1980.06  4871.6 1976.26  4876.9 1977.55
  4903.8 1969.76  4909.1 1970.27  4929.2 1967.28  4936.0 1965.47  4942.6 1965.21
  4960.7 1962.27  4979.7 1961.55  4979.9 1961.05  4983.7 1961.55  5006.5 1962.21
  5034.6 1966.01  5099.8 1976.13  5119.5 1981.29  5127.0 1982.23  5133.7 1985.43
  5140.3 1992.20  5148.0 1990.92  5154.6 1994.33  5162.2 1992.49  5168.8 1994.59
  5176.5 1992.89  5183.1 1996.73  5190.7 1995.26  5197.3 1996.61  5201.2 1993.00
#Mann=6,-1,0
  4760.8    0.07       0  4942.6   0.033       0  4979.7   0.033       0
  4983.7   0.033       0  5034.6    0.07       0  5099.8   0.035       0
Bank Sta=4979.7,4983.7
Exp/Cntr=0.3,0.1

Chan Stop Cuts=-1