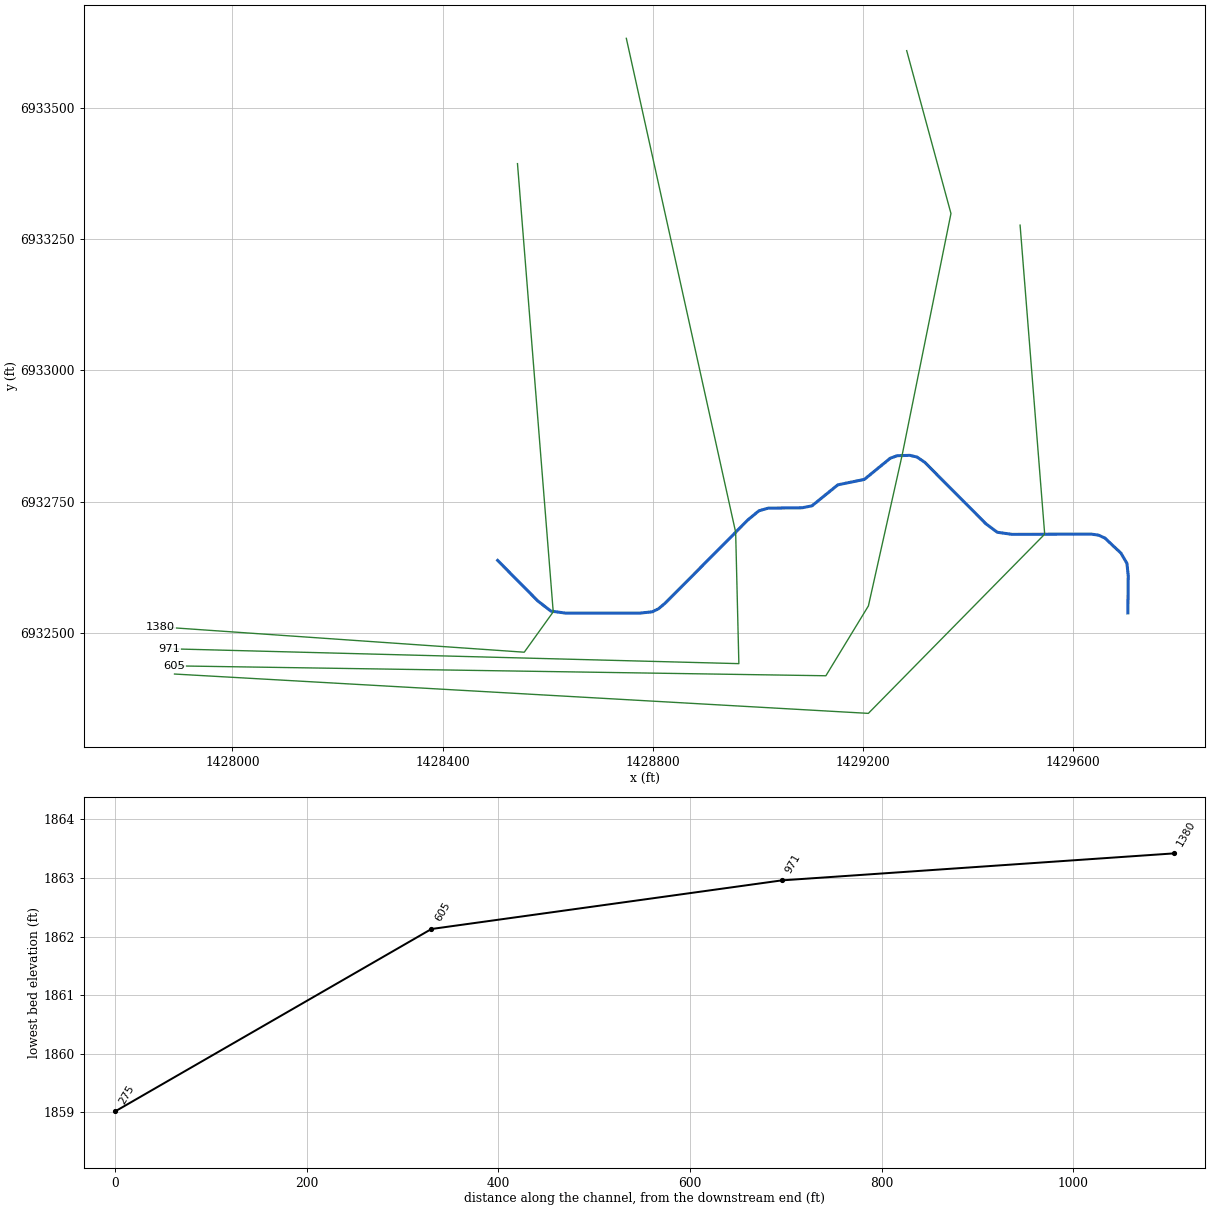
--- China Creek Trib3.prj (project) ---

Proj Title=China Creek Trib3 Base Level Engineering
Current Plan=p01
Default Exp/Contr=0.3,0.1
English Units
Geom File=g01
Flow File=f01
Plan File=p01
BEGIN DESCRIPTION:
China Creek Trib3
END DESCRIPTION:

--- China Creek Trib3.p01 (plan) ---

Plan Title=Multiple Run
Short Identifier=Multiple
Geom File=g01
Flow File=f01
Subcritical Flow
K Sum by GR= 0
Std Step Tol= 0.01
Critical Tol= 0.01
Num of Std Step Trials= 20
Max Error Tol= 0.3
Flow Tol Ratio= 0.001
Split Flow NTrial= 30
Split Flow Tol= 0.02
Split Flow Ratio= 0.02
Log Output Level= 0
Friction Slope Method= 1
Unsteady Friction Slope Method= 2
Unsteady Bridges Friction Slope Method= 1
Parabolic Critical Depth
Global Vel Dist=  1 , 1 , 1
Global Log Level= 0
CheckData=True
Encroach Param= -1, 0, 0, 0
BEGIN DESCRIPTION:
Multiple Run
END DESCRIPTION:

--- China Creek Trib3.f01 (steady flow) ---

Flow Title=Multiple
Number of Profiles=7
Profile Names=10-year,25-year,50-year,1pct_min,100-year,1pct_plu,500-year
River Rch & RM= China Creek Trib,Reach-1,1380
     243     340     420     258     515    1028     786
Boundary for River Rch & Prof#=China Creek Trib,Reach-1,1
Up Type=0
Dn Type=3
Dn Slope=0.005
Boundary for River Rch & Prof#=China Creek Trib,Reach-1,2
Up Type=0
Dn Type=3
Dn Slope=0.005
Boundary for River Rch & Prof#=China Creek Trib,Reach-1,3
Up Type=0
Dn Type=3
Dn Slope=0.005
Boundary for River Rch & Prof#=China Creek Trib,Reach-1,4
Up Type=0
Dn Type=3
Dn Slope=0.005
Boundary for River Rch & Prof#=China Creek Trib,Reach-1,5
Up Type=0
Dn Type=3
Dn Slope=0.005
Boundary for River Rch & Prof#=China Creek Trib,Reach-1,6
Up Type=0
Dn Type=3
Dn Slope=0.005
Boundary for River Rch & Prof#=China Creek Trib,Reach-1,7
Up Type=0
Dn Type=3
Dn Slope=0.005

--- China Creek Trib3.g01 (geometry) ---

Geom Title=Existing Conditions

River Reach=China Creek Trib,Reach-1
Reach XY= 30
      1428505.00      6932638.00      1428581.42      6932560.75
      1428606.44      6932541.48      1428634.82      6932537.56
      1428775.18      6932537.56      1428799.15      6932540.06
      1428811.19      6932545.81      1428825.16      6932557.60
      1428981.48      6932715.12      1429002.57      6932732.48
      1429020.22      6932737.48      1429084.90      6932738.24
      1429103.41      6932741.83      1429152.82      6932781.89
      1429203.28      6932792.22      1429252.81      6932832.69
      1429265.70      6932837.30      1429289.66      6932838.05
      1429303.37      6932834.88      1429318.21      6932824.88
      1429434.84      6932707.61      1429456.46      6932691.54
      1429484.82      6932687.57      1429635.13      6932688.09
      1429649.35      6932686.04      1429661.52      6932680.35
      1429691.84      6932651.80      1429703.24      6932632.48
      1429705.78      6932608.41      1429705.00      6932538.00

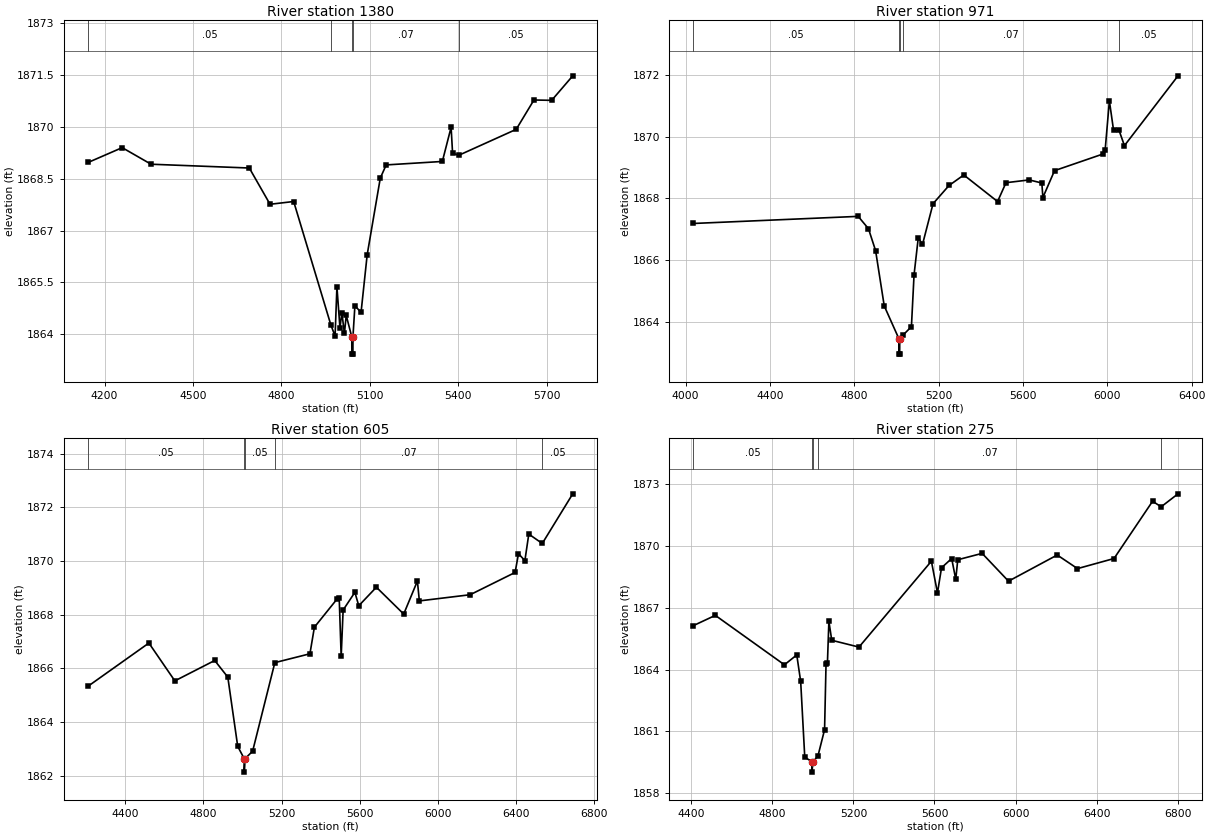
Type RM Length L Ch R = 1,1380,409,409,409
BEGIN DESCRIPTION:
China Creek Trib3 1.0
END DESCRIPTION:
XS GIS Cut Line= 4
      1428542.77      6933393.51      1428610.84      6932540.02
      1428555.68      6932463.18      1427863.64      6932511.31
#Sta/Elev= 30
  4143.8 1868.97  4259.7 1869.40  4357.7 1868.92  4691.0 1868.81  4761.3 1867.76
  4841.5 1867.84  4967.5 1864.27  4982.0 1863.94  4988.2 1865.37  4998.5 1864.18
  5005.0 1864.62  5013.6 1864.02  5019.8 1864.54  5038.6 1863.92  5038.9 1863.42
  5042.4 1863.42  5042.6 1863.92  5049.2 1864.82  5070.1 1864.63  5090.9 1866.30
  5135.4 1868.52  5155.4 1868.90  5345.9 1869.00  5375.6 1869.99  5380.6 1869.24
  5401.9 1869.18  5596.5 1869.93  5656.6 1870.78  5716.8 1870.77  5788.3 1871.48
#Mann=5,-1,0
  4143.8    0.05       0  4967.5    0.07       0  5038.6    0.07       0
  5042.6    0.07       0  5401.9    0.05       0
Bank Sta=5038.6,5042.6
Exp/Cntr=0.3,0.1

Type RM Length L Ch R = 1,971,366,366,366
BEGIN DESCRIPTION:
China Creek Trib3 2.0
END DESCRIPTION:
XS GIS Cut Line= 4
      1428750.03      6933632.08      1428958.20      6932691.65
      1428964.31      6932441.42      1427879.59      6932469.72
#Sta/Elev= 30
  4036.8 1867.19  4818.8 1867.42  4867.5 1867.02  4901.3 1866.31  4942.3 1864.52
  5011.7 1863.46  5011.9 1862.96  5015.4 1862.96  5015.7 1863.46  5033.5 1863.59
  5071.2 1863.85  5083.7 1865.53  5103.7 1866.73  5123.7 1866.51  5173.7 1867.83
  5249.5 1868.42  5319.6 1868.76  5479.7 1867.90  5519.7 1868.51  5629.7 1868.60
  5689.6 1868.50  5694.6 1868.03  5749.8 1868.90  5979.9 1869.44  5989.9 1869.57
  6009.9 1871.16  6029.9 1870.20  6056.0 1870.20  6081.3 1869.71  6335.4 1871.97
#Mann=5,-1,0
  4036.8    0.05       0  5011.7    0.05       0  5015.7    0.05       0
  5033.5    0.07       0  6056.0    0.05       0
Bank Sta=5011.7,5015.7
Exp/Cntr=0.3,0.1

Type RM Length L Ch R = 1,605,330,330,330
BEGIN DESCRIPTION:
China Creek Trib3 3.0
END DESCRIPTION:
XS GIS Cut Line= 6
      1429283.88      6933608.63      1429368.17      6933298.52
      1429275.20      6932838.37      1429210.97      6932551.32
      1429130.00      6932418.34      1427889.98      6932437.18
#Sta/Elev= 30
  4209.2 1865.33  4520.7 1866.94  4653.5 1865.53  4857.6 1866.29  4924.6 1865.67
  4975.3 1863.09  5008.6 1862.63  5008.9 1862.13  5012.6 1862.63  5051.6 1862.91
  5165.3 1866.21  5344.9 1866.54  5367.7 1867.53  5484.8 1868.59  5494.8 1868.61
  5504.8 1866.44  5514.8 1868.17  5574.9 1868.83  5594.9 1868.33  5684.9 1869.02
  5824.9 1868.02  5894.9 1869.25  5904.9 1868.51  6164.9 1868.74  6394.9 1869.57
  6412.3 1870.27  6445.0 1870.01  6465.0 1871.00  6534.0 1870.65  6690.0 1872.50
#Mann=5,-1,0
  4209.2    0.05       0  5008.6    0.05       0  5012.6    0.05       0
  5165.3    0.07       0  6534.0    0.05       0
Bank Sta=5008.6,5012.6
Exp/Cntr=0.3,0.1

Type RM Length L Ch R = 1,275,0,0,0
BEGIN DESCRIPTION:
China Creek Trib3 4.0
END DESCRIPTION:
XS GIS Cut Line= 4
      1429499.80      6933276.37      1429546.65      6932687.93
      1429210.85      6932346.71      1427889.72      6932421.62
#Sta/Elev= 30
  4409.7 1866.13  4518.4 1866.63  4859.5 1864.23  4920.4 1864.71  4939.7 1863.42
  4959.8 1859.75  4995.5 1859.52  4995.7 1859.02  4999.5 1859.52  5024.5 1859.79
  5057.6 1861.08  5064.8 1864.26  5071.8 1864.34  5078.9 1866.34  5093.1 1865.42
  5227.4 1865.09  5584.8 1869.26  5614.8 1867.72  5634.8 1868.94  5684.9 1869.39
  5705.0 1868.38  5715.0 1869.33  5835.2 1869.64  5965.4 1868.29  6205.8 1869.56
  6305.9 1868.90  6486.2 1869.39  6676.5 1872.17  6718.8 1871.90  6802.0 1872.53
#Mann=5,-1,0
  4409.7    0.05       0  4995.5    0.05       0  4999.5    0.05       0
  5024.5    0.07       0  6718.8    0.05       0
Bank Sta=4995.5,4999.5
Exp/Cntr=0.3,0.1

Chan Stop Cuts=-1