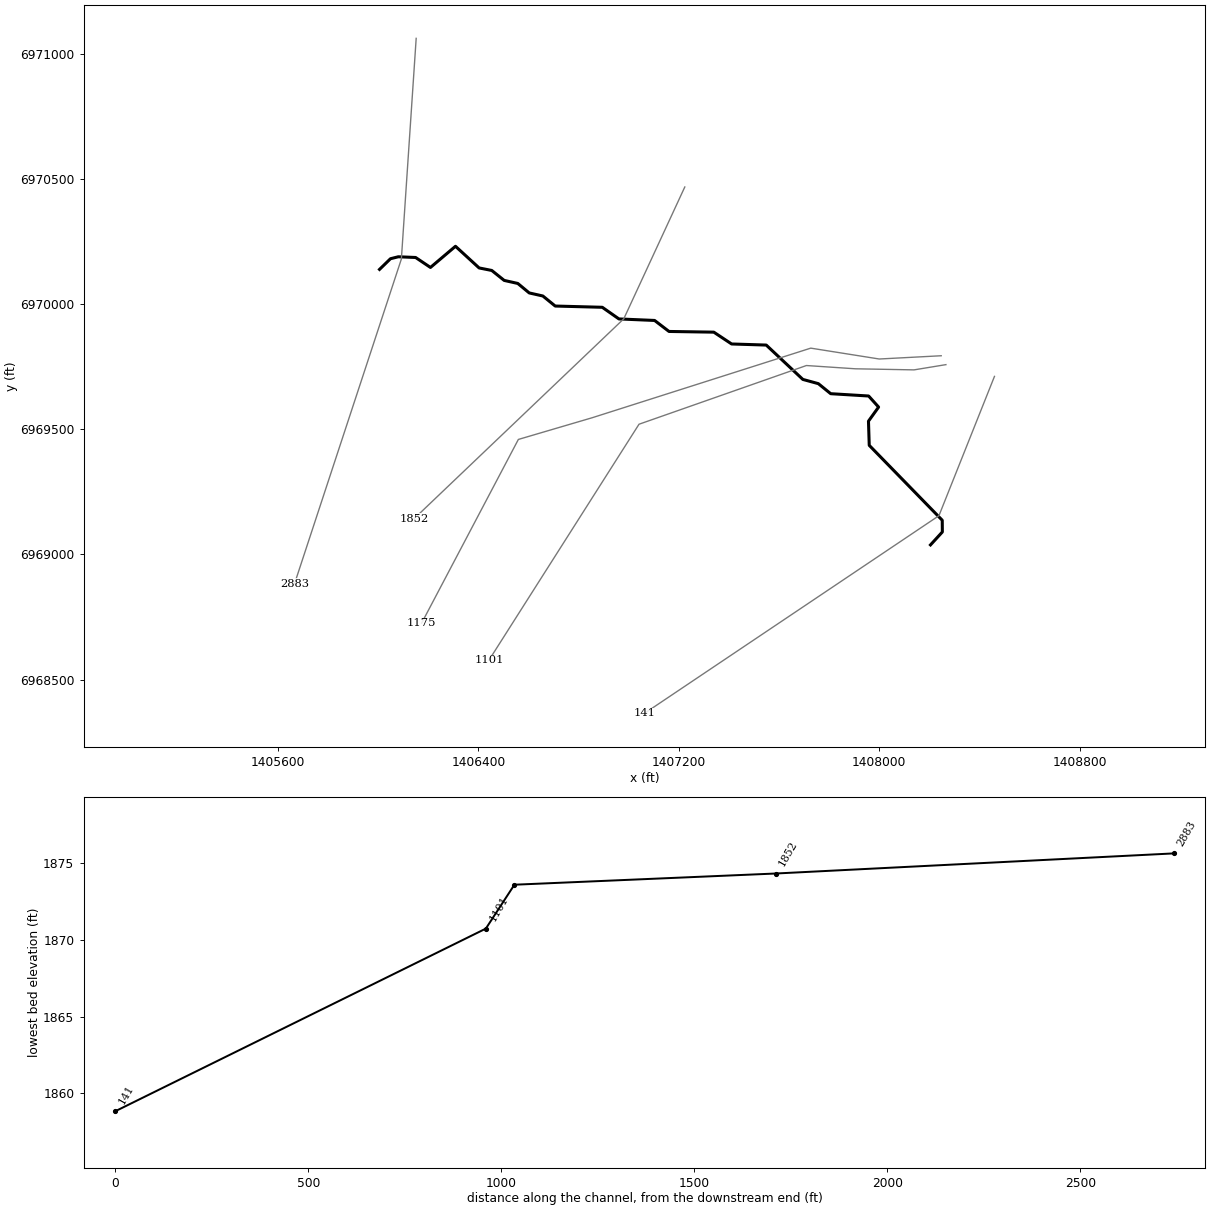
--- Clear Fork Trib1.prj (project) ---

Proj Title=Clear Fork Trib1 Base Level Engineering
Current Plan=p01
Default Exp/Contr=0.3,0.1
English Units
Geom File=g01
Flow File=f01
Plan File=p01
BEGIN DESCRIPTION:
Clear Fork Trib1
END DESCRIPTION:

--- Clear Fork Trib1.p01 (plan) ---

Plan Title=Multiple Run
Short Identifier=Multiple
Geom File=g01
Flow File=f01
Subcritical Flow
K Sum by GR= 0
Std Step Tol= 0.01
Critical Tol= 0.01
Num of Std Step Trials= 20
Max Error Tol= 0.3
Flow Tol Ratio= 0.001
Split Flow NTrial= 30
Split Flow Tol= 0.02
Split Flow Ratio= 0.02
Log Output Level= 0
Friction Slope Method= 1
Unsteady Friction Slope Method= 2
Unsteady Bridges Friction Slope Method= 1
Parabolic Critical Depth
Global Vel Dist=  1 , 1 , 1
Global Log Level= 0
CheckData=True
Encroach Param= -1, 0, 0, 0
BEGIN DESCRIPTION:
Multiple Run
END DESCRIPTION:

--- Clear Fork Trib1.f01 (steady flow) ---

Flow Title=Multiple
Number of Profiles=7
Profile Names=10-year,25-year,50-year,1pct_min,100-year,1pct_plu,500-year
River Rch & RM= Clear Fork Trib1,Reach-1,2883
     141     191     232     140     279     556     408
River Rch & RM= Clear Fork Trib1,Reach-1,1852
     332     475     596     371     741    1479    1162
Boundary for River Rch & Prof#=Clear Fork Trib1,Reach-1,1
Up Type=0
Dn Type=3
Dn Slope=0.005
Boundary for River Rch & Prof#=Clear Fork Trib1,Reach-1,2
Up Type=0
Dn Type=3
Dn Slope=0.005
Boundary for River Rch & Prof#=Clear Fork Trib1,Reach-1,3
Up Type=0
Dn Type=3
Dn Slope=0.005
Boundary for River Rch & Prof#=Clear Fork Trib1,Reach-1,4
Up Type=0
Dn Type=3
Dn Slope=0.005
Boundary for River Rch & Prof#=Clear Fork Trib1,Reach-1,5
Up Type=0
Dn Type=3
Dn Slope=0.005
Boundary for River Rch & Prof#=Clear Fork Trib1,Reach-1,6
Up Type=0
Dn Type=3
Dn Slope=0.005
Boundary for River Rch & Prof#=Clear Fork Trib1,Reach-1,7
Up Type=0
Dn Type=3
Dn Slope=0.005

--- Clear Fork Trib1.g01 (geometry) ---

Geom Title=Existing Conditions

River Reach=Clear Fork Trib1,Reach-1
Reach XY= 30
      1406005.00      6970138.00      1406048.68      6970180.64
      1406080.00      6970188.47      1406149.12      6970185.63
      1406208.42      6970145.82      1406308.33      6970230.38
      1406402.70      6970143.86      1406453.26      6970133.81
      1406502.80      6970094.08      1406557.20      6970081.92
      1406602.80      6970044.08      1406657.18      6970031.88
      1406706.55      6969991.75      1406894.49      6969986.78
      1406960.94      6969940.27      1407103.43      6969934.21
      1407160.94      6969890.26      1407339.78      6969887.48
      1407410.94      6969840.27      1407549.14      6969835.93
      1407695.32      6969698.76      1407757.17      6969681.86
      1407806.56      6969641.76      1407958.01      6969632.54
      1407997.78      6969588.35      1407957.37      6969532.12
      1407960.40      6969435.57      1408251.93      6969136.42
      1408252.33      6969089.62      1408205.00      6969038.00

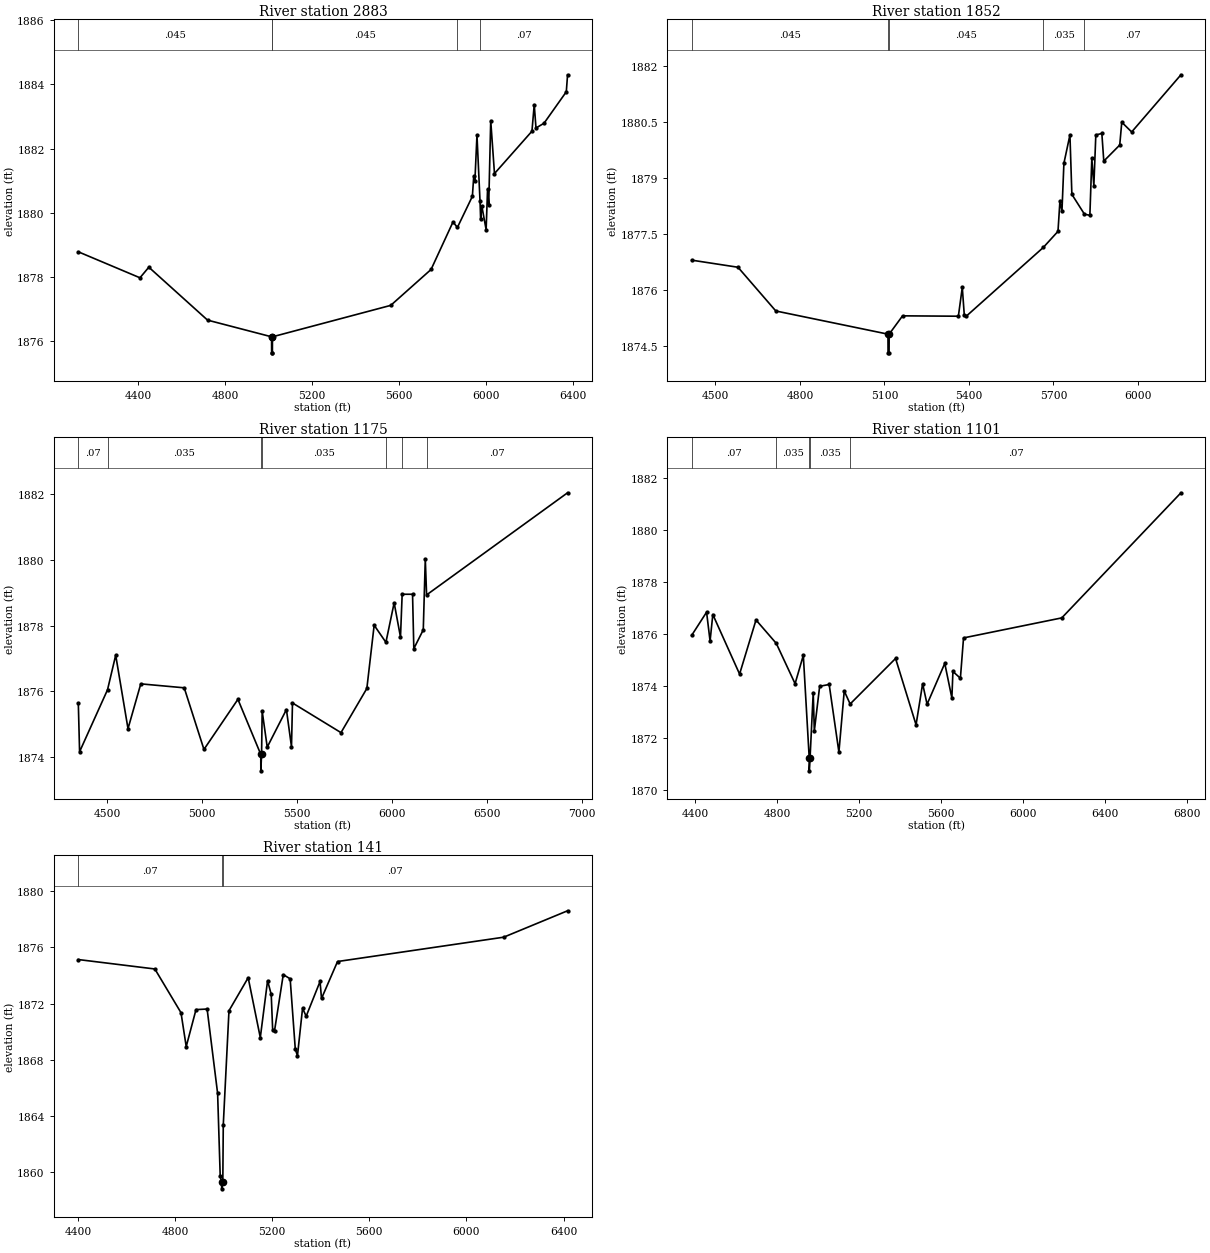
Type RM Length L Ch R = 1,2883,1031,1031,1031
BEGIN DESCRIPTION:
Clear Fork Trib1 6.0
END DESCRIPTION:
XS GIS Cut Line= 3
      1406151.41      6971060.67      1406092.28      6970179.53
      1405665.50      6968882.46
#Sta/Elev= 30
  4126.1 1878.78  4409.4 1877.97  4450.2 1878.30  4720.1 1876.65  5014.3 1876.13
  5014.6 1875.63  5018.1 1875.63  5018.3 1876.13  5562.0 1877.11  5747.4 1878.23
  5848.1 1879.71  5868.4 1879.54  5937.2 1880.51  5943.4 1881.13  5948.7 1880.98
  5958.3 1882.42  5972.4 1880.35  5975.2 1879.79  5980.5 1880.21  6000.4 1879.47
  6007.0 1880.73  6012.3 1880.24  6021.5 1882.87  6038.8 1881.22  6211.0 1882.54
  6221.5 1883.37  6229.5 1882.64  6266.6 1882.79  6368.9 1883.77  6374.7 1884.30
#Mann=5,-1,0
  4126.1   0.045       0  5014.3   0.045       0  5018.3   0.045       0
  5868.4   0.035       0  5972.4    0.07       0
Bank Sta=5014.3,5018.3
Exp/Cntr=0.3,0.1

Type RM Length L Ch R = 1,1852,677,677,677
BEGIN DESCRIPTION:
Mapping XS c496810b
END DESCRIPTION:
XS GIS Cut Line= 3
      1407223.96      6970467.14      1406980.40      6969940.86
      1406143.13      6969142.64
#Sta/Elev= 30
  4415.9 1876.80  4580.2 1876.61  4714.5 1875.44  5112.6 1874.82  5112.9 1874.32
  5116.5 1874.32  5116.8 1874.82  5164.4 1875.31  5362.5 1875.30  5376.4 1876.07
  5383.6 1875.32  5390.5 1875.30  5664.0 1877.14  5716.1 1877.57  5723.0 1878.38
  5730.2 1878.11  5737.1 1879.39  5758.5 1880.15  5765.4 1878.56  5810.0 1878.03
  5829.3 1878.00  5836.2 1879.52  5843.4 1878.79  5850.4 1880.15  5871.8 1880.19
  5878.7 1879.45  5935.3 1879.88  5942.5 1880.49  5977.7 1880.23  6152.6 1881.76
#Mann=5,-1,0
  4415.9   0.045       0  5112.6   0.045       0  5116.8   0.045       0
  5664.0   0.035       0  5810.0    0.07       0
Bank Sta=5112.6,5116.8
Exp/Cntr=0.3,0.1

Type RM Length L Ch R = 1,1175,74,74,74
BEGIN DESCRIPTION:
Mapping XS 686adb1a
END DESCRIPTION:
XS GIS Cut Line= 6
      1408247.78      6969793.29      1408000.37      6969780.27
      1407726.93      6969823.67      1406854.53      6969545.89
      1406559.39      6969459.09      1406173.11      6968725.59
#Sta/Elev= 30
  4347.9 1875.64  4354.6 1874.17  4501.7 1876.05  4544.8 1877.10  4609.6 1874.87
  4676.9 1876.23  4905.7 1876.11  5009.6 1874.24  5188.5 1875.76  5308.9 1874.09
  5309.2 1873.59  5313.1 1874.09  5316.3 1875.40  5342.9 1874.31  5444.0 1875.45
  5470.7 1874.32  5475.9 1875.65  5731.4 1874.75  5867.6 1876.09  5906.1 1878.01
  5968.0 1877.49  6011.4 1878.69  6044.8 1877.65  6053.6 1878.95  6108.3 1878.95
  6115.0 1877.30  6164.8 1877.87  6175.4 1880.02  6182.3 1878.93  6924.8 1882.03
#Mann=7,-1,0
  4347.9    0.07       0  4501.7   0.035       0  5308.9   0.035       0
  5313.1   0.035       0  5968.0    0.07       0  6053.6   0.035       0
  6182.3    0.07       0
Bank Sta=5308.9,5313.1
Exp/Cntr=0.3,0.1

Type RM Length L Ch R = 1,1101,960,960,960
BEGIN DESCRIPTION:
Mapping XS 08ef8112
END DESCRIPTION:
XS GIS Cut Line= 6
      1408266.58      6969757.80      1408139.26      6969736.87
      1407904.88      6969741.21      1407709.57      6969754.23
      1407041.16      6969519.85      1406442.21      6968578.02
#Sta/Elev= 30
  4384.8 1875.94  4457.3 1876.83  4474.3 1875.72  4487.7 1876.74  4618.1 1874.45
  4698.1 1876.53  4796.9 1875.63  4888.5 1874.08  4928.6 1875.17  4957.3 1871.23
  4957.6 1870.73  4961.5 1871.23  4976.9 1873.74  4982.2 1872.26  5008.2 1873.98
  5054.6 1874.05  5102.0 1871.45  5128.0 1873.80  5156.7 1873.30  5378.1 1875.05
  5477.9 1872.50  5509.9 1874.08  5531.6 1873.29  5617.8 1874.86  5652.4 1873.53
  5657.5 1874.55  5693.9 1874.29  5709.2 1875.84  6187.8 1876.61  6768.5 1881.42
#Mann=5,-1,0
  4384.8    0.07       0  4796.9   0.035       0  4957.3   0.035       0
  4961.5   0.035       0  5156.7    0.07       0
Bank Sta=4957.3,4961.5
Exp/Cntr=0.3,0.1

Type RM Length L Ch R = 1,141,0,0,0
BEGIN DESCRIPTION:
Clear Fork Trib1 1.0
END DESCRIPTION:
XS GIS Cut Line= 3
      1408460.44      6969710.84      1408238.76      6969154.69
      1407062.84      6968365.32
#Sta/Elev= 30
  4401.3 1875.14  4716.5 1874.47  4824.2 1871.36  4845.7 1868.95  4886.0 1871.58
  4931.8 1871.62  4975.0 1865.62  4985.7 1859.74  4991.3 1859.33  4991.7 1858.83
  4996.4 1859.33  4998.3 1863.37  5021.8 1871.50  5100.9 1873.85  5150.8 1869.59
  5180.8 1873.64  5195.8 1872.66  5201.8 1870.11  5209.3 1870.06  5245.4 1874.07
  5273.8 1873.77  5294.9 1868.77  5303.8 1868.29  5324.8 1871.67  5339.8 1871.11
  5396.9 1873.58  5402.9 1872.37  5468.9 1875.00  6153.0 1876.73  6416.3 1878.61
#Mann=3,-1,0
  4401.3    0.07       0  4991.3    0.07       0  4996.4    0.07       0
Bank Sta=4991.3,4996.4
Exp/Cntr=0.3,0.1

Chan Stop Cuts=-1