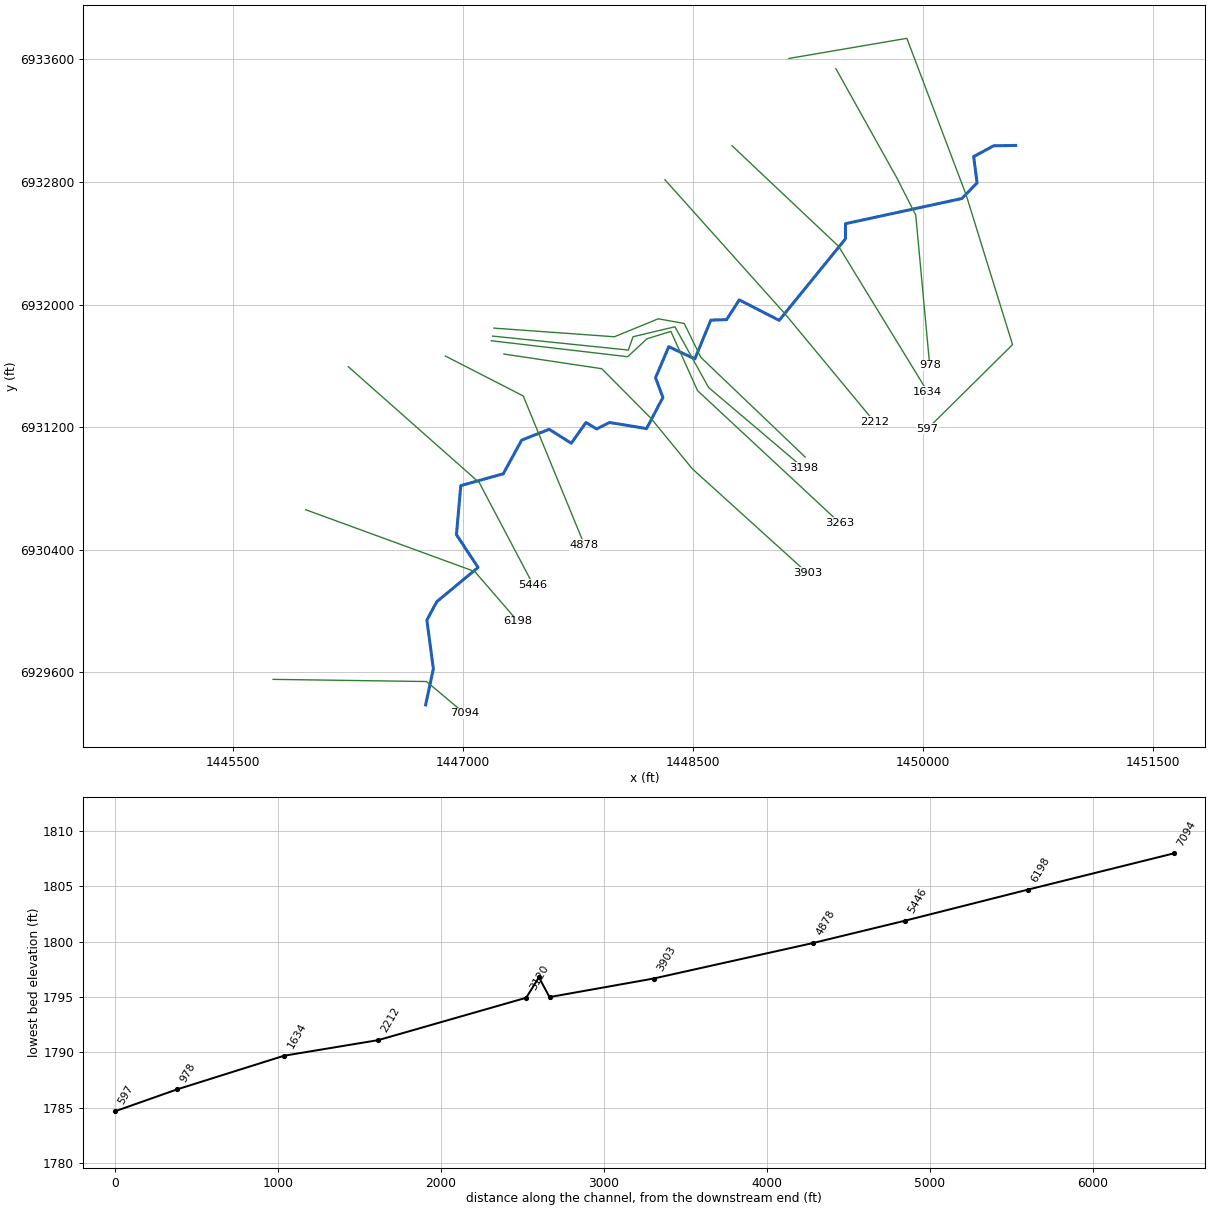
--- Clear Fork Trib10.prj (project) ---

Proj Title=Clear Fork Trib10 Base Level Engineering
Current Plan=p01
Default Exp/Contr=0.3,0.1
English Units
Geom File=g01
Flow File=f01
Plan File=p01
BEGIN DESCRIPTION:
Clear Fork Trib10
END DESCRIPTION:

--- Clear Fork Trib10.p01 (plan) ---

Plan Title=Multiple Run
Short Identifier=Multiple
Geom File=g01
Flow File=f01
Subcritical Flow
K Sum by GR= 0
Std Step Tol= 0.01
Critical Tol= 0.01
Num of Std Step Trials= 20
Max Error Tol= 0.3
Flow Tol Ratio= 0.001
Split Flow NTrial= 30
Split Flow Tol= 0.02
Split Flow Ratio= 0.02
Log Output Level= 0
Friction Slope Method= 1
Unsteady Friction Slope Method= 2
Unsteady Bridges Friction Slope Method= 1
Parabolic Critical Depth
Global Vel Dist=  1 , 1 , 1
Global Log Level= 0
CheckData=True
Encroach Param= -1, 0, 0, 0
BEGIN DESCRIPTION:
Multiple Run
END DESCRIPTION:

--- Clear Fork Trib10.f01 (steady flow) ---

Flow Title=Multiple
Number of Profiles=7
Profile Names=10-year,25-year,50-year,1pct_min,100-year,1pct_plu,500-year
River Rch & RM= Clear Fork Trib1,Reach-1,7094
     221     303     369     224     447     891     662
River Rch & RM= Clear Fork Trib1,Reach-1,5446
     241     332     405     246     491     980     730
River Rch & RM= Clear Fork Trib1,Reach-1,1634
     416     590     737     457     911    1818    1410
Boundary for River Rch & Prof#=Clear Fork Trib1,Reach-1,1
Up Type=0
Dn Type=3
Dn Slope=0.005
Boundary for River Rch & Prof#=Clear Fork Trib1,Reach-1,2
Up Type=0
Dn Type=3
Dn Slope=0.005
Boundary for River Rch & Prof#=Clear Fork Trib1,Reach-1,3
Up Type=0
Dn Type=3
Dn Slope=0.005
Boundary for River Rch & Prof#=Clear Fork Trib1,Reach-1,4
Up Type=0
Dn Type=3
Dn Slope=0.005
Boundary for River Rch & Prof#=Clear Fork Trib1,Reach-1,5
Up Type=0
Dn Type=3
Dn Slope=0.005
Boundary for River Rch & Prof#=Clear Fork Trib1,Reach-1,6
Up Type=0
Dn Type=3
Dn Slope=0.005
Boundary for River Rch & Prof#=Clear Fork Trib1,Reach-1,7
Up Type=0
Dn Type=3
Dn Slope=0.005

--- Clear Fork Trib10.g01 (geometry) ---

Geom Title=Existing Conditions

River Reach=Clear Fork Trib1,Reach-1
Reach XY= 30
      1446755.00      6929388.00      1446805.43      6929622.82
      1446763.04      6929941.32      1446828.00      6930061.47
      1447097.24      6930284.58      1446956.05      6930498.44
      1446984.35      6930818.58      1447261.50      6930895.73
      1447381.42      6931115.15      1447561.13      6931186.22
      1447705.22      6931095.00      1447801.34      6931230.28
      1447870.36      6931188.30      1447955.00      6931230.38
      1448196.52      6931190.66      1448303.20      6931394.11
      1448255.10      6931522.60      1448341.25      6931724.76
      1448511.37      6931645.33      1448615.76      6931898.39
      1448718.68      6931901.51      1448801.33      6932030.31
      1449061.67      6931896.81      1449493.75      6932428.01
      1449494.49      6932527.52      1450253.52      6932691.61
      1450353.04      6932793.88      1450330.59      6932965.01
      1450460.91      6933035.81      1450605.00      6933038.00

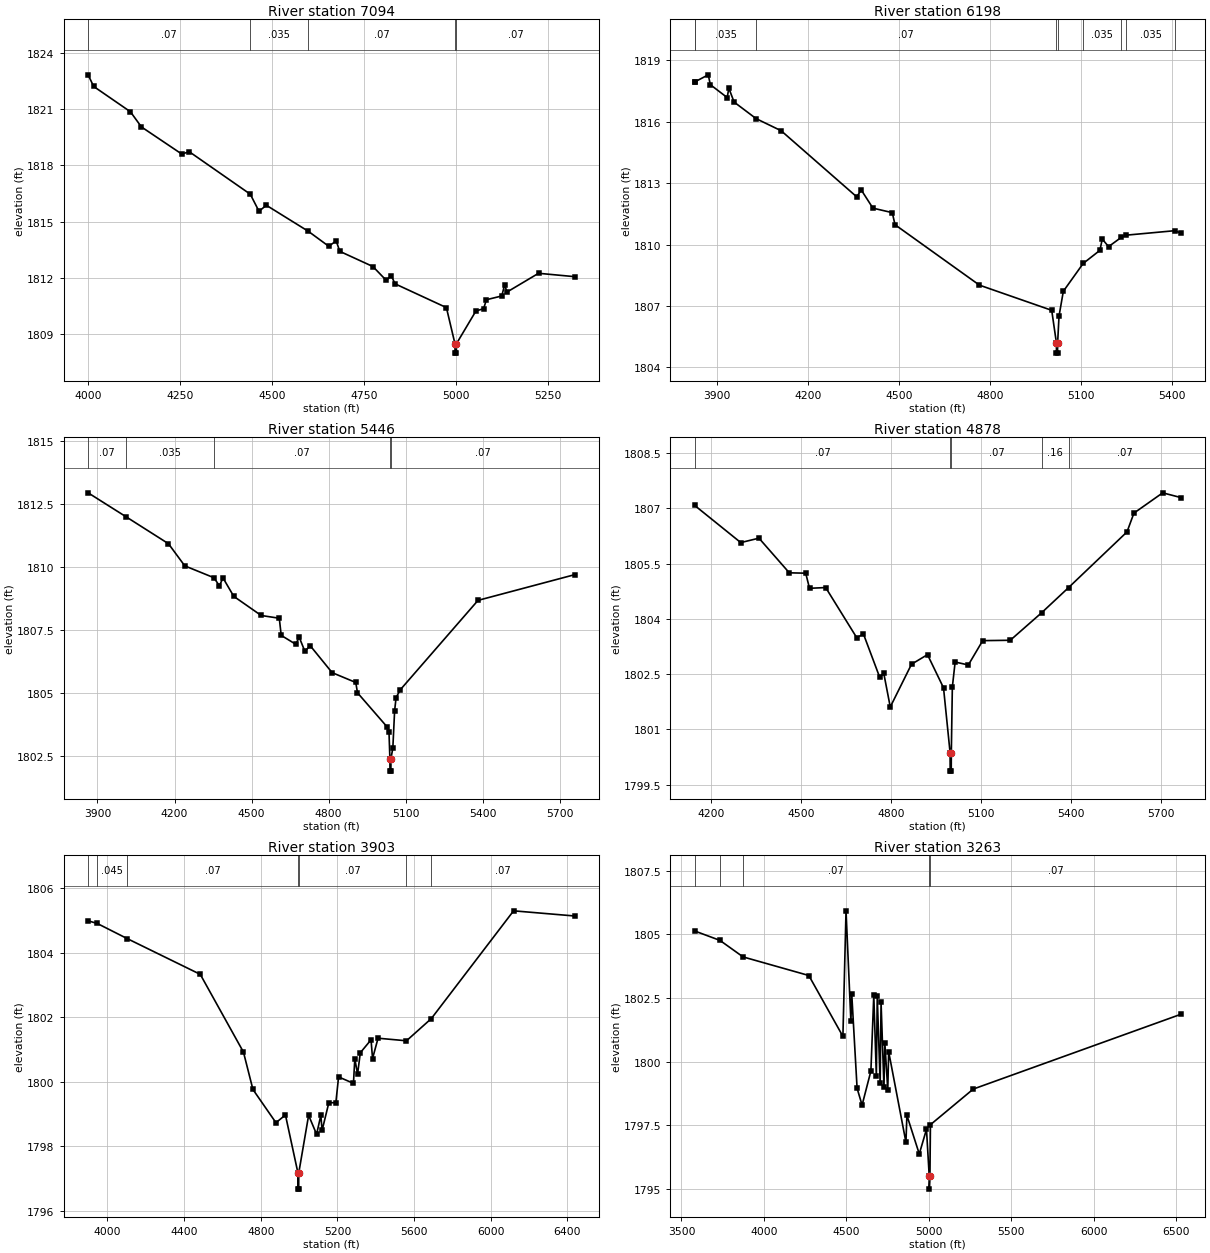
Type RM Length L Ch R = 1,7094,896,896,896
BEGIN DESCRIPTION:
Clear Fork Trib10 8.0
END DESCRIPTION:
XS GIS Cut Line= 3
      1445759.93      6929554.50      1446760.73      6929540.34
      1447008.44      6929332.59
#Sta/Elev= 30
  3999.1 1822.83  4014.2 1822.21  4114.2 1820.86  4144.2 1820.05  4254.2 1818.60
  4274.2 1818.73  4440.5 1816.46  4464.2 1815.55  4484.2 1815.87  4598.5 1814.48
  4654.2 1813.68  4674.2 1813.97  4684.2 1813.41  4774.3 1812.60  4810.7 1811.86
  4824.3 1812.12  4834.3 1811.68  4974.3 1810.41  4997.6 1808.48  4997.9 1807.98
  5001.4 1807.98  5001.6 1808.48  5054.7 1810.23  5075.5 1810.35  5083.3 1810.83
  5125.0 1811.03  5132.7 1811.62  5139.3 1811.24  5225.1 1812.24  5323.3 1812.06
#Mann=5,-1,0
  3999.1    0.07       0  4440.5   0.035       0  4598.5    0.07       0
  4997.6    0.07       0  5001.6    0.07       0
Bank Sta=4997.6,5001.6
Exp/Cntr=0.3,0.1

Type RM Length L Ch R = 1,6198,752,752,752
BEGIN DESCRIPTION:
Clear Fork Trib10 7.0
END DESCRIPTION:
XS GIS Cut Line= 3
      1445972.60      6930661.29      1447075.98      6930257.91
      1447356.81      6929932.54
#Sta/Elev= 30
  3825.2 1817.95  3826.6 1817.95  3870.3 1818.29  3877.1 1817.81  3932.8 1817.18
  3938.1 1817.64  3955.5 1816.96  4028.2 1816.15  4110.7 1815.56  4360.1 1812.33
  4374.8 1812.67  4413.4 1811.78  4477.2 1811.56  4486.3 1810.97  4764.7 1808.02
  5003.1 1806.79  5018.6 1805.20  5018.8 1804.70  5022.3 1804.70  5022.6 1805.20
  5027.2 1806.51  5041.4 1807.72  5106.9 1809.08  5162.1 1809.72  5169.8 1810.27
  5190.6 1809.90  5233.2 1810.36  5248.6 1810.46  5409.8 1810.68  5429.8 1810.55
#Mann=9,-1,0
  3825.2    0.07       0  3826.6   0.035       0  4028.2    0.07       0
  5018.6    0.07       0  5022.6    0.07       0  5106.9   0.035       0
  5233.2    0.07       0  5248.6   0.035       0  5409.8    0.07       0
Bank Sta=5018.6,5022.6
Exp/Cntr=0.3,0.1

Type RM Length L Ch R = 1,5446,568,568,568
BEGIN DESCRIPTION:
Clear Fork Trib10 6.0
END DESCRIPTION:
XS GIS Cut Line= 3
      1446250.40      6931594.44      1447105.00      6930838.00
      1447456.43      6930171.92
#Sta/Elev= 30
  3863.5 1812.95  4009.6 1812.01  4176.3 1810.93  4239.9 1810.05  4353.2 1809.58
  4374.6 1809.26  4388.8 1809.57  4430.6 1808.84  4537.4 1808.08  4607.9 1807.97
  4615.4 1807.29  4671.5 1806.94  4685.7 1807.21  4707.4 1806.66  4728.3 1806.88
  4813.7 1805.81  4905.7 1805.42  4912.4 1805.01  5027.4 1803.66  5035.0 1803.47
  5038.6 1802.40  5038.9 1801.90  5042.4 1801.90  5042.7 1802.40  5050.0 1802.81
  5057.0 1804.30  5062.7 1804.82  5079.0 1805.13  5381.7 1808.68  5757.9 1809.70
#Mann=5,-1,0
  3863.5    0.07       0  4009.6   0.035       0  4353.2    0.07       0
  5038.6    0.07       0  5042.7    0.07       0
Bank Sta=5038.6,5042.7
Exp/Cntr=0.3,0.1

Type RM Length L Ch R = 1,4878,975,975,975
BEGIN DESCRIPTION:
Mapping XS 6d6bf5ee
END DESCRIPTION:
XS GIS Cut Line= 3
      1446884.09      6931663.88      1447391.90      6931403.46
      1447791.20      6930431.26
#Sta/Elev= 30
  4145.2 1807.08  4299.2 1806.07  4359.8 1806.19  4460.9 1805.25  4515.6 1805.24
  4528.3 1804.83  4582.2 1804.85  4685.7 1803.49  4708.1 1803.59  4761.6 1802.43
  4775.9 1802.52  4797.5 1801.61  4868.3 1802.77  4921.6 1803.03  4975.0 1802.13
  4996.9 1800.37  4997.1 1799.87  5000.7 1799.87  5001.0 1800.37  5004.4 1802.15
  5013.7 1802.83  5057.7 1802.75  5105.6 1803.41  5197.5 1803.42  5302.5 1804.17
  5391.9 1804.85  5586.6 1806.36  5609.7 1806.87  5705.6 1807.42  5766.9 1807.29
#Mann=5,-1,0
  4145.2    0.07       0  4996.9    0.07       0  5001.0    0.07       0
  5302.5    0.16       0  5391.9    0.07       0
Bank Sta=4996.9,5001
Exp/Cntr=0.3,0.1

Type RM Length L Ch R = 1,3903,640,640,640
BEGIN DESCRIPTION:
Mapping XS 81ff211a
END DESCRIPTION:
XS GIS Cut Line= 5
      1447266.07      6931676.89      1447904.06      6931581.41
      1448225.25      6931257.72      1448495.06      6930928.06
      1449245.51      6930248.51
#Sta/Elev= 30
  3898.9 1804.99  3945.9 1804.91  4102.5 1804.44  4484.3 1803.33  4709.7 1800.92
  4759.2 1799.76  4879.4 1798.73  4928.9 1798.97  4994.2 1797.17  4994.4 1796.67
  4998.1 1796.67  4998.4 1797.17  5049.9 1798.96  5091.5 1798.37  5113.7 1798.96
  5120.2 1798.49  5155.4 1799.35  5192.0 1799.35  5206.3 1800.15  5283.9 1799.95
  5291.0 1800.71  5305.4 1800.24  5319.8 1800.90  5375.7 1801.30  5383.6 1800.72
  5412.3 1801.35  5560.7 1801.27  5690.6 1801.96  6119.8 1805.30  6438.4 1805.14
#Mann=7,-1,0
  3898.9    0.07       0  3945.9   0.045       0  4102.5    0.07       0
  4994.2    0.07       0  4998.4    0.07       0  5560.7    0.16       0
  5690.6    0.07       0
Bank Sta=4994.2,4998.4
Exp/Cntr=0.3,0.1

Type RM Length L Ch R = 1,3263,65,65,65
BEGIN DESCRIPTION:
Mapping XS 37ba09be
END DESCRIPTION:
XS GIS Cut Line= 6
      1447183.61      6931763.70      1448073.33      6931659.54
      1448199.20      6931776.73      1448355.45      6931824.47
      1448529.06      6931438.18      1449454.99      6930577.25
#Sta/Elev= 30
  3579.7 1805.13  3733.2 1804.76  3873.7 1804.11  4272.2 1803.38  4478.9 1800.99
  4497.8 1805.92  4527.3 1801.58  4532.5 1802.65  4564.9 1798.95  4595.2 1798.29
  4648.6 1799.63  4666.1 1802.61  4681.7 1799.42  4687.1 1802.57  4704.7 1799.15
  4710.2 1802.32  4727.8 1799.00  4733.3 1800.71  4750.9 1798.89  4756.3 1800.39
  4861.1 1796.83  4866.8 1797.89  4941.9 1796.37  4985.6 1797.34  5002.3 1795.49
  5002.6 1794.99  5006.5 1795.49  5009.5 1797.52  5269.2 1798.92  6529.1 1801.86
#Mann=5,-1,0
  3579.7    0.07       0  3733.2   0.045       0  3873.7    0.07       0
  5002.3    0.07       0  5006.5    0.07       0
Bank Sta=5002.3,5006.5
Exp/Cntr=0.3,0.1

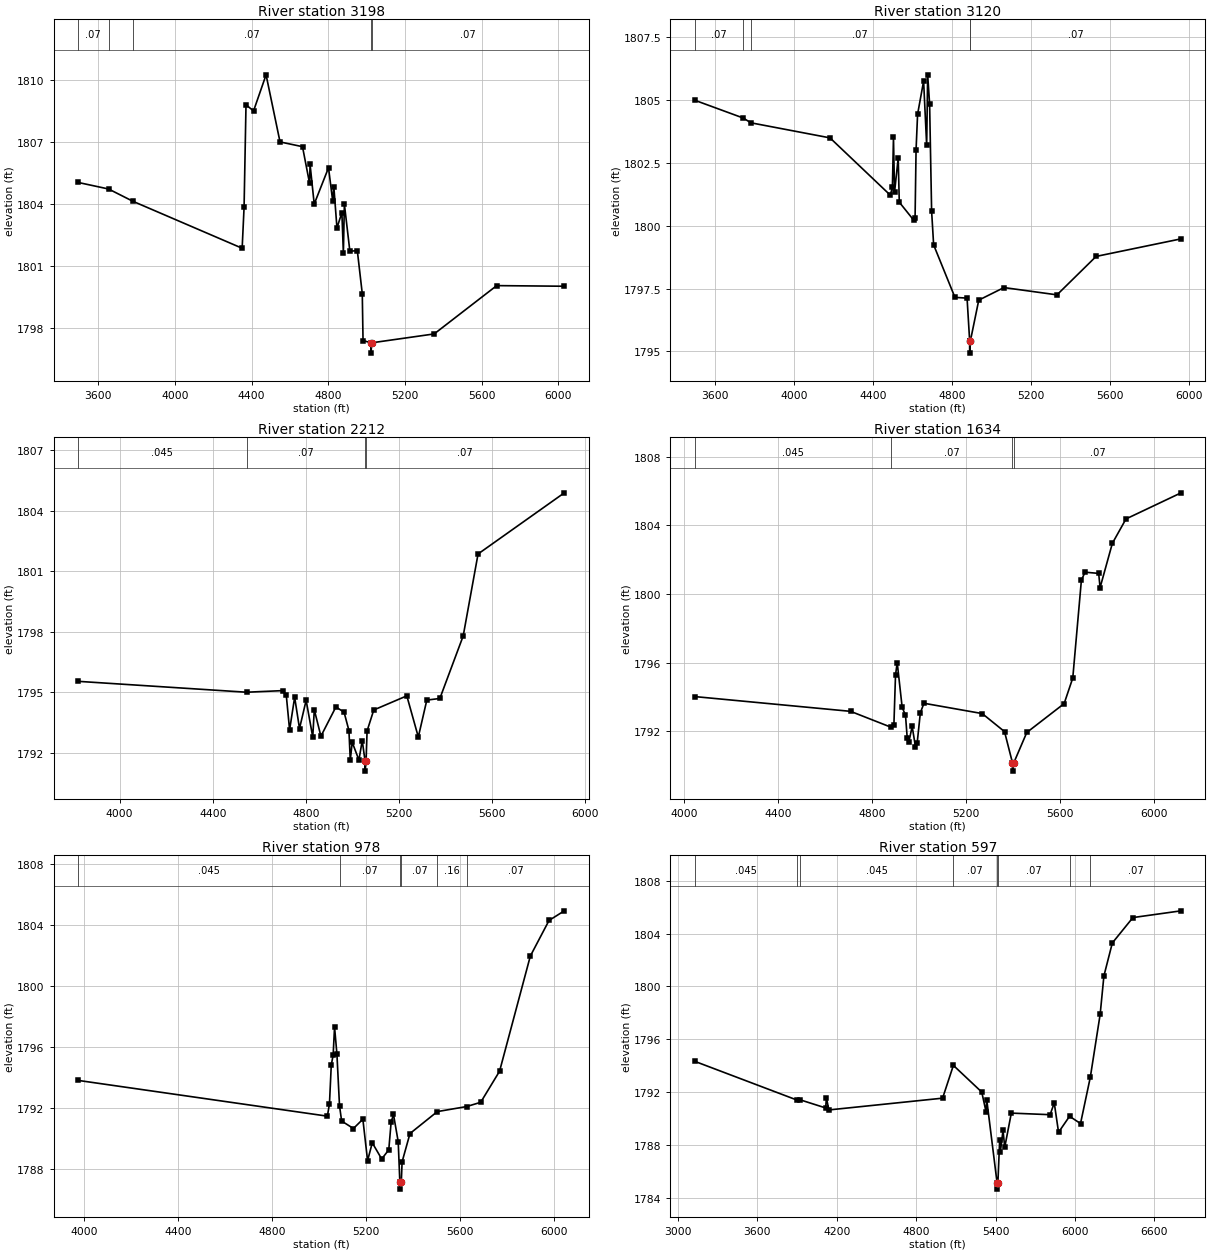
Type RM Length L Ch R = 1,3198,78,78,78
BEGIN DESCRIPTION:
Mapping XS f2cdff20
END DESCRIPTION:
XS GIS Cut Line= 6
      1447192.24      6931794.09      1448077.67      6931702.94
      1448108.05      6931789.75      1448381.49      6931854.85
      1448601.24      6931458.77      1449219.16      6930934.71
#Sta/Elev= 30
  3493.1 1805.05  3653.3 1804.73  3781.4 1804.13  4350.4 1801.86  4360.4 1803.84
  4370.5 1808.81  4409.8 1808.51  4475.2 1810.26  4548.0 1807.01  4665.3 1806.78
  4702.3 1805.00  4704.8 1805.92  4726.4 1804.00  4801.1 1805.76  4823.1 1804.13
  4828.7 1804.85  4845.1 1802.84  4870.8 1803.59  4878.6 1801.62  4883.8 1804.00
  4912.4 1801.72  4951.4 1801.74  4977.2 1799.66  4981.2 1797.39  5022.4 1797.28
  5022.7 1796.78  5026.6 1797.28  5352.4 1797.71  5678.7 1800.05  6031.6 1800.02
#Mann=5,-1,0
  3493.1    0.07       0  3653.3   0.045       0  3781.4    0.07       0
  5022.4    0.07       0  5026.6    0.07       0
Bank Sta=5022.4,5026.6
Exp/Cntr=0.3,0.1

Type RM Length L Ch R = 1,3120,908,908,908
BEGIN DESCRIPTION:
Mapping XS 207c1ca6
END DESCRIPTION:
XS GIS Cut Line= 6
      1447200.89      6931846.17      1447986.52      6931789.75
      1448272.98      6931906.93      1448442.25      6931876.55
      1448550.76      6931655.20      1449231.10      6931005.19
#Sta/Elev= 30
  3495.6 1805.00  3741.9 1804.29  3780.5 1804.10  4181.5 1803.50  4486.9 1801.22
  4497.7 1801.53  4503.1 1803.52  4508.5 1801.34  4527.1 1802.70  4532.5 1800.94
  4605.0 1800.23  4612.5 1800.29  4617.6 1803.03  4625.3 1804.44  4655.8 1805.76
  4671.3 1803.20  4676.4 1806.01  4686.2 1804.85  4696.4 1800.58  4706.6 1799.24
  4814.5 1797.15  4876.0 1797.12  4889.0 1795.43  4889.2 1794.93  4893.2 1795.43
  4935.2 1797.04  5063.0 1797.54  5331.6 1797.25  5529.7 1798.78  5960.4 1799.48
#Mann=5,-1,0
  3495.6    0.07       0  3741.9   0.045       0  3780.5    0.07       0
  4889.0    0.07       0  4893.2    0.07       0
Bank Sta=4889,4893.2
Exp/Cntr=0.3,0.1

Type RM Length L Ch R = 1,2212,578,578,578
BEGIN DESCRIPTION:
Mapping XS b5db07cb
END DESCRIPTION:
XS GIS Cut Line= 3
      1448316.41      6932814.02      1449097.63      6931941.66
      1449683.55      6931234.22
#Sta/Elev= 30
  3820.6 1795.55  4545.1 1795.01  4701.7 1795.09  4715.9 1794.85  4730.1 1793.14
  4751.8 1794.76  4772.7 1793.21  4801.1 1794.61  4829.5 1792.79  4836.2 1794.14
  4864.6 1792.83  4929.0 1794.28  4964.1 1794.02  4985.0 1793.11  4990.7 1791.64
  4999.1 1792.53  5027.8 1791.65  5042.1 1792.61  5054.3 1791.60  5054.6 1791.10
  5058.6 1791.60  5062.9 1793.09  5091.6 1794.13  5233.6 1794.83  5283.0 1792.79
  5319.5 1794.62  5375.5 1794.70  5475.8 1797.80  5539.6 1801.86  5910.2 1804.89
#Mann=4,-1,0
  3820.6   0.045       0  4545.1    0.07       0  5054.3    0.07       0
  5058.6    0.07       0
Bank Sta=5054.3,5058.6
Exp/Cntr=0.3,0.1

Type RM Length L Ch R = 1,1634,656,656,656
BEGIN DESCRIPTION:
Mapping XS df9e761d
END DESCRIPTION:
XS GIS Cut Line= 3
      1448754.73      6933035.42      1449449.20      6932380.02
      1450030.41      6931430.13
#Sta/Elev= 30
  4046.4 1794.03  4709.6 1793.17  4880.7 1792.25  4893.7 1792.37  4900.6 1795.28
  4907.8 1796.01  4928.9 1793.40  4943.0 1792.95  4950.3 1791.63  4957.2 1791.38
  4971.4 1792.29  4985.5 1791.11  4992.8 1791.34  5006.2 1793.09  5021.6 1793.64
  5269.3 1793.04  5364.1 1791.99  5397.6 1790.19  5398.1 1789.69  5404.0 1790.19
  5458.8 1791.94  5617.6 1793.62  5654.3 1795.11  5691.0 1800.81  5706.5 1801.27
  5764.5 1801.20  5770.4 1800.37  5822.6 1802.95  5880.6 1804.37  6114.9 1805.89
#Mann=4,-1,0
  4046.4   0.045       0  4880.7    0.07       0  5397.6    0.07       0
  5404.0    0.07       0
Bank Sta=5397.6,5404
Exp/Cntr=0.3,0.1

Type RM Length L Ch R = 1,978,381,381,381
BEGIN DESCRIPTION:
Mapping XS 7647ecc5
END DESCRIPTION:
XS GIS Cut Line= 4
      1449431.84      6933538.87      1449831.14      6932822.73
      1449952.67      6932584.02      1450043.81      6931603.15
#Sta/Elev= 30
  3972.7 1793.79  5035.9 1791.44  5044.8 1792.25  5052.5 1794.80  5060.5 1795.45
  5066.5 1797.29  5076.6 1795.51  5087.6 1792.12  5096.7 1791.12  5146.9 1790.63
  5187.1 1791.24  5207.2 1788.52  5227.2 1789.69  5267.4 1788.63  5297.5 1789.23
  5307.6 1791.05  5317.6 1791.55  5337.7 1789.77  5344.6 1787.15  5345.1 1786.65
  5351.0 1787.15  5354.3 1788.44  5387.9 1790.30  5504.4 1791.74  5629.1 1792.07
  5689.2 1792.35  5769.6 1794.39  5900.7 1801.95  5980.5 1804.29  6045.6 1804.92
#Mann=6,-1,0
  3972.7   0.045       0  5087.6    0.07       0  5344.6   0.045       0
  5351.0    0.07       0  5504.4    0.16       0  5629.1    0.07       0
Bank Sta=5344.6,5351
Exp/Cntr=0.3,0.1

Type RM Length L Ch R = 1,597,0,0,0
BEGIN DESCRIPTION:
Clear Fork Trib10 1.0
END DESCRIPTION:
XS GIS Cut Line= 5
      1449125.26      6933605.59      1449894.78      6933736.80
      1450281.94      6932714.15      1450584.18      6931738.40
      1450029.06      6931189.02
#Sta/Elev= 30
  3125.9 1794.34  3901.3 1791.40  3921.8 1791.43  4116.4 1790.81  4121.7 1791.58
  4140.5 1790.66  5000.0 1791.55  5081.5 1794.03  5296.0 1792.01  5328.6 1790.51
  5333.8 1791.42  5411.5 1785.17  5412.0 1784.67  5418.0 1785.17  5431.6 1788.42
  5436.9 1787.50  5456.6 1789.12  5469.5 1787.83  5519.4 1790.42  5812.5 1790.30
  5843.9 1791.19  5876.4 1788.97  5959.6 1790.18  6042.4 1789.63  6116.7 1793.15
  6190.9 1797.90  6219.2 1800.80  6282.8 1803.29  6438.4 1805.21  6802.5 1805.72
#Mann=8,-1,0
  3125.9   0.045       0  3901.3    0.05       0  3921.8   0.045       0
  5081.5    0.07       0  5411.5   0.045       0  5418.0    0.07       0
  5959.6    0.16       0  6116.7    0.07       0
Bank Sta=5411.5,5418
Exp/Cntr=0.3,0.1

Chan Stop Cuts=-1