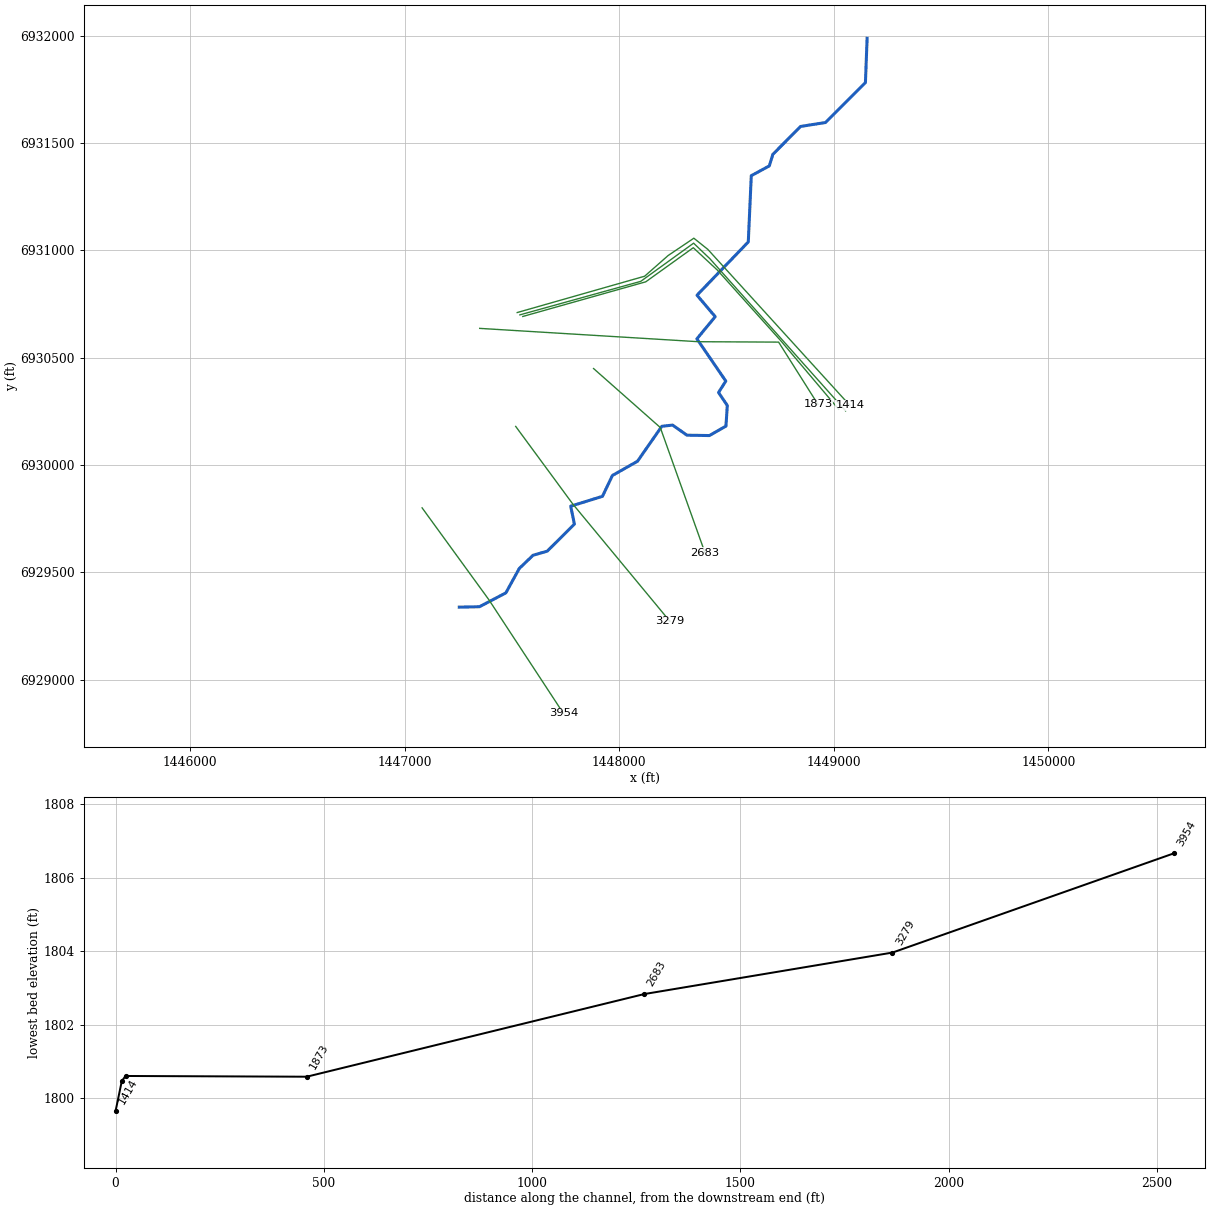
--- Clear Fork Trib10_1.prj (project) ---

Proj Title=Clear Fork Trib10_1 Base Level Engineering
Current Plan=p01
Default Exp/Contr=0.3,0.1
English Units
Geom File=g01
Flow File=f01
Plan File=p01
BEGIN DESCRIPTION:
Clear Fork Trib10_1
END DESCRIPTION:

--- Clear Fork Trib10_1.p01 (plan) ---

Plan Title=Multiple Run
Short Identifier=Multiple
Geom File=g01
Flow File=f01
Subcritical Flow
K Sum by GR= 0
Std Step Tol= 0.01
Critical Tol= 0.01
Num of Std Step Trials= 20
Max Error Tol= 0.3
Flow Tol Ratio= 0.001
Split Flow NTrial= 30
Split Flow Tol= 0.02
Split Flow Ratio= 0.02
Log Output Level= 0
Friction Slope Method= 1
Unsteady Friction Slope Method= 2
Unsteady Bridges Friction Slope Method= 1
Parabolic Critical Depth
Global Vel Dist=  1 , 1 , 1
Global Log Level= 0
CheckData=True
Encroach Param= -1, 0, 0, 0
BEGIN DESCRIPTION:
Multiple Run
END DESCRIPTION:

--- Clear Fork Trib10_1.f01 (steady flow) ---

Flow Title=Multiple
Number of Profiles=7
Profile Names=10-year,25-year,50-year,1pct_min,100-year,1pct_plu,500-year
River Rch & RM= Clear Fork Trib1,Reach-1,3954
     195     264     319     191     382     762     554
Boundary for River Rch & Prof#=Clear Fork Trib1,Reach-1,1
Up Type=0
Dn Type=3
Dn Slope=0.005
Boundary for River Rch & Prof#=Clear Fork Trib1,Reach-1,2
Up Type=0
Dn Type=3
Dn Slope=0.005
Boundary for River Rch & Prof#=Clear Fork Trib1,Reach-1,3
Up Type=0
Dn Type=3
Dn Slope=0.005
Boundary for River Rch & Prof#=Clear Fork Trib1,Reach-1,4
Up Type=0
Dn Type=3
Dn Slope=0.005
Boundary for River Rch & Prof#=Clear Fork Trib1,Reach-1,5
Up Type=0
Dn Type=3
Dn Slope=0.005
Boundary for River Rch & Prof#=Clear Fork Trib1,Reach-1,6
Up Type=0
Dn Type=3
Dn Slope=0.005
Boundary for River Rch & Prof#=Clear Fork Trib1,Reach-1,7
Up Type=0
Dn Type=3
Dn Slope=0.005

--- Clear Fork Trib10_1.g01 (geometry) ---

Geom Title=Existing Conditions

River Reach=Clear Fork Trib1,Reach-1
Reach XY= 30
      1447255.00      6929338.00      1447349.14      6929340.07
      1447472.05      6929404.49      1447534.59      6929518.23
      1447598.93      6929579.85      1447664.68      6929598.78
      1447791.35      6929724.67      1447774.17      6929808.48
      1447922.13      6929854.31      1447968.49      6929951.55
      1448085.23      6930017.59      1448198.66      6930180.64
      1448248.83      6930186.23      1448315.50      6930139.23
      1448420.25      6930137.44      1448497.38      6930181.50
      1448503.75      6930277.51      1448462.80      6930338.10
      1448496.76      6930391.23      1448362.11      6930588.00
      1448447.36      6930691.33      1448362.61      6930791.33
      1448601.46      6931039.46      1448615.40      6931348.10
      1448699.35      6931393.64      1448715.89      6931447.42
      1448845.21      6931577.48      1448961.17      6931595.86
      1449147.19      6931781.81      1449155.00      6931988.00

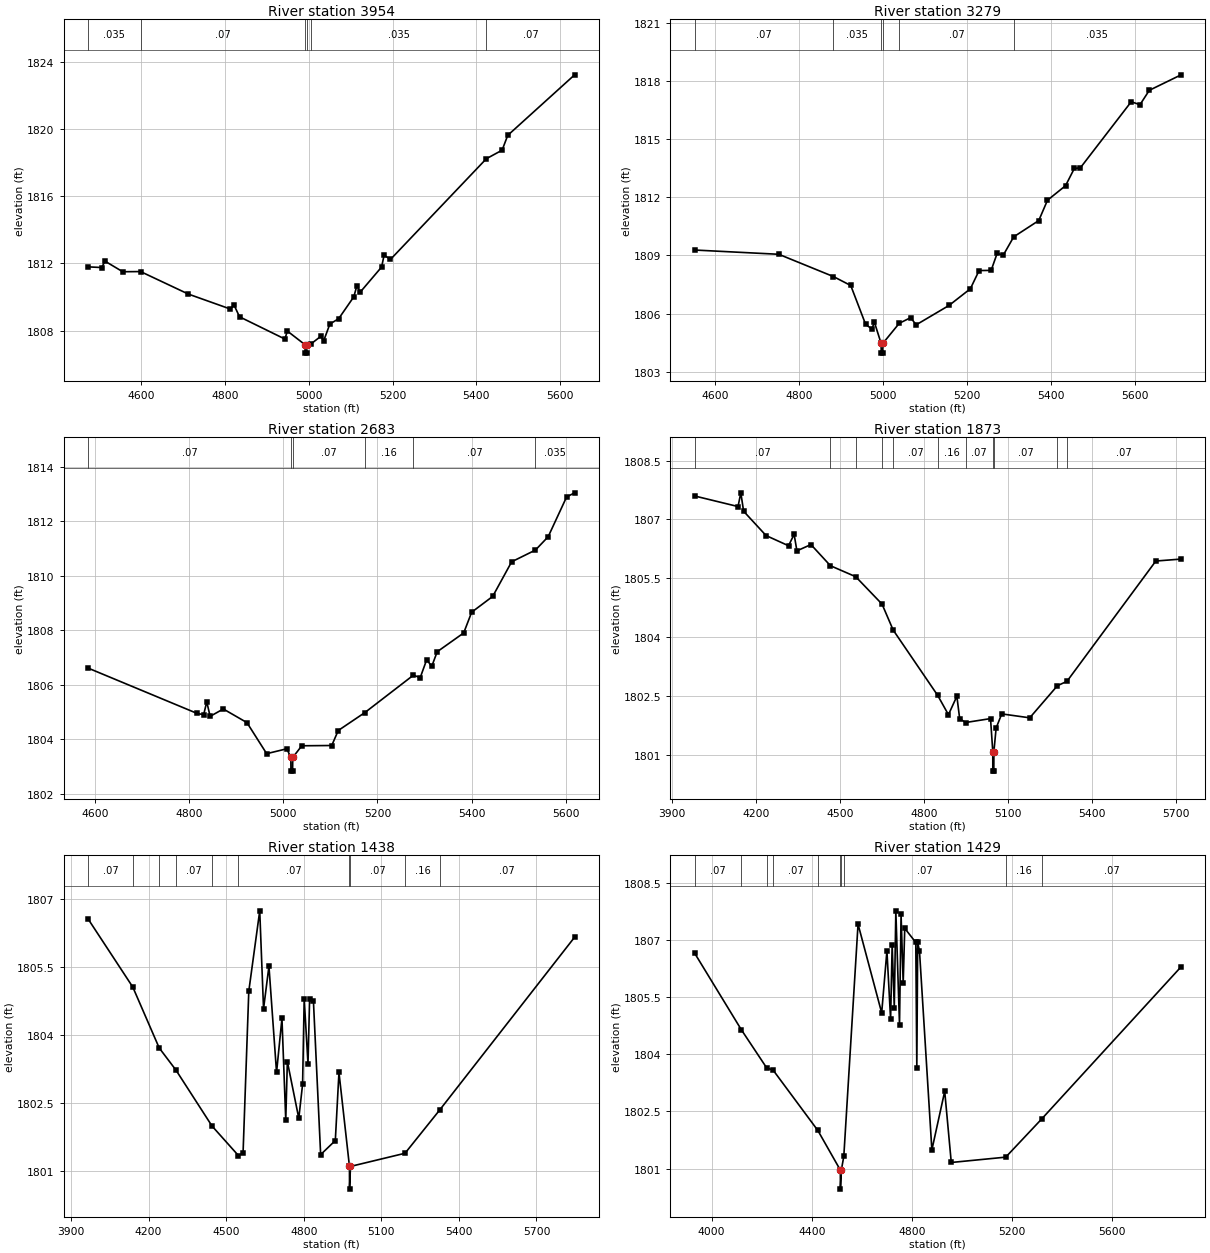
Type RM Length L Ch R = 1,3954,675,675,675
BEGIN DESCRIPTION:
Clear Fork Trib10_1 5.0
END DESCRIPTION:
XS GIS Cut Line= 3
      1447081.85      6929800.59      1447391.96      6929373.99
      1447740.11      6928843.18
#Sta/Elev= 30
  4472.6 1811.79  4505.1 1811.75  4512.9 1812.13  4555.3 1811.50  4597.9 1811.51
  4712.2 1810.17  4812.7 1809.28  4821.2 1809.52  4834.3 1808.82  4942.5 1807.50
  4948.7 1807.97  4990.8 1807.16  4991.0 1806.66  4994.5 1806.66  4994.8 1807.16
  5004.6 1807.20  5029.0 1807.67  5035.0 1807.37  5050.1 1808.39  5071.2 1808.71
  5107.3 1810.01  5114.8 1810.68  5122.4 1810.28  5173.7 1811.78  5179.7 1812.49
  5194.8 1812.23  5423.9 1818.22  5461.6 1818.73  5475.0 1819.61  5634.8 1823.21
#Mann=6,-1,0
  4472.6   0.035       0  4597.9    0.07       0  4990.8    0.07       0
  4994.8    0.07       0  5004.6   0.035       0  5423.9    0.07       0
Bank Sta=4990.8,4994.8
Exp/Cntr=0.3,0.1

Type RM Length L Ch R = 1,3279,596,596,596
BEGIN DESCRIPTION:
Clear Fork Trib10_1 4.0
END DESCRIPTION:
XS GIS Cut Line= 3
      1447517.94      6930179.97      1447783.95      6929818.37
      1448236.16      6929272.18
#Sta/Elev= 30
  4551.1 1809.28  4751.5 1809.06  4881.6 1807.91  4922.8 1807.45  4958.3 1805.44
  4972.9 1805.21  4979.2 1805.55  4995.1 1804.46  4995.4 1803.96  4998.9 1803.96
  4999.1 1804.46  5038.3 1805.50  5065.4 1805.79  5078.5 1805.42  5156.7 1806.42
  5207.5 1807.28  5228.3 1808.22  5257.0 1808.23  5271.3 1809.11  5285.7 1809.01
  5310.7 1809.96  5370.3 1810.80  5391.1 1811.85  5434.1 1812.60  5455.0 1813.49
  5469.3 1813.52  5590.4 1816.93  5611.3 1816.78  5633.4 1817.52  5709.1 1818.32
#Mann=6,-1,0
  4551.1    0.07       0  4881.6   0.035       0  4995.1   0.035       0
  4999.1   0.035       0  5038.3    0.07       0  5310.7   0.035       0
Bank Sta=4995.1,4999.1
Exp/Cntr=0.3,0.1

Type RM Length L Ch R = 1,2683,810,810,810
BEGIN DESCRIPTION:
Clear Fork Trib10_1 3.0
END DESCRIPTION:
XS GIS Cut Line= 3
      1447880.69      6930449.64      1448191.43      6930175.02
      1448399.58      6929591.96
#Sta/Elev= 30
  4585.3 1806.61  4816.5 1804.95  4830.8 1804.90  4837.4 1805.37  4844.6 1804.84
  4872.6 1805.11  4922.8 1804.61  4964.7 1803.47  5007.5 1803.65  5016.1 1803.33
  5016.3 1802.83  5019.8 1802.83  5020.1 1803.33  5039.3 1803.76  5103.0 1803.77
  5116.8 1804.32  5173.5 1804.98  5276.5 1806.35  5291.0 1806.26  5304.8 1806.92
  5315.4 1806.67  5327.1 1807.21  5383.4 1807.90  5400.3 1808.66  5445.0 1809.24
  5485.3 1810.51  5535.8 1810.94  5562.9 1811.43  5602.1 1812.89  5619.1 1813.04
#Mann=6,-1,0
  4585.3    0.07       0  5016.1    0.07       0  5020.1    0.07       0
  5173.5    0.16       0  5276.5    0.07       0  5535.8   0.035       0
Bank Sta=5016.1,5020.1
Exp/Cntr=0.3,0.1

Type RM Length L Ch R = 1,1873,435,435,435
BEGIN DESCRIPTION:
Clear Fork Trib10_1 2.0
END DESCRIPTION:
XS GIS Cut Line= 4
      1447350.24      6930636.78      1448368.44      6930574.68
      1448742.82      6930572.77      1448925.90      6930283.17
#Sta/Elev= 30
  3979.9 1807.60  4135.0 1807.33  4145.0 1807.68  4155.0 1807.21  4235.1 1806.59
  4315.3 1806.33  4335.3 1806.62  4345.3 1806.20  4395.4 1806.36  4465.0 1805.82
  4555.3 1805.54  4649.3 1804.84  4688.9 1804.18  4848.1 1802.51  4886.3 1802.02
  4916.4 1802.49  4926.4 1801.92  4947.5 1801.82  5036.6 1801.92  5044.6 1801.08
  5044.8 1800.58  5048.3 1800.58  5048.6 1801.08  5056.6 1801.68  5076.6 1802.04
  5176.6 1801.94  5275.5 1802.76  5309.4 1802.87  5626.8 1805.94  5717.0 1805.99
#Mann=11,-1,0
  3979.9    0.07       0  4465.0   0.035       0  4555.3    0.07       0
  4649.3   0.035       0  4688.9    0.07       0  4848.1    0.16       0
  4947.5    0.07       0  5044.6    0.07       0  5048.6    0.07       0
  5275.5    0.16       0  5309.4    0.07       0
Bank Sta=5044.6,5048.6
Exp/Cntr=0.3,0.1

Type RM Length L Ch R = 1,1438,9,9,9
BEGIN DESCRIPTION:
Mapping XS c1b207f7
END DESCRIPTION:
XS GIS Cut Line= 6
      1447550.95      6930692.28      1448123.88      6930853.74
      1448345.24      6931012.59      1448457.22      6930908.42
      1448754.09      6930577.70      1449022.34      6930259.96
#Sta/Elev= 30
  3966.5 1806.55  4139.3 1805.05  4241.3 1803.71  4306.3 1803.22  4445.5 1801.99
  4547.5 1801.34  4565.5 1801.39  4587.7 1804.96  4630.0 1806.73  4644.7 1804.57
  4665.6 1805.51  4695.0 1803.17  4715.9 1804.36  4730.6 1802.12  4736.8 1803.41
  4781.0 1802.16  4795.7 1802.91  4801.9 1804.79  4816.6 1803.36  4822.8 1804.79
  4837.5 1804.75  4865.5 1801.36  4922.2 1801.67  4936.3 1803.17  4976.9 1801.10
  4977.1 1800.60  4980.9 1801.10  5191.7 1801.39  5326.7 1802.35  5847.4 1806.15
#Mann=10,-1,0
  3966.5    0.07       0  4139.3    0.16       0  4241.3   0.035       0
  4306.3    0.07       0  4445.5   0.035       0  4547.5    0.07       0
  4976.9    0.07       0  4980.9    0.07       0  5191.7    0.16       0
  5326.7    0.07       0
Bank Sta=4976.9,4980.9
Exp/Cntr=0.3,0.1

Type RM Length L Ch R = 1,1429,15,15,15
BEGIN DESCRIPTION:
Mapping XS b390807c
END DESCRIPTION:
XS GIS Cut Line= 5
      1447537.33      6930699.71      1448100.49      6930855.83
      1448346.65      6931033.73      1448423.04      6930960.81
      1449054.77      6930252.39
#Sta/Elev= 30
  3932.1 1806.66  4118.5 1804.65  4220.5 1803.64  4245.3 1803.59  4424.4 1802.00
  4514.2 1800.96  4514.5 1800.46  4518.2 1800.96  4528.0 1801.32  4584.9 1807.42
  4679.3 1805.09  4700.2 1806.72  4714.9 1804.92  4721.1 1806.88  4729.6 1805.23
  4735.8 1807.77  4750.5 1804.78  4756.7 1807.68  4765.2 1805.87  4771.4 1807.31
  4815.5 1806.94  4819.6 1803.64  4823.1 1806.94  4830.3 1806.71  4879.7 1801.49
  4931.0 1803.03  4957.2 1801.16  5174.7 1801.30  5319.3 1802.31  5875.0 1806.30
#Mann=10,-1,0
  3932.1    0.07       0  4118.5    0.16       0  4220.5   0.035       0
  4245.3    0.07       0  4424.4   0.035       0  4514.2    0.07       0
  4518.2   0.035       0  4528.0    0.07       0  5174.7    0.16       0
  5319.3    0.07       0
Bank Sta=4514.2,4518.2
Exp/Cntr=0.3,0.1

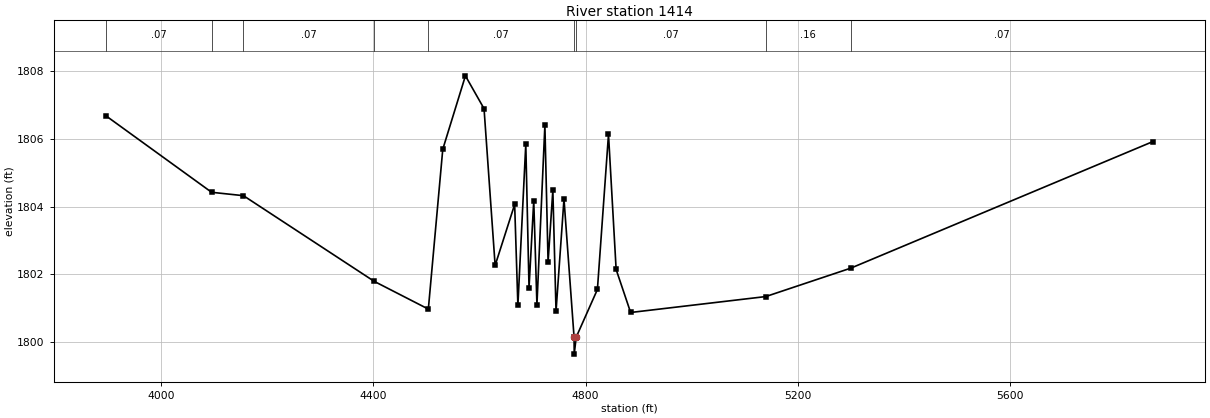
Type RM Length L Ch R = 1,1414,0,0,0
BEGIN DESCRIPTION:
Mapping XS 658488bd
END DESCRIPTION:
XS GIS Cut Line= 6
      1447524.89      6930710.50      1448118.67      6930879.78
      1448228.05      6930976.13      1448347.84      6931056.86
      1448412.95      6931004.78      1449074.40      6930278.22
#Sta/Elev= 30
  3895.9 1806.68  4095.2 1804.42  4155.2 1804.32  4401.6 1801.79  4503.7 1800.97
  4530.9 1805.69  4573.6 1807.86  4608.7 1806.89  4629.6 1802.26  4666.4 1804.06
  4672.5 1801.08  4687.4 1805.84  4693.5 1801.60  4702.4 1804.17  4708.4 1801.10
  4723.4 1806.40  4729.4 1802.36  4738.4 1804.48  4744.4 1800.91  4759.4 1804.22
  4778.4 1800.14  4778.7 1799.64  4782.4 1800.14  4822.4 1801.55  4843.3 1806.13
  4857.7 1802.14  4885.0 1800.87  5139.7 1801.34  5300.1 1802.18  5869.8 1805.92
#Mann=9,-1,0
  3895.9    0.07       0  4095.2    0.16       0  4155.2    0.07       0
  4401.6   0.035       0  4503.7    0.07       0  4778.4    0.07       0
  4782.4    0.07       0  5139.7    0.16       0  5300.1    0.07       0
Bank Sta=4778.4,4782.4
Exp/Cntr=0.3,0.1

Chan Stop Cuts=-1