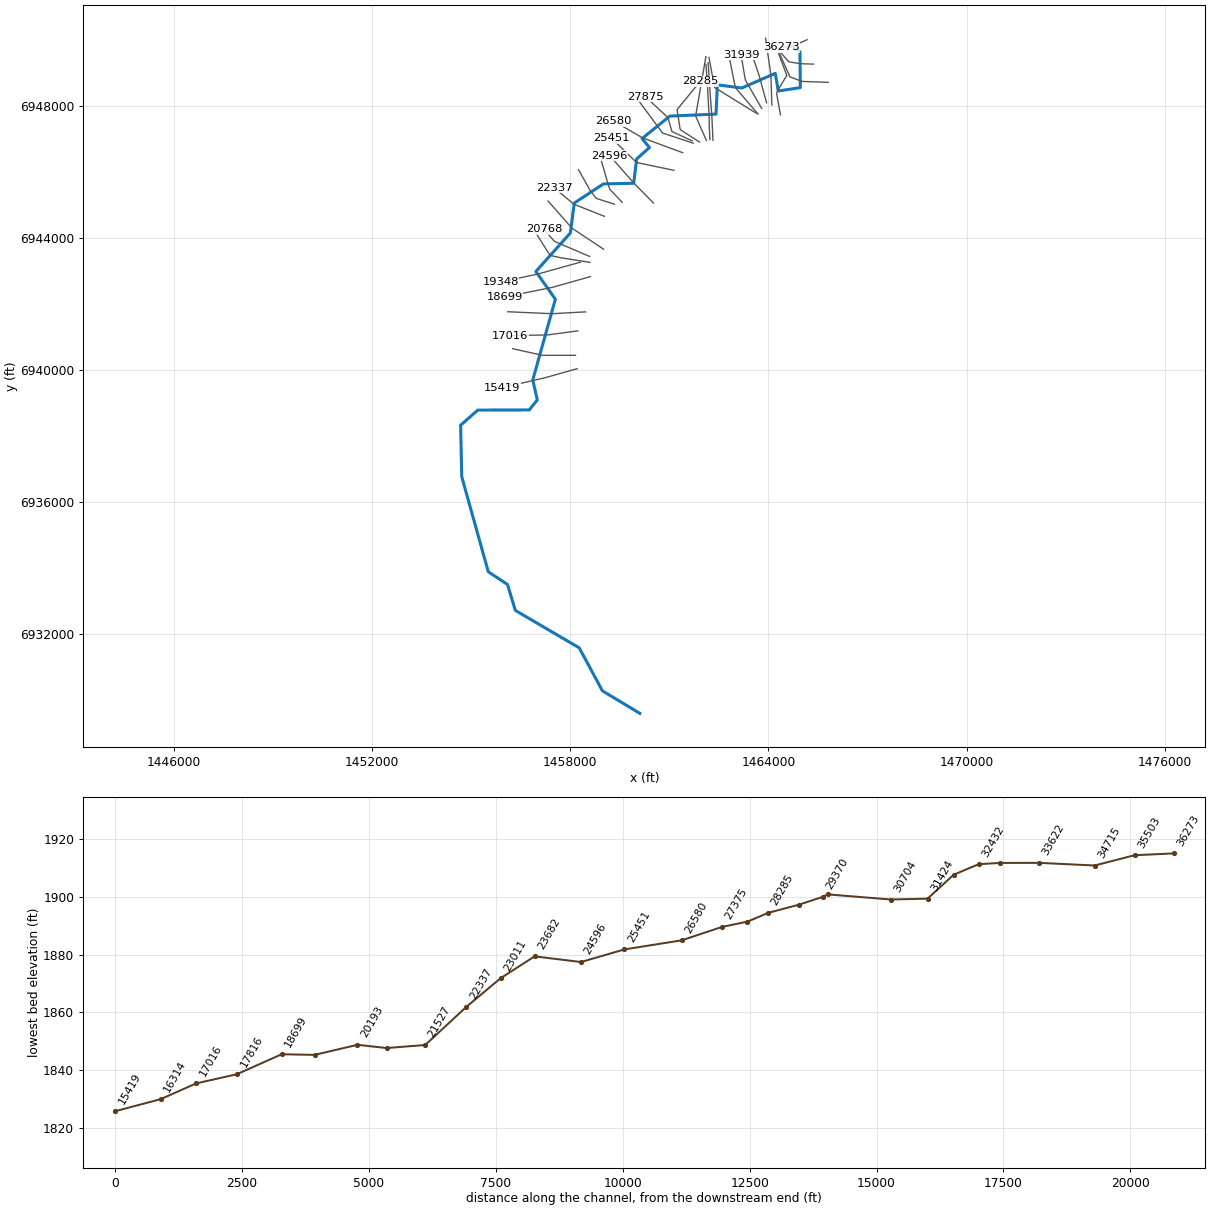
--- Clear Fork Trib11.prj (project) ---

Proj Title=Clear Fork Trib11 Base Level Engineering
Current Plan=p01
Default Exp/Contr=0.3,0.1
English Units
Geom File=g01
Flow File=f01
Plan File=p01
Y Axis Title=Elevation
X Axis Title(PF)=Main Channel Distance
X Axis Title(XS)=Station
BEGIN DESCRIPTION:
Clear Fork Trib11
END DESCRIPTION:
DSS Export Rating Curves= 0
DSS Export Rating Curve Sorted= 0
DSS Export Volume Flow Curves= 0
DXF OffsetX= 0
DXF OffsetY= 0
DXF ScaleX= 1
DXF ScaleY= 10

--- Clear Fork Trib11.p01 (plan) ---

Plan Title=Multiple Run
Short Identifier=Multiple
Geom File=g01
Flow File=f01
Subcritical Flow
K Sum by GR= 0
Std Step Tol= 0.01
Critical Tol= 0.01
Num of Std Step Trials= 20
Max Error Tol= 0.3
Flow Tol Ratio= 0.001
Split Flow NTrial= 30
Split Flow Tol= 0.02
Split Flow Ratio= 0.02
Log Output Level= 0
Friction Slope Method= 1
Unsteady Friction Slope Method= 2
Unsteady Bridges Friction Slope Method= 1
Parabolic Critical Depth
Global Vel Dist=  1 , 1 , 1
Global Log Level= 0
CheckData=True
Encroach Param= -1, 0, 0, 0
BEGIN DESCRIPTION:
Multiple Run
END DESCRIPTION:

--- Clear Fork Trib11.f01 (steady flow) ---

Flow Title=Multiple
Program Version=4.10
Number of Profiles= 7
Profile Names=10-year,25-year,50-year,1pct_min,100-year,1pct_plu,500-year
River Rch & RM=Clear Fork Trib1,Reach-1         ,36273
     189     255     307     184     368     734     533
River Rch & RM=Clear Fork Trib1,Reach-1         ,35503
     285     393     480     291     581    1159     863
River Rch & RM=Clear Fork Trib1,Reach-1         ,27375
     571     818    1028     641    1278    2550    2000
River Rch & RM=Clear Fork Trib1,Reach-1         ,20768
     577     828    1040     647    1291    2576    2018
River Rch & RM=Clear Fork Trib1,Reach-1         ,19348
     809    1178    1496     941    1877    3744    2991
River Rch & RM=Clear Fork Trib1,Reach-1         ,4172
    1065    1567    2004    1268    2529    5047    4083
Boundary for River Rch & Prof#=Clear Fork Trib1,Reach-1         , 1
Up Type= 0
Dn Type= 3
Dn Slope=0.00397
Boundary for River Rch & Prof#=Clear Fork Trib1,Reach-1         , 2
Up Type= 0
Dn Type= 3
Dn Slope=0.00397
Boundary for River Rch & Prof#=Clear Fork Trib1,Reach-1         , 3
Up Type= 0
Dn Type= 3
Dn Slope=0.00397
Boundary for River Rch & Prof#=Clear Fork Trib1,Reach-1         , 4
Up Type= 0
Dn Type= 3
Dn Slope=0.00397
Boundary for River Rch & Prof#=Clear Fork Trib1,Reach-1         , 5
Up Type= 0
Dn Type= 3
Dn Slope=0.00397
Boundary for River Rch & Prof#=Clear Fork Trib1,Reach-1         , 6
Up Type= 0
Dn Type= 3
Dn Slope=0.00397
Boundary for River Rch & Prof#=Clear Fork Trib1,Reach-1         , 7
Up Type= 0
Dn Type= 3
Dn Slope=0.00397
DSS Import GetInterval= 0
DSS Import GetPeak= 0
DSS Import FillOption= 0

--- Clear Fork Trib11.g01 (geometry) ---

Geom Title=Existing Conditions

River Reach=Clear Fork Trib1,Reach-1
Reach XY= 30
      1464655.00      6949838.00      1464953.04      6949632.35
      1464965.12      6948548.35      1464298.05      6948446.84
      1464205.11      6948980.69      1463194.55      6948538.53
      1462452.55      6948632.53      1462411.08      6947746.13
      1461011.05      6947686.43      1460171.18      6947004.70
      1460397.02      6946734.65      1460008.52      6946386.72
      1459918.80      6945651.19      1459001.67      6945630.38
      1458118.61      6945051.24      1458001.97      6944146.01
      1456955.72      6942977.29      1457547.44      6942138.00
      1456863.00      6939691.33      1456999.91      6939085.70
      1456757.25      6938782.07      1455198.76      6938778.79
      1454677.93      6938318.72      1454712.65      6936756.22
      1455516.23      6933877.98      1456097.36      6933494.45
      1456334.42      6932707.59      1458268.63      6931574.54
      1458971.43      6930271.24      1460105.00      6929588.00

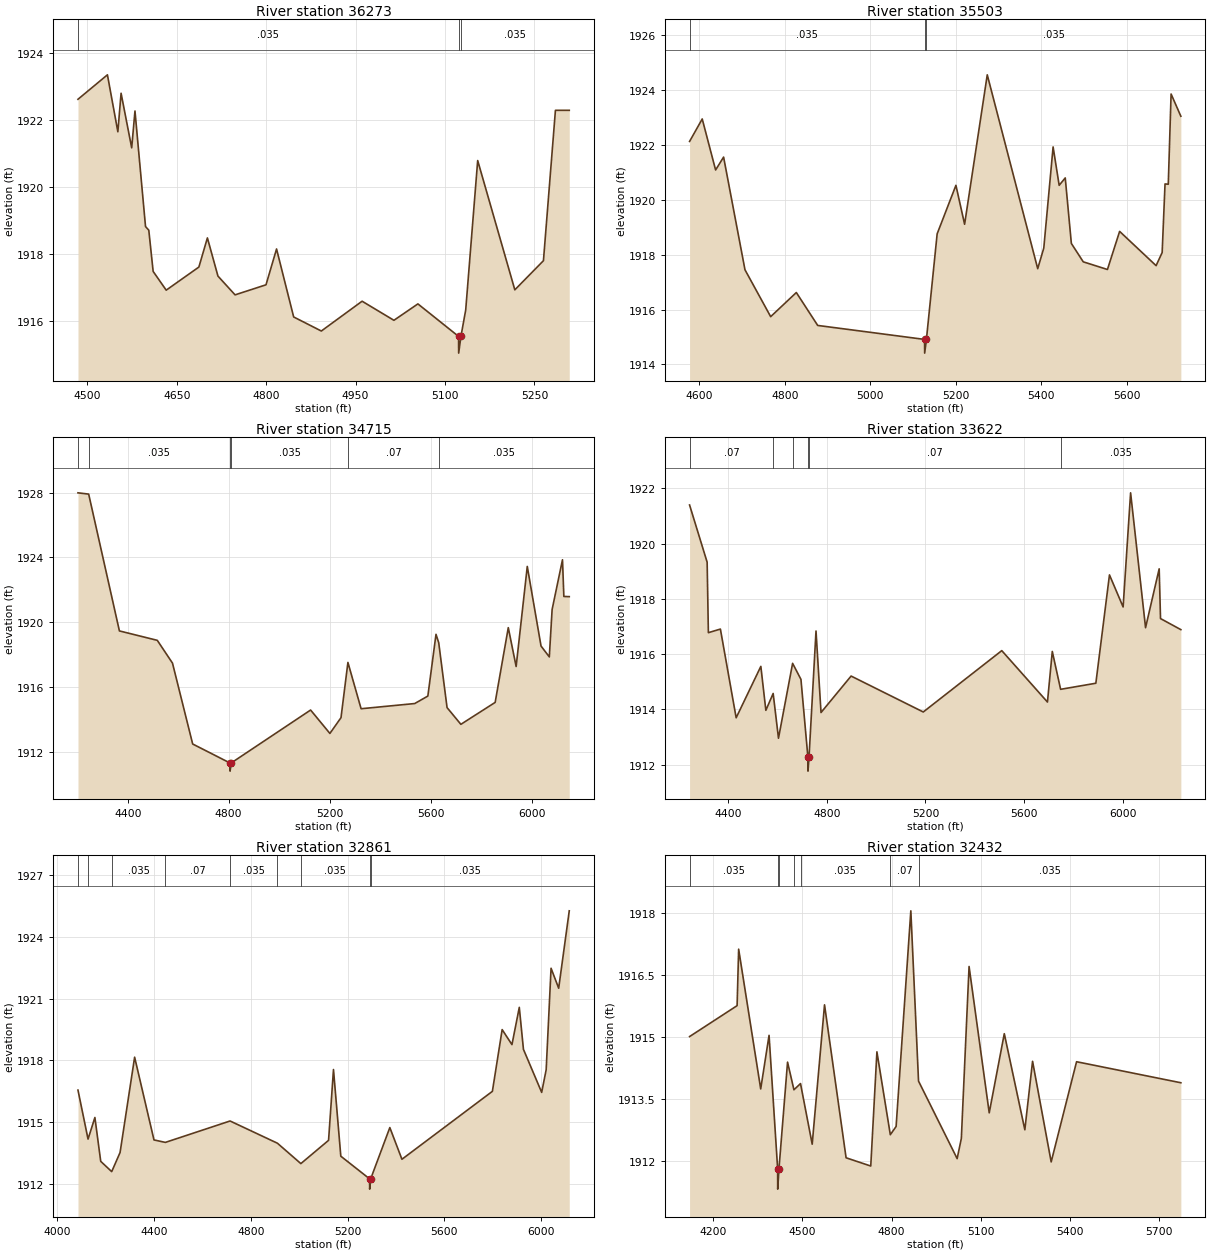
Type RM Length L Ch R = 1,36273,770,770,770
BEGIN DESCRIPTION:
Clear Fork Trib11 43.0
END DESCRIPTION:
XS GIS Cut Line= 3
      1465170.12      6950000.69      1464699.28      6949790.32
      1464391.89      6949765.38
#Sta/Elev= 30
  4484.3 1922.62  4533.7 1923.35  4551.2 1921.65  4556.6 1922.80  4574.4 1921.17
  4579.9 1922.27  4597.6 1918.82  4603.1 1918.71  4610.4 1917.48  4632.3 1916.92
  4687.1 1917.61  4701.4 1918.48  4719.1 1917.34  4747.8 1916.78  4799.7 1917.08
  4817.4 1918.15  4846.1 1916.12  4892.5 1915.70  4960.9 1916.59  5014.3 1916.02
  5054.5 1916.51  5122.7 1915.54  5122.9 1915.04  5126.7 1915.54  5134.7 1916.33
  5154.8 1920.79  5217.1 1916.93  5265.1 1917.80  5285.2 1922.29  5308.4 1922.29
#Mann=3,-1,0
  4484.3   0.035       0  5122.7   0.035       0  5126.7   0.035       0
Bank Sta=5122.7,5126.7
Exp/Cntr=0.3,0.1

Type RM Length L Ch R = 1,35503,788,788,788
BEGIN DESCRIPTION:
Mapping XS 13dd73ac
END DESCRIPTION:
XS GIS Cut Line= 4
      1465364.56      6949261.13      1464940.98      6949275.01
      1464614.59      6949334.04      1464354.17      6949629.19
#Sta/Elev= 30
  4577.0 1922.13  4606.6 1922.95  4637.9 1921.09  4656.6 1921.56  4706.6 1917.45
  4766.7 1915.74  4826.7 1916.62  4876.7 1915.42  5126.6 1914.91  5126.9 1914.41
  5131.0 1914.91  5156.1 1918.76  5200.0 1920.53  5220.3 1919.11  5273.3 1924.56
  5391.3 1917.49  5405.5 1918.24  5427.3 1921.93  5441.5 1920.53  5455.7 1920.80
  5470.0 1918.41  5497.8 1917.74  5554.4 1917.46  5582.9 1918.85  5668.2 1917.60
  5682.4 1918.08  5689.1 1920.58  5696.7 1920.57  5703.3 1923.86  5726.1 1923.05
#Mann=3,-1,0
  4577.0   0.035       0  5126.6   0.035       0  5131.0   0.035       0
Bank Sta=5126.6,5131
Exp/Cntr=0.3,0.1

Type RM Length L Ch R = 1,34715,1093,1093,1093
BEGIN DESCRIPTION:
Mapping XS e7cb6f23
END DESCRIPTION:
XS GIS Cut Line= 4
      1465809.04      6948709.04      1465013.90      6948736.82
      1464649.31      6948875.71      1464340.27      6949570.18
#Sta/Elev= 30
  4203.1 1927.98  4245.5 1927.90  4367.2 1919.48  4517.3 1918.90  4577.4 1917.50
  4657.4 1912.52  4805.3 1911.35  4805.6 1910.85  4809.8 1911.35  5124.5 1914.61
  5200.9 1913.17  5244.9 1914.14  5272.3 1917.54  5324.5 1914.69  5536.9 1915.01
  5588.9 1915.47  5621.2 1919.27  5632.0 1918.75  5665.0 1914.76  5719.7 1913.73
  5855.5 1915.08  5907.5 1919.68  5938.6 1917.29  5982.7 1923.45  6037.2 1918.55
  6070.0 1917.88  6081.1 1920.80  6122.2 1923.86  6127.6 1921.60  6149.0 1921.59
#Mann=6,-1,0
  4203.1    0.07       0  4245.5   0.035       0  4805.3   0.035       0
  4809.8   0.035       0  5272.3    0.07       0  5632.0   0.035       0
Bank Sta=4805.3,4809.8
Exp/Cntr=0.3,0.1

Type RM Length L Ch R = 1,33622,761,761,761
BEGIN DESCRIPTION:
Mapping XS 2190c10c
END DESCRIPTION:
XS GIS Cut Line= 5
      1464362.69      6947723.75      1464246.09      6948374.76
      1464278.01      6948463.53      1464555.56      6948917.38
      1464309.51      6949575.82
#Sta/Elev= 30
  4244.3 1921.40  4315.5 1919.33  4320.5 1916.78  4369.2 1916.91  4433.1 1913.70
  4533.1 1915.56  4553.4 1913.97  4583.0 1914.58  4604.6 1912.96  4661.8 1915.67
  4695.6 1915.09  4723.8 1912.27  4724.1 1911.77  4728.3 1912.27  4756.6 1916.84
  4776.9 1913.89  4898.8 1915.21  5191.2 1913.91  5509.3 1916.13  5694.4 1914.27
  5714.0 1916.10  5747.7 1914.73  5890.5 1914.95  5945.7 1918.87  6001.0 1917.71
  6031.3 1921.84  6091.9 1916.96  6147.1 1919.09  6152.5 1917.29  6234.9 1916.89
#Mann=6,-1,0
  4244.3    0.07       0  4583.0   0.035       0  4661.8    0.07       0
  4723.8    0.07       0  4728.3    0.07       0  5747.7   0.035       0
Bank Sta=4723.8,4728.3
Exp/Cntr=0.3,0.1

Type RM Length L Ch R = 1,32861,429,429,429
BEGIN DESCRIPTION:
Mapping XS 7d79cb20
END DESCRIPTION:
XS GIS Cut Line= 3
      1464102.27      6948024.07      1464072.92      6948938.21
      1463913.20      6950042.41
#Sta/Elev= 30
  4086.0 1916.55  4127.6 1914.17  4155.9 1915.22  4180.0 1913.09  4225.4 1912.59
  4260.0 1913.52  4320.1 1918.15  4400.1 1914.13  4447.1 1914.01  4714.6 1915.05
  4910.3 1913.97  5007.1 1912.98  5121.6 1914.11  5141.9 1917.55  5172.2 1913.34
  5291.1 1912.24  5291.5 1911.74  5295.7 1912.24  5374.8 1914.73  5424.8 1913.19
  5798.6 1916.49  5839.0 1919.49  5879.5 1918.76  5909.8 1920.57  5927.0 1918.53
  6002.3 1916.44  6020.9 1917.54  6041.1 1922.47  6072.6 1921.50  6116.3 1925.26
#Mann=9,-1,0
  4086.0   0.035       0  4127.6    0.07       0  4225.4   0.035       0
  4447.1    0.07       0  4714.6   0.035       0  4910.3    0.07       0
  5007.1   0.035       0  5291.1    0.07       0  5295.7   0.035       0
Bank Sta=5291.1,5295.7
Exp/Cntr=0.3,0.1

Type RM Length L Ch R = 1,32432,493,493,493
BEGIN DESCRIPTION:
Mapping XS a7046524
END DESCRIPTION:
XS GIS Cut Line= 3
      1463942.54      6948090.10      1463709.91      6948940.77
      1463459.95      6949669.81
#Sta/Elev= 30
  4120.5 1915.01  4280.4 1915.76  4285.6 1917.13  4359.8 1913.74  4387.9 1915.04
  4416.7 1911.81  4417.0 1911.31  4421.3 1911.81  4450.1 1914.39  4471.6 1913.72
  4493.7 1913.87  4533.0 1912.40  4574.5 1915.78  4647.0 1912.07  4730.0 1911.87
  4750.7 1914.64  4795.8 1912.63  4815.3 1912.83  4864.8 1918.06  4890.7 1913.93
  5020.6 1912.05  5034.7 1912.54  5060.7 1916.71  5128.5 1913.16  5179.2 1915.08
  5248.3 1912.75  5274.3 1914.41  5336.9 1911.97  5422.3 1914.40  5773.1 1913.89
#Mann=7,-1,0
  4120.5   0.035       0  4416.7   0.035       0  4421.3   0.035       0
  4471.6    0.07       0  4493.7   0.035       0  4795.8    0.07       0
  4890.7   0.035       0
Bank Sta=4416.7,4421.3
Exp/Cntr=0.3,0.1

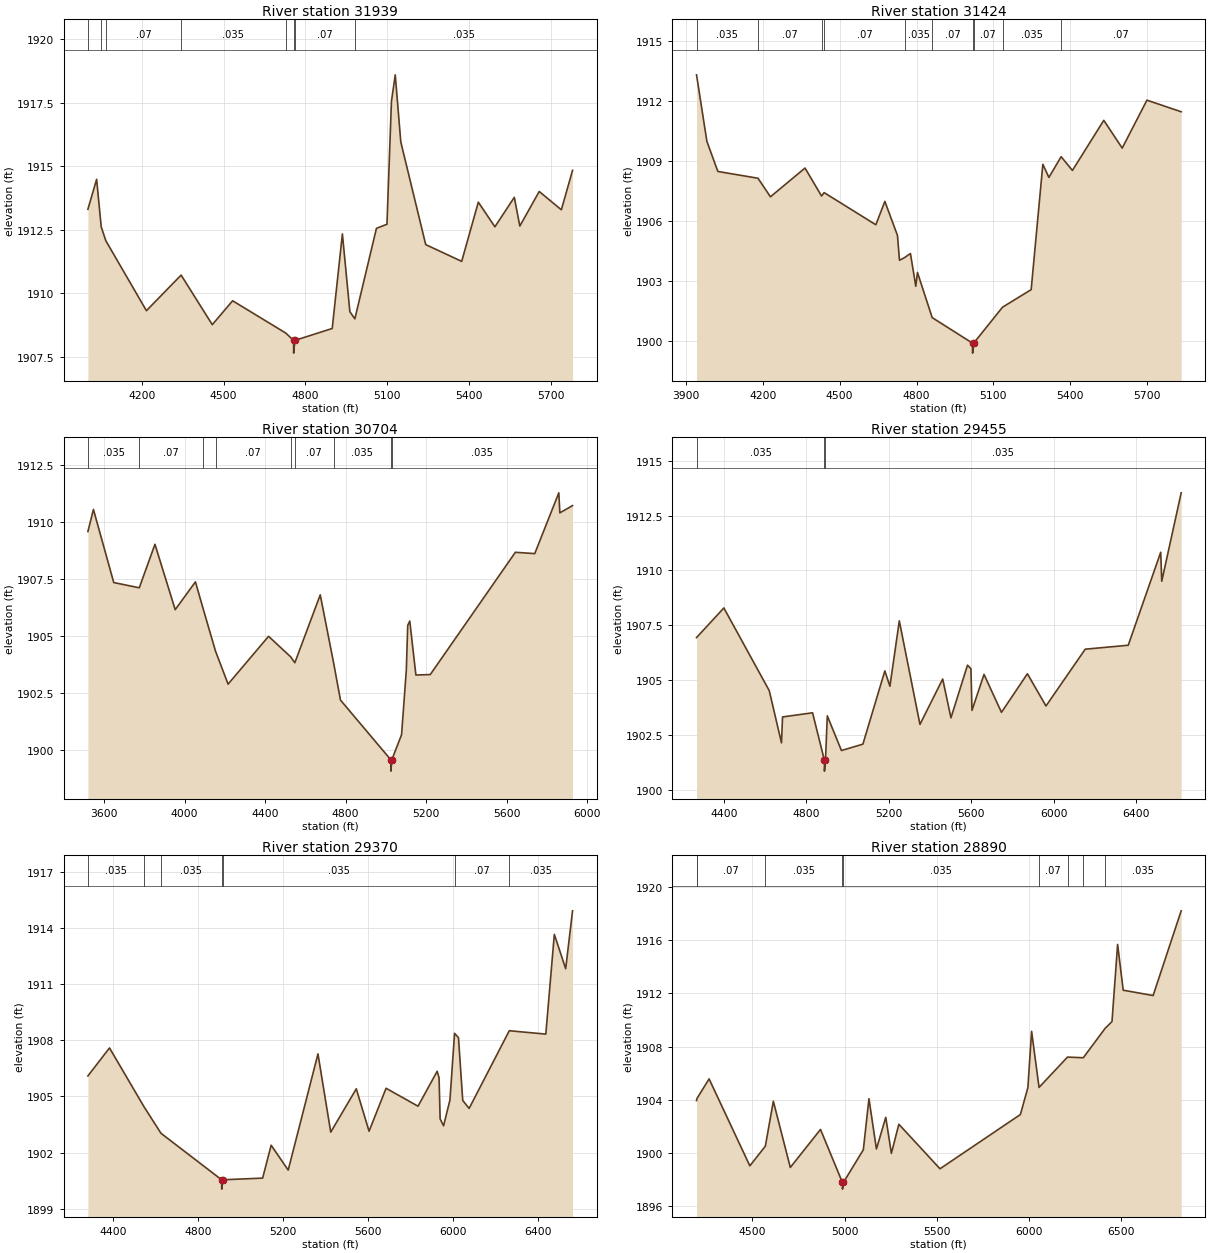
Type RM Length L Ch R = 1,31939,515,515,515
BEGIN DESCRIPTION:
Mapping XS 6cc10f3c
END DESCRIPTION:
XS GIS Cut Line= 3
      1463796.70      6947916.48      1463300.19      6948777.58
      1463168.25      6949548.38
#Sta/Elev= 30
  4002.9 1913.31  4034.9 1914.49  4051.7 1912.62  4068.7 1912.07  4217.4 1909.32
  4344.5 1910.72  4458.7 1908.77  4533.3 1909.71  4727.9 1908.44  4756.6 1908.15
  4756.9 1907.65  4761.2 1908.15  4898.2 1908.62  4935.5 1912.34  4962.9 1909.28
  4981.2 1909.00  5060.3 1912.56  5098.8 1912.72  5115.3 1917.56  5129.2 1918.60
  5149.5 1915.96  5240.8 1911.92  5372.7 1911.26  5433.6 1913.59  5494.4 1912.62
  5565.5 1913.78  5585.7 1912.65  5656.8 1914.01  5737.9 1913.29  5778.9 1914.84
#Mann=8,-1,0
  4002.9    0.07       0  4051.7   0.035       0  4068.7    0.07       0
  4344.5   0.035       0  4727.9    0.07       0  4756.6   0.035       0
  4761.2    0.07       0  4981.2   0.035       0
Bank Sta=4756.6,4761.2
Exp/Cntr=0.3,0.1

Type RM Length L Ch R = 1,31424,720,720,720
BEGIN DESCRIPTION:
Clear Fork Trib11 40.0
END DESCRIPTION:
XS GIS Cut Line= 3
      1463687.53      6947743.74      1462998.39      6948547.43
      1462833.57      6949364.17
#Sta/Elev= 30
  3941.3 1913.31  3981.7 1909.98  4024.5 1908.47  4181.2 1908.13  4229.8 1907.20
  4364.8 1908.64  4429.3 1907.24  4439.4 1907.41  4641.3 1905.80  4676.5 1906.97
  4725.8 1905.26  4733.5 1904.02  4754.1 1904.16  4776.3 1904.36  4797.2 1902.72
  4803.8 1903.41  4861.2 1901.15  5018.6 1899.87  5019.0 1899.37  5023.3 1899.87
  5135.8 1901.67  5247.6 1902.55  5293.2 1908.83  5316.8 1908.17  5364.6 1909.21
  5408.6 1908.52  5531.1 1911.03  5603.0 1909.64  5699.5 1912.04  5833.2 1911.46
#Mann=10,-1,0
  3941.3   0.035       0  4181.2    0.07       0  4429.3   0.035       0
  4439.4    0.07       0  4754.1   0.035       0  4861.2    0.07       0
  5018.6    0.07       0  5023.3    0.07       0  5135.8   0.035       0
  5364.6    0.07       0
Bank Sta=5018.6,5023.3
Exp/Cntr=0.3,0.1

Type RM Length L Ch R = 1,30704,1249,1249,1249
BEGIN DESCRIPTION:
Mapping XS fcc4dc88
END DESCRIPTION:
XS GIS Cut Line= 3
      1463628.44      6947775.04      1462368.06      6948552.79
      1462197.93      6949462.49
#Sta/Elev= 30
  3520.0 1909.59  3547.5 1910.56  3648.4 1907.35  3775.1 1907.12  3853.0 1909.03
  3953.5 1906.16  4054.0 1907.38  4092.9 1906.18  4153.6 1904.34  4216.1 1902.89
  4417.1 1904.99  4526.7 1904.09  4547.6 1903.83  4673.7 1906.81  4739.9 1903.83
  4774.2 1902.19  5024.0 1899.57  5024.4 1899.07  5029.3 1899.57  5077.5 1900.67
  5101.1 1903.50  5108.1 1905.47  5118.2 1905.66  5148.7 1903.29  5220.0 1903.31
  5642.7 1908.68  5738.8 1908.62  5858.3 1911.29  5863.4 1910.41  5926.5 1910.73
#Mann=9,-1,0
  3520.0   0.035       0  3775.1    0.07       0  4092.9   0.035       0
  4153.6    0.07       0  4526.7   0.035       0  4547.6    0.07       0
  4739.9   0.035       0  5024.0   0.035       0  5029.3   0.035       0
Bank Sta=5024,5029.3
Exp/Cntr=0.3,0.1

Type RM Length L Ch R = 1,29455,85,85,85
BEGIN DESCRIPTION:
Mapping XS 8ce6bf55
END DESCRIPTION:
XS GIS Cut Line= 4
      1462319.45      6946955.53      1462284.73      6947698.63
      1462236.12      6948337.51      1462173.62      6949302.75
#Sta/Elev= 30
  4266.8 1906.94  4399.4 1908.29  4619.7 1904.52  4679.1 1902.14  4684.2 1903.32
  4829.9 1903.51  4887.2 1901.35  4887.6 1900.85  4892.6 1901.35  4901.4 1903.37
  4970.0 1901.79  5074.2 1902.08  5180.6 1905.42  5205.3 1904.72  5250.8 1907.70
  5351.1 1902.98  5461.4 1905.05  5501.5 1903.28  5581.7 1905.68  5598.5 1905.52
  5603.5 1903.62  5661.9 1905.26  5746.6 1903.53  5872.4 1905.29  5962.6 1903.82
  6153.0 1906.41  6361.8 1906.59  6519.4 1910.83  6524.4 1909.51  6618.7 1913.54
#Mann=3,-1,0
  4266.8   0.035       0  4887.2   0.035       0  4892.6   0.035       0
Bank Sta=4887.2,4892.6
Exp/Cntr=0.3,0.1

Type RM Length L Ch R = 1,29370,480,480,480
BEGIN DESCRIPTION:
Mapping XS d733d472
END DESCRIPTION:
XS GIS Cut Line= 5
      1462225.70      6946976.38      1462208.34      6947361.82
      1462201.40      6947709.04      1462149.31      6948643.07
      1462107.69      6949253.55
#Sta/Elev= 30
  4281.4 1906.10  4383.1 1907.60  4545.5 1904.45  4625.3 1903.03  4910.8 1900.54
  4911.2 1900.04  4916.2 1900.54  5103.6 1900.63  5143.7 1902.39  5224.0 1901.06
  5364.0 1907.28  5424.1 1903.09  5544.3 1905.41  5604.4 1903.14  5684.5 1905.44
  5834.8 1904.48  5924.9 1906.35  5933.8 1906.00  5938.8 1903.80  5955.0 1903.43
  5985.0 1904.81  6006.7 1908.38  6025.1 1908.15  6045.2 1904.79  6075.2 1904.36
  6264.2 1908.52  6436.1 1908.34  6476.2 1913.68  6529.6 1911.84  6561.9 1914.94
#Mann=7,-1,0
  4281.4   0.035       0  4545.5    0.07       0  4625.3   0.035       0
  4910.8   0.035       0  4916.2   0.035       0  6006.7    0.07       0
  6264.2   0.035       0
Bank Sta=4910.8,4916.2
Exp/Cntr=0.3,0.1

Type RM Length L Ch R = 1,28890,605,605,605
BEGIN DESCRIPTION:
Clear Fork Trib11 37.0
END DESCRIPTION:
XS GIS Cut Line= 3
      1462118.08      6946952.06      1461794.81      6947687.55
      1462105.00      6949488.02
#Sta/Elev= 30
  4196.6 1903.94  4199.6 1904.11  4264.8 1905.57  4485.9 1899.03  4570.1 1900.51
  4613.5 1903.89  4705.6 1898.91  4869.4 1901.77  4988.4 1897.78  4988.8 1897.28
  4993.8 1897.78  5101.9 1900.24  5132.4 1904.08  5173.0 1900.30  5223.7 1902.68
  5254.1 1899.97  5294.7 1902.16  5518.0 1898.81  5954.3 1902.89  5994.9 1904.91
  6015.2 1909.15  6055.6 1904.93  6210.0 1907.21  6295.6 1907.16  6414.2 1909.37
  6451.5 1909.88  6482.0 1915.68  6512.4 1912.24  6674.7 1911.84  6827.0 1918.21
#Mann=9,-1,0
  4196.6   0.035       0  4199.6    0.07       0  4570.1   0.035       0
  4988.4   0.035       0  4993.8   0.035       0  6055.6    0.07       0
  6210.0   0.035       0  6295.6    0.07       0  6414.2   0.035       0
Bank Sta=4988.4,4993.8
Exp/Cntr=0.3,0.1

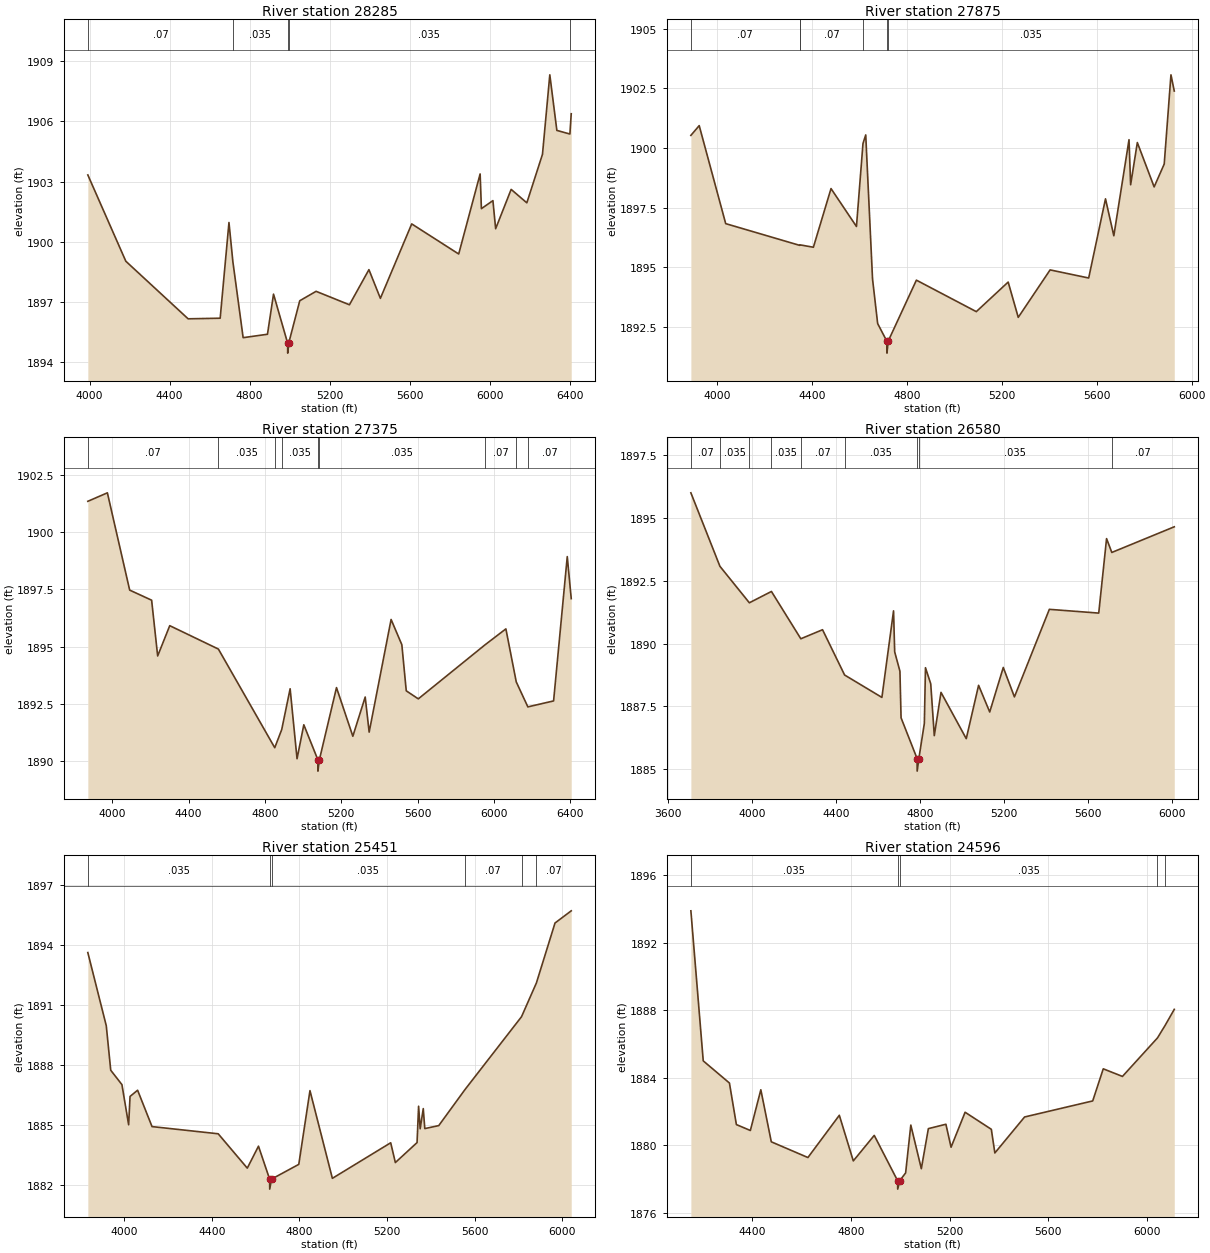
Type RM Length L Ch R = 1,28285,410,410,410
BEGIN DESCRIPTION:
Mapping XS 9d8493da
END DESCRIPTION:
XS GIS Cut Line= 4
      1461909.74      6946900.01      1461326.40      6947278.49
      1461232.65      6947882.65      1461934.04      6948740.30
#Sta/Elev= 30
  3991.6 1903.33  4181.4 1899.03  4492.6 1896.16  4652.7 1896.19  4696.6 1900.96
  4716.2 1899.00  4767.4 1895.22  4888.9 1895.39  4919.2 1897.39  4989.6 1894.95
  4990.0 1894.45  4995.1 1894.95  5050.2 1897.06  5131.7 1897.53  5298.4 1896.86
  5395.7 1898.61  5453.0 1897.18  5609.5 1900.89  5844.2 1899.39  5951.2 1903.38
  5957.6 1901.65  6015.1 1902.05  6028.7 1900.65  6106.2 1902.61  6184.5 1901.94
  6262.7 1904.36  6299.3 1908.32  6334.5 1905.55  6399.6 1905.37  6406.3 1906.38
#Mann=5,-1,0
  3991.6    0.07       0  4716.2   0.035       0  4989.6   0.035       0
  4995.1   0.035       0  6399.6    0.07       0
Bank Sta=4989.6,4995.1
Exp/Cntr=0.3,0.1

Type RM Length L Ch R = 1,27875,500,500,500
BEGIN DESCRIPTION:
Mapping XS 40d0ffc3
END DESCRIPTION:
XS GIS Cut Line= 4
      1461688.45      6946936.78      1461076.51      6947218.01
      1460956.72      6947639.89      1460277.04      6948270.08
#Sta/Elev= 30
  3887.8 1900.53  3922.9 1900.94  4034.7 1896.83  4346.4 1895.92  4348.0 1895.94
  4404.5 1895.84  4478.9 1898.30  4586.2 1896.71  4613.7 1900.19  4625.3 1900.55
  4654.0 1894.51  4675.6 1892.64  4714.4 1891.90  4714.9 1891.40  4719.9 1891.90
  4839.0 1894.46  5091.7 1893.14  5226.1 1894.38  5268.6 1892.90  5403.0 1894.89
  5565.7 1894.55  5636.6 1897.87  5671.7 1896.32  5735.8 1900.35  5742.6 1898.46
  5770.9 1900.23  5841.8 1898.37  5884.3 1899.33  5912.7 1903.07  5926.7 1902.39
#Mann=6,-1,0
  3887.8    0.07       0  4346.4   0.035       0  4348.0    0.07       0
  4613.7   0.035       0  4714.4   0.035       0  4719.9   0.035       0
Bank Sta=4714.4,4719.9
Exp/Cntr=0.3,0.1

Type RM Length L Ch R = 1,27375,795,795,795
BEGIN DESCRIPTION:
Mapping XS 800df18f
END DESCRIPTION:
XS GIS Cut Line= 3
      1461722.19      6946865.30      1460791.67      6947174.32
      1459869.54      6948422.31
#Sta/Elev= 30
  3872.4 1901.34  3974.8 1901.71  4091.6 1897.47  4206.6 1897.03  4238.2 1894.60
  4301.5 1895.92  4556.3 1894.90  4851.5 1890.60  4888.0 1891.39  4932.1 1893.17
  4968.3 1890.12  5003.8 1891.60  5077.1 1890.08  5077.6 1889.58  5085.5 1890.08
  5175.0 1893.22  5260.6 1891.10  5325.3 1892.81  5346.1 1891.28  5461.0 1896.19
  5517.3 1895.09  5540.4 1893.08  5603.5 1892.73  5952.3 1895.08  6062.3 1895.78
  6116.6 1893.47  6177.4 1892.38  6312.2 1892.64  6383.8 1898.93  6404.6 1897.10
#Mann=9,-1,0
  3872.4    0.07       0  4556.3   0.035       0  4851.5    0.07       0
  4888.0   0.035       0  5077.1   0.035       0  5085.5   0.035       0
  5952.3    0.07       0  6116.6   0.035       0  6177.4    0.07       0
Bank Sta=5077.1,5085.5
Exp/Cntr=0.3,0.1

Type RM Length L Ch R = 1,26580,1129,1129,1129
BEGIN DESCRIPTION:
Mapping XS 3147318e
END DESCRIPTION:
XS GIS Cut Line= 3
      1461402.75      6946577.11      1460190.98      6947025.01
      1459316.02      6947531.93
#Sta/Elev= 30
  3708.1 1895.99  3846.5 1893.07  3986.7 1891.62  4091.9 1892.07  4231.9 1890.19
  4335.4 1890.55  4440.5 1888.75  4618.2 1887.86  4673.7 1891.30  4679.1 1889.67
  4704.1 1888.90  4709.5 1887.05  4785.8 1885.43  4786.3 1884.93  4794.3 1885.43
  4820.5 1886.83  4825.8 1889.04  4850.9 1888.40  4867.8 1886.34  4899.8 1888.06
  5020.1 1886.22  5078.9 1888.34  5131.9 1887.28  5196.5 1889.05  5249.6 1887.88
  5416.0 1891.36  5651.3 1891.21  5688.6 1894.17  5713.6 1893.62  6011.2 1894.64
#Mann=9,-1,0
  3708.1    0.07       0  3846.5   0.035       0  3986.7    0.07       0
  4091.9   0.035       0  4231.9    0.07       0  4440.5   0.035       0
  4785.8   0.035       0  4794.3   0.035       0  5713.6    0.07       0
Bank Sta=4785.8,4794.3
Exp/Cntr=0.3,0.1

Type RM Length L Ch R = 1,25451,855,855,855
BEGIN DESCRIPTION:
Mapping XS 914073ec
END DESCRIPTION:
XS GIS Cut Line= 3
      1461137.32      6946043.52      1460006.95      6946278.49
      1459253.46      6947011.15
#Sta/Elev= 30
  3834.8 1893.62  3918.9 1889.96  3939.3 1887.73  3990.4 1887.01  4021.0 1885.00
  4027.4 1886.42  4061.9 1886.73  4127.7 1884.91  4429.6 1884.55  4562.3 1882.83
  4613.4 1883.93  4664.2 1882.28  4664.7 1881.78  4672.9 1882.28  4797.3 1883.02
  4848.3 1886.71  4950.5 1882.32  5216.6 1884.10  5237.9 1883.11  5336.9 1884.11
  5343.9 1885.93  5351.1 1884.80  5365.2 1885.81  5372.2 1884.81  5435.9 1884.96
  5556.0 1886.77  5813.5 1890.41  5881.4 1892.10  5966.3 1895.10  6040.3 1895.71
#Mann=6,-1,0
  3834.8   0.035       0  4664.2   0.035       0  4672.9   0.035       0
  5556.0    0.07       0  5813.5   0.035       0  5881.4    0.07       0
Bank Sta=4664.2,4672.9
Exp/Cntr=0.3,0.1

Type RM Length L Ch R = 1,24596,914,914,914
BEGIN DESCRIPTION:
Mapping XS 98148986
END DESCRIPTION:
XS GIS Cut Line= 3
      1460518.91      6945051.06      1459916.67      6945663.90
      1459190.99      6946490.28
#Sta/Elev= 30
  4151.7 1893.88  4201.8 1885.00  4307.9 1883.69  4336.1 1881.23  4392.7 1880.88
  4435.2 1883.29  4477.6 1880.21  4626.0 1879.28  4753.3 1881.78  4809.9 1879.08
  4894.8 1880.59  4989.4 1877.91  4989.9 1877.41  4998.1 1877.91  5022.0 1878.37
  5043.0 1881.20  5085.6 1878.62  5114.1 1880.99  5185.2 1881.25  5206.1 1879.89
  5263.0 1881.96  5369.3 1880.95  5383.6 1879.55  5504.1 1881.68  5780.2 1882.63
  5822.9 1884.53  5900.7 1884.08  6042.7 1886.36  6073.6 1887.10  6110.7 1888.05
#Mann=5,-1,0
  4151.7   0.035       0  4989.4   0.035       0  4998.1   0.035       0
  6042.7    0.07       0  6073.6   0.035       0
Bank Sta=4989.4,4998.1
Exp/Cntr=0.3,0.1

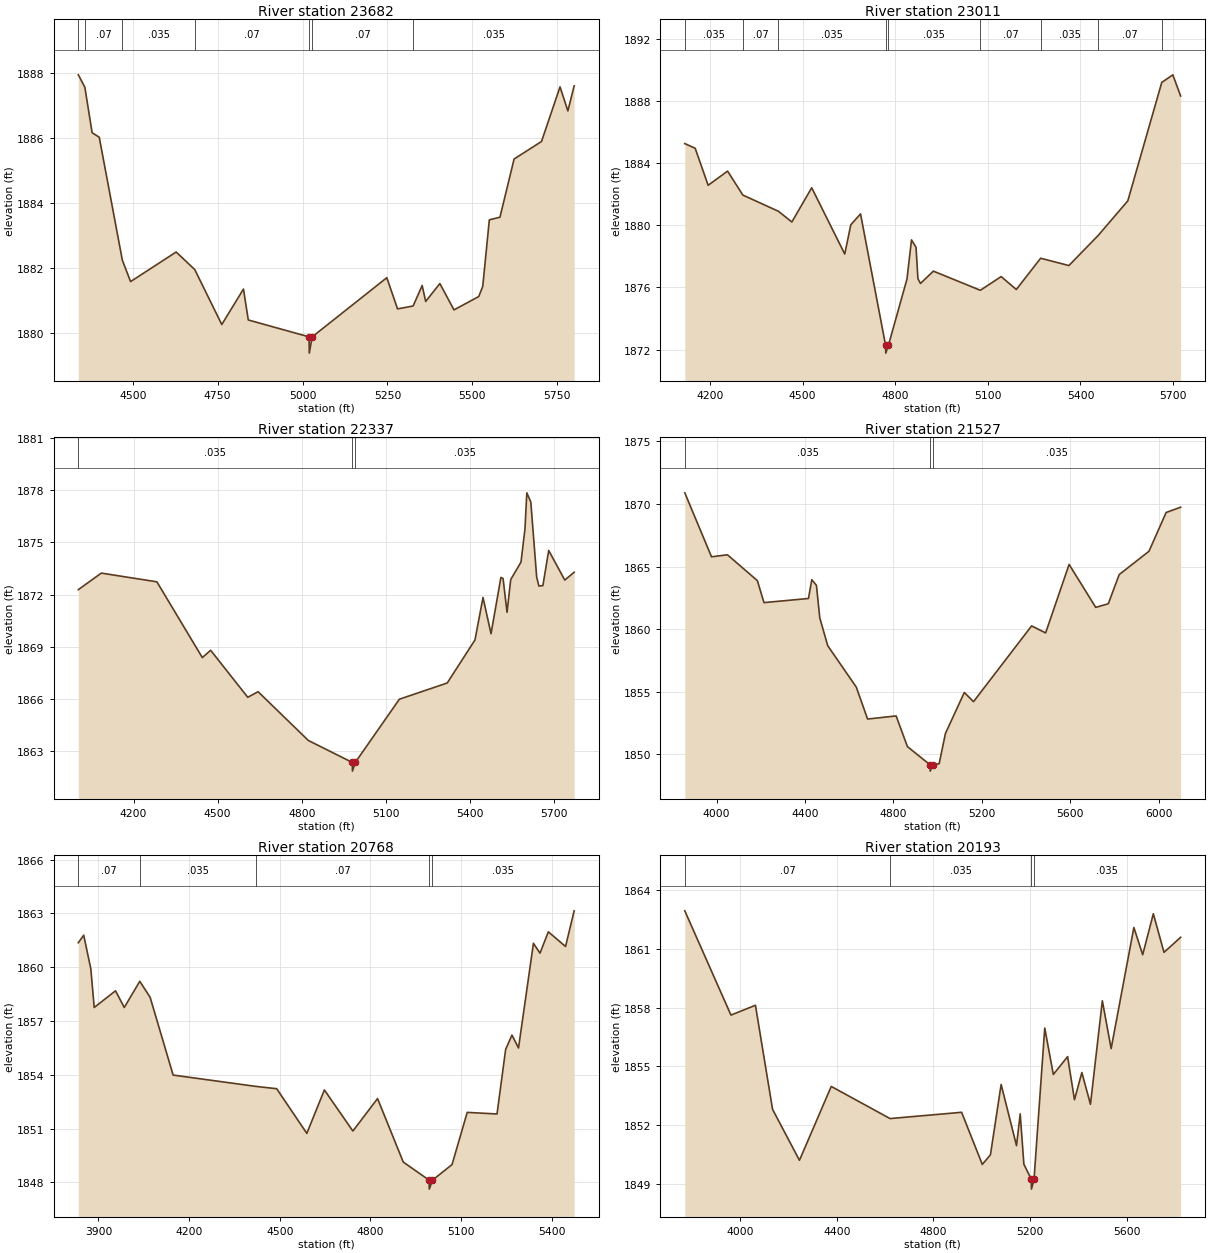
Type RM Length L Ch R = 1,23682,671,671,671
BEGIN DESCRIPTION:
Mapping XS 16bc3c75
END DESCRIPTION:
XS GIS Cut Line= 4
      1459569.24      6945074.93      1459197.81      6945465.99
      1459156.26      6945580.57      1458934.04      6946347.92
#Sta/Elev= 30
  4339.7 1887.94  4358.9 1887.56  4380.3 1886.16  4401.3 1886.02  4469.3 1882.24
  4493.5 1881.58  4627.8 1882.49  4682.6 1881.95  4762.1 1880.26  4826.0 1881.35
  4840.2 1880.40  5019.3 1879.88  5019.8 1879.38  5028.3 1879.88  5248.1 1881.70
  5279.8 1880.74  5325.6 1880.83  5352.2 1881.46  5362.6 1880.97  5404.3 1881.52
  5445.9 1880.71  5518.8 1881.12  5530.6 1881.43  5550.0 1883.48  5581.3 1883.56
  5622.9 1885.35  5703.7 1885.89  5758.2 1887.57  5781.3 1886.83  5799.8 1887.60
#Mann=7,-1,0
  4339.7   0.035       0  4358.9    0.07       0  4469.3   0.035       0
  4682.6    0.07       0  5019.3    0.07       0  5028.3    0.07       0
  5325.6   0.035       0
Bank Sta=5019.3,5028.3
Exp/Cntr=0.3,0.1

Type RM Length L Ch R = 1,23011,674,674,674
BEGIN DESCRIPTION:
Mapping XS 890db284
END DESCRIPTION:
XS GIS Cut Line= 4
      1459337.02      6945016.33      1458780.07      6945194.53
      1458597.23      6945441.68      1458246.60      6946063.09
#Sta/Elev= 30
  4118.6 1885.25  4152.2 1884.95  4194.2 1882.57  4257.2 1883.48  4306.6 1881.94
  4421.7 1880.90  4465.3 1880.21  4529.6 1882.41  4636.6 1878.15  4656.2 1880.03
  4687.7 1880.73  4768.9 1872.28  4769.4 1871.78  4778.0 1872.28  4838.1 1876.54
  4852.8 1879.06  4867.4 1878.58  4873.6 1876.56  4881.8 1876.26  4923.7 1877.05
  5075.7 1875.82  5143.1 1876.70  5192.2 1875.87  5271.0 1877.88  5362.5 1877.41
  5457.6 1879.35  5553.3 1881.57  5663.2 1889.18  5699.1 1889.67  5724.3 1888.31
#Mann=9,-1,0
  4118.6   0.035       0  4306.6    0.07       0  4421.7   0.035       0
  4768.9   0.035       0  4778.0   0.035       0  5075.7    0.07       0
  5271.0   0.035       0  5457.6    0.07       0  5663.2   0.035       0
Bank Sta=4768.9,4778
Exp/Cntr=0.3,0.1

Type RM Length L Ch R = 1,22337,810,810,810
BEGIN DESCRIPTION:
Mapping XS acf0ad0a
END DESCRIPTION:
XS GIS Cut Line= 3
      1459031.27      6944650.01      1458111.12      6945014.60
      1457510.42      6945511.13
#Sta/Elev= 30
  4002.9 1872.29  4084.9 1873.24  4283.2 1872.74  4445.3 1868.39  4475.0 1868.81
  4607.4 1866.11  4644.3 1866.43  4823.6 1863.63  4980.4 1862.37  4980.9 1861.87
  4991.1 1862.37  5148.4 1866.00  5319.1 1866.93  5418.1 1869.40  5446.8 1871.84
  5475.4 1869.76  5510.6 1872.99  5518.4 1872.93  5532.5 1870.99  5545.7 1872.87
  5582.3 1873.87  5596.6 1875.79  5603.1 1877.85  5617.4 1877.32  5638.2 1873.02
  5646.1 1872.50  5660.4 1872.52  5681.2 1874.54  5738.6 1872.84  5772.0 1873.29
#Mann=3,-1,0
  4002.9   0.035       0  4980.4   0.035       0  4991.1   0.035       0
Bank Sta=4980.4,4991.1
Exp/Cntr=0.3,0.1

Type RM Length L Ch R = 1,21527,759,759,759
BEGIN DESCRIPTION:
Mapping XS c6d2ac13
END DESCRIPTION:
XS GIS Cut Line= 3
      1459006.92      6943653.51      1458052.09      6944288.90
      1457326.40      6945111.81
#Sta/Elev= 30
  3855.8 1870.90  3976.7 1865.79  4048.9 1865.95  4184.1 1863.89  4214.2 1862.13
  4415.6 1862.46  4430.6 1863.96  4451.6 1863.51  4466.7 1860.91  4502.7 1858.69
  4632.0 1855.38  4683.1 1852.83  4812.3 1853.08  4863.4 1850.63  4966.2 1849.17
  4966.7 1848.67  4977.0 1849.17  5007.0 1849.26  5035.5 1851.68  5120.8 1854.95
  5162.6 1854.22  5425.4 1860.27  5488.9 1859.71  5595.2 1865.18  5715.7 1861.75
  5772.6 1862.04  5821.9 1864.37  5956.6 1866.23  6034.4 1869.33  6099.9 1869.75
#Mann=3,-1,0
  3855.8   0.035       0  4966.2   0.035       0  4977.0   0.035       0
Bank Sta=4966.2,4977
Exp/Cntr=0.3,0.1

Type RM Length L Ch R = 1,20768,575,575,575
BEGIN DESCRIPTION:
Mapping XS 9c53babf
END DESCRIPTION:
XS GIS Cut Line= 3
      1458583.35      6943434.73      1457520.84      6943889.60
      1457199.45      6944252.46
#Sta/Elev= 30
  3833.6 1861.36  3851.4 1861.78  3874.9 1859.91  3886.2 1857.75  3956.6 1858.68
  3985.6 1857.75  4036.9 1859.21  4071.1 1858.32  4147.3 1853.98  4420.6 1853.35
  4489.9 1853.22  4589.6 1850.73  4647.7 1853.15  4742.0 1850.86  4823.6 1852.67
  4908.7 1849.13  4994.3 1848.12  4994.8 1847.62  5005.4 1848.12  5070.1 1848.99
  5120.3 1851.90  5218.9 1851.81  5247.4 1855.41  5268.3 1856.21  5290.0 1855.49
  5339.4 1861.33  5361.1 1860.78  5388.7 1861.97  5445.6 1861.15  5474.1 1863.14
#Mann=5,-1,0
  3833.6    0.07       0  4036.9   0.035       0  4420.6    0.07       0
  4994.3    0.07       0  5005.4   0.035       0
Bank Sta=4994.3,5005.4
Exp/Cntr=0.3,0.1

Type RM Length L Ch R = 1,20193,845,845,845
BEGIN DESCRIPTION:
Mapping XS 030ece3e
END DESCRIPTION:
XS GIS Cut Line= 4
      1458593.80      6943254.17      1457715.29      6943393.07
      1457385.42      6943465.99      1456944.73      6944163.47
#Sta/Elev= 30
  3771.0 1862.94  3962.1 1857.62  4063.4 1858.12  4134.3 1852.81  4245.6 1850.21
  4377.2 1853.98  4620.6 1852.34  4916.8 1852.66  5002.4 1850.00  5036.1 1850.49
  5080.4 1854.08  5144.0 1850.96  5159.3 1852.58  5174.5 1850.01  5205.4 1849.24
  5205.9 1848.74  5216.5 1849.24  5260.9 1856.96  5296.4 1854.59  5355.5 1855.50
  5384.0 1853.30  5414.5 1854.69  5450.1 1853.07  5499.3 1858.35  5535.7 1855.91
  5629.8 1862.09  5666.3 1860.70  5710.4 1862.79  5754.5 1860.82  5823.3 1861.59
#Mann=4,-1,0
  3771.0    0.07       0  4620.6   0.035       0  5205.4   0.035       0
  5216.5   0.035       0
Bank Sta=5205.4,5216.5
Exp/Cntr=0.3,0.1

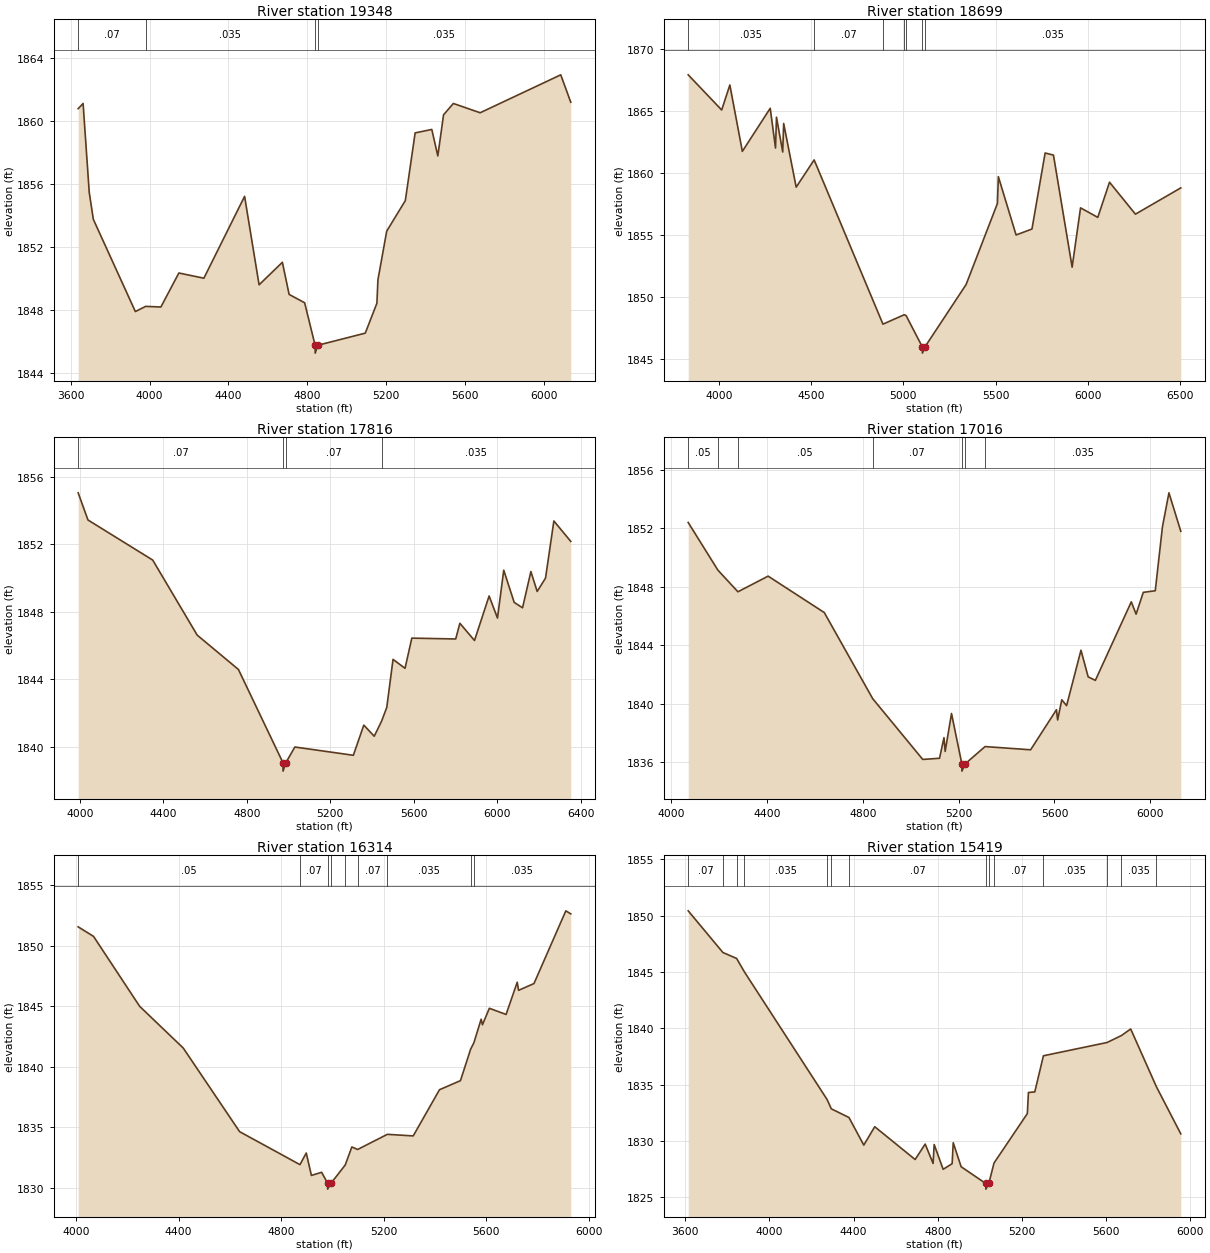
Type RM Length L Ch R = 1,19348,649,649,649
BEGIN DESCRIPTION:
Mapping XS ba408c29
END DESCRIPTION:
XS GIS Cut Line= 3
      1458309.07      6943261.13      1457003.48      6942896.54
      1455885.38      6942660.42
#Sta/Elev= 30
  3638.1 1860.78  3663.1 1861.11  3694.2 1855.47  3715.0 1853.75  3928.2 1847.89
  3980.4 1848.22  4057.6 1848.18  4148.8 1850.34  4275.7 1850.01  4482.2 1855.21
  4555.7 1849.59  4673.8 1851.02  4708.0 1848.98  4786.7 1848.45  4839.8 1845.75
  4840.3 1845.25  4853.6 1845.75  5094.3 1846.52  5153.2 1848.42  5158.4 1849.90
  5203.0 1853.00  5297.4 1854.94  5347.1 1859.24  5431.6 1859.46  5462.2 1857.78
  5491.3 1860.39  5541.0 1861.11  5676.9 1860.52  6085.7 1862.93  6136.4 1861.19
#Mann=4,-1,0
  3638.1    0.07       0  3980.4   0.035       0  4839.8   0.035       0
  4853.6   0.035       0
Bank Sta=4839.8,4853.6
Exp/Cntr=0.3,0.1

Type RM Length L Ch R = 1,18699,883,883,883
BEGIN DESCRIPTION:
Mapping XS 00b4dcef
END DESCRIPTION:
XS GIS Cut Line= 3
      1458611.14      6942823.63      1457486.12      6942504.18
      1456013.89      6942205.57
#Sta/Elev= 30
  3833.1 1867.94  4014.7 1865.10  4059.0 1867.12  4126.8 1861.76  4278.0 1865.24
  4306.7 1862.03  4311.9 1864.52  4345.8 1861.71  4351.0 1864.01  4418.8 1858.87
  4516.2 1861.07  4889.4 1847.81  5005.2 1848.57  5015.0 1848.50  5103.1 1845.97
  5103.6 1845.47  5117.0 1845.97  5340.5 1851.01  5510.2 1857.55  5515.3 1859.72
  5611.5 1855.01  5697.6 1855.49  5769.0 1861.63  5814.2 1861.46  5915.5 1852.41
  5961.1 1857.20  6054.7 1856.43  6118.2 1859.27  6258.8 1856.69  6504.8 1858.81
#Mann=7,-1,0
  3833.1   0.035       0  4516.2    0.07       0  4889.4   0.035       0
  5005.2    0.07       0  5015.0   0.035       0  5103.1   0.035       0
  5117.0   0.035       0
Bank Sta=5103.1,5117
Exp/Cntr=0.3,0.1

Type RM Length L Ch R = 1,17816,800,800,800
BEGIN DESCRIPTION:
Mapping XS 645186d5
END DESCRIPTION:
XS GIS Cut Line= 3
      1458461.80      6941754.18      1457451.40      6941698.63
      1456104.22      6941757.65
#Sta/Elev= 30
  3991.6 1855.05  4038.5 1853.44  4348.9 1851.06  4561.9 1846.61  4759.6 1844.57
  4972.9 1839.04  4973.4 1838.54  4986.8 1839.04  5029.9 1839.97  5310.2 1839.48
  5360.3 1841.27  5410.3 1840.61  5445.4 1841.50  5470.4 1842.32  5500.4 1845.17
  5557.9 1844.64  5590.5 1846.43  5800.7 1846.38  5820.7 1847.31  5890.8 1846.29
  5960.8 1848.93  6000.9 1847.62  6030.9 1850.46  6081.0 1848.55  6121.0 1848.23
  6161.0 1850.38  6191.1 1849.20  6231.1 1849.99  6271.1 1853.38  6352.0 1852.17
#Mann=4,-1,0
  3991.6    0.07       0  4972.9    0.07       0  4986.8    0.07       0
  5445.4   0.035       0
Bank Sta=4972.9,4986.8
Exp/Cntr=0.3,0.1

Type RM Length L Ch R = 1,17016,702,702,702
BEGIN DESCRIPTION:
Mapping XS 7887c220
END DESCRIPTION:
XS GIS Cut Line= 3
      1458225.72      6941177.79      1457315.98      6941056.26
      1456178.56      6941031.99
#Sta/Elev= 30
  4071.5 1852.39  4195.5 1849.13  4279.0 1847.65  4405.0 1848.72  4639.3 1846.23
  4841.3 1840.34  5050.3 1836.18  5120.3 1836.26  5138.8 1837.67  5143.8 1836.73
  5170.3 1839.32  5213.3 1835.88  5213.8 1835.38  5227.4 1835.88  5310.3 1837.06
  5500.4 1836.84  5608.2 1839.58  5613.2 1838.88  5630.4 1840.26  5650.5 1839.86
  5710.5 1843.65  5740.5 1841.83  5770.5 1841.59  5920.5 1846.96  5940.5 1846.12
  5970.5 1847.61  6020.5 1847.72  6050.5 1852.10  6077.6 1854.42  6127.0 1851.79
#Mann=7,-1,0
  4071.5    0.05       0  4195.5    0.07       0  4279.0    0.05       0
  4841.3    0.07       0  5213.3    0.07       0  5227.4    0.07       0
  5310.3   0.035       0
Bank Sta=5213.3,5227.4
Exp/Cntr=0.3,0.1

Type RM Length L Ch R = 1,16314,895,895,895
BEGIN DESCRIPTION:
Clear Fork Trib11 19.0
END DESCRIPTION:
XS GIS Cut Line= 3
      1458155.01      6940438.00      1457155.00      6940438.00
      1456254.96      6940638.01
#Sta/Elev= 30
  4007.8 1851.55  4067.8 1850.76  4247.8 1844.99  4417.8 1841.55  4637.8 1834.65
  4873.2 1831.93  4897.8 1832.89  4917.8 1831.04  4957.8 1831.30  4980.7 1830.41
  4981.2 1829.91  4994.9 1830.41  5049.8 1831.90  5075.7 1833.39  5098.1 1833.18
  5214.1 1834.43  5315.1 1834.30  5417.6 1838.11  5499.5 1838.86  5539.2 1841.46
  5551.6 1841.97  5580.2 1843.93  5585.3 1843.47  5612.2 1844.83  5677.5 1844.32
  5721.0 1846.98  5726.2 1846.31  5786.3 1846.87  5910.6 1852.87  5929.8 1852.62
#Mann=9,-1,0
  4007.8    0.05       0  4873.2    0.07       0  4980.7    0.07       0
  4994.9    0.07       0  5049.8   0.035       0  5098.1    0.07       0
  5214.1   0.035       0  5539.2    0.07       0  5551.6   0.035       0
Bank Sta=4980.7,4994.9
Exp/Cntr=0.3,0.1

Type RM Length L Ch R = 1,15419,44,44,44
BEGIN DESCRIPTION:
Mapping XS 0043821c
END DESCRIPTION:
XS GIS Cut Line= 4
      1458208.37      6940031.97      1457246.54      6939761.13
      1456871.54      6939674.32      1455938.74      6939459.33
#Sta/Elev= 30
  3614.1 1850.44  3779.1 1846.74  3844.3 1846.21  3881.2 1845.02  4274.2 1833.69
  4294.4 1832.86  4378.2 1832.09  4448.7 1829.64  4500.8 1831.27  4692.8 1828.36
  4740.6 1829.73  4778.2 1828.01  4783.3 1829.69  4826.0 1827.49  4868.7 1827.99
  4873.9 1829.85  4911.4 1827.72  5028.5 1826.23  5029.0 1825.73  5043.0 1826.23
  5067.8 1828.05  5226.2 1832.44  5231.3 1834.31  5261.5 1834.36  5302.6 1837.57
  5605.5 1838.75  5673.6 1839.37  5717.4 1839.95  5839.9 1834.81  5955.5 1830.64
#Mann=14,-1,0
  3614.1    0.07       0  3779.1   0.035       0  3844.3    0.07       0
  3881.2   0.035       0  4274.2    0.07       0  4294.4   0.035       0
  4378.2    0.07       0  5028.5    0.07       0  5043.0    0.07       0
  5067.8    0.07       0  5302.6   0.035       0  5605.5    0.07       0
  5673.6   0.035       0  5839.9    0.07       0
Bank Sta=5028.5,5043
Exp/Cntr=0.3,0.1