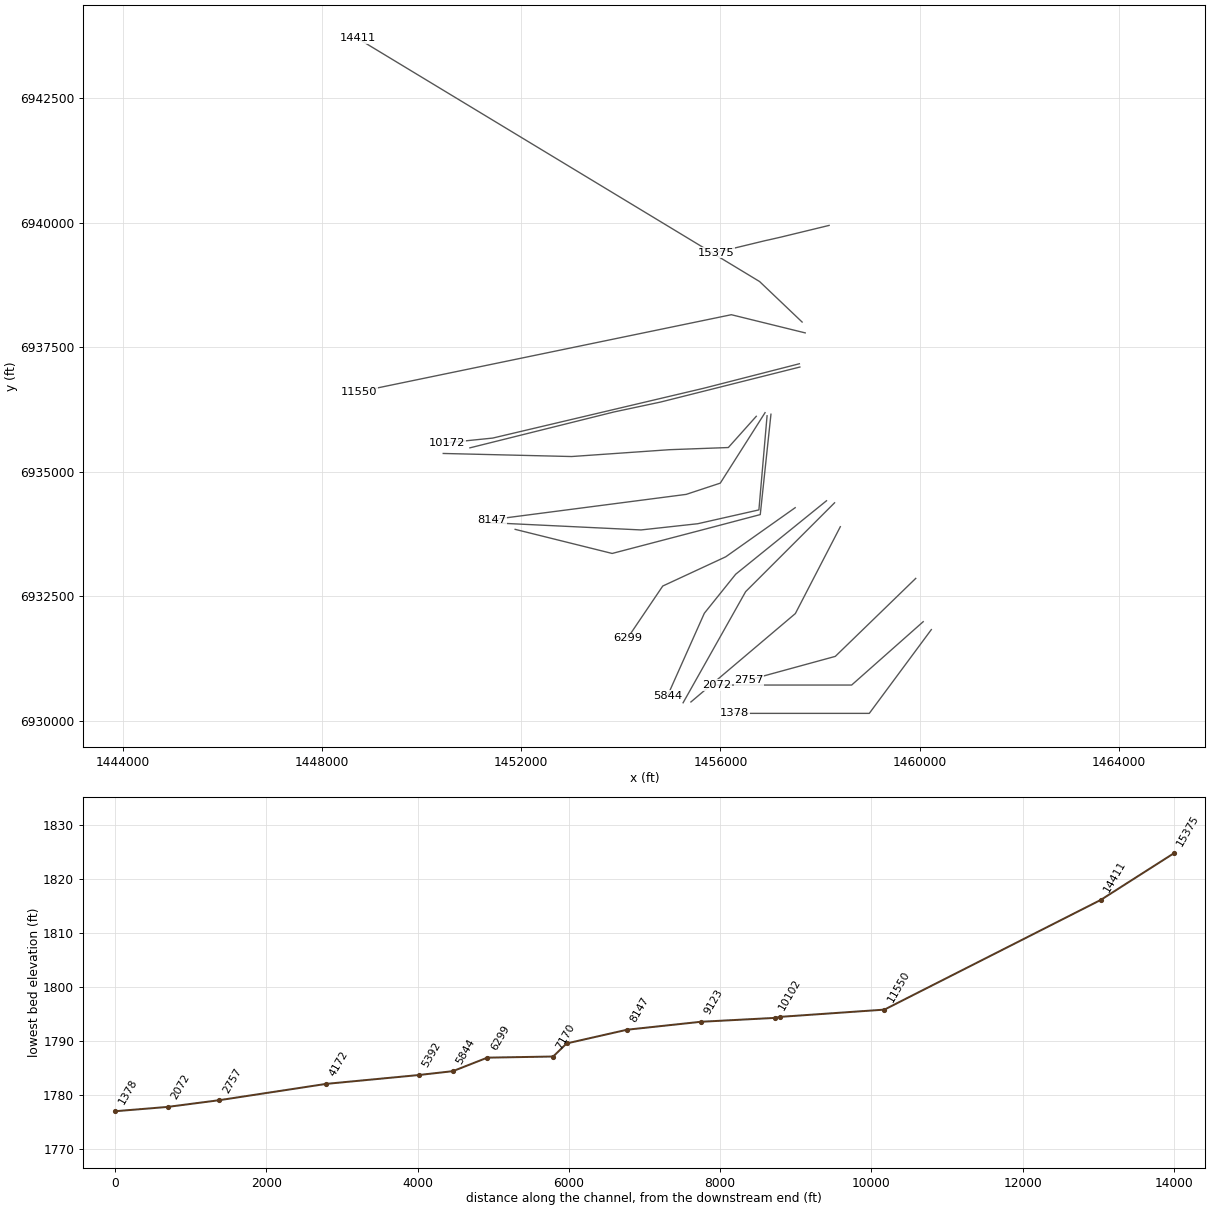
HEC-RAS study Clear Fork Trib11.prj: Clear Fork Trib11 Base Level Engineering

--- Clear Fork Trib11.g01 (geometry) --- (continued)

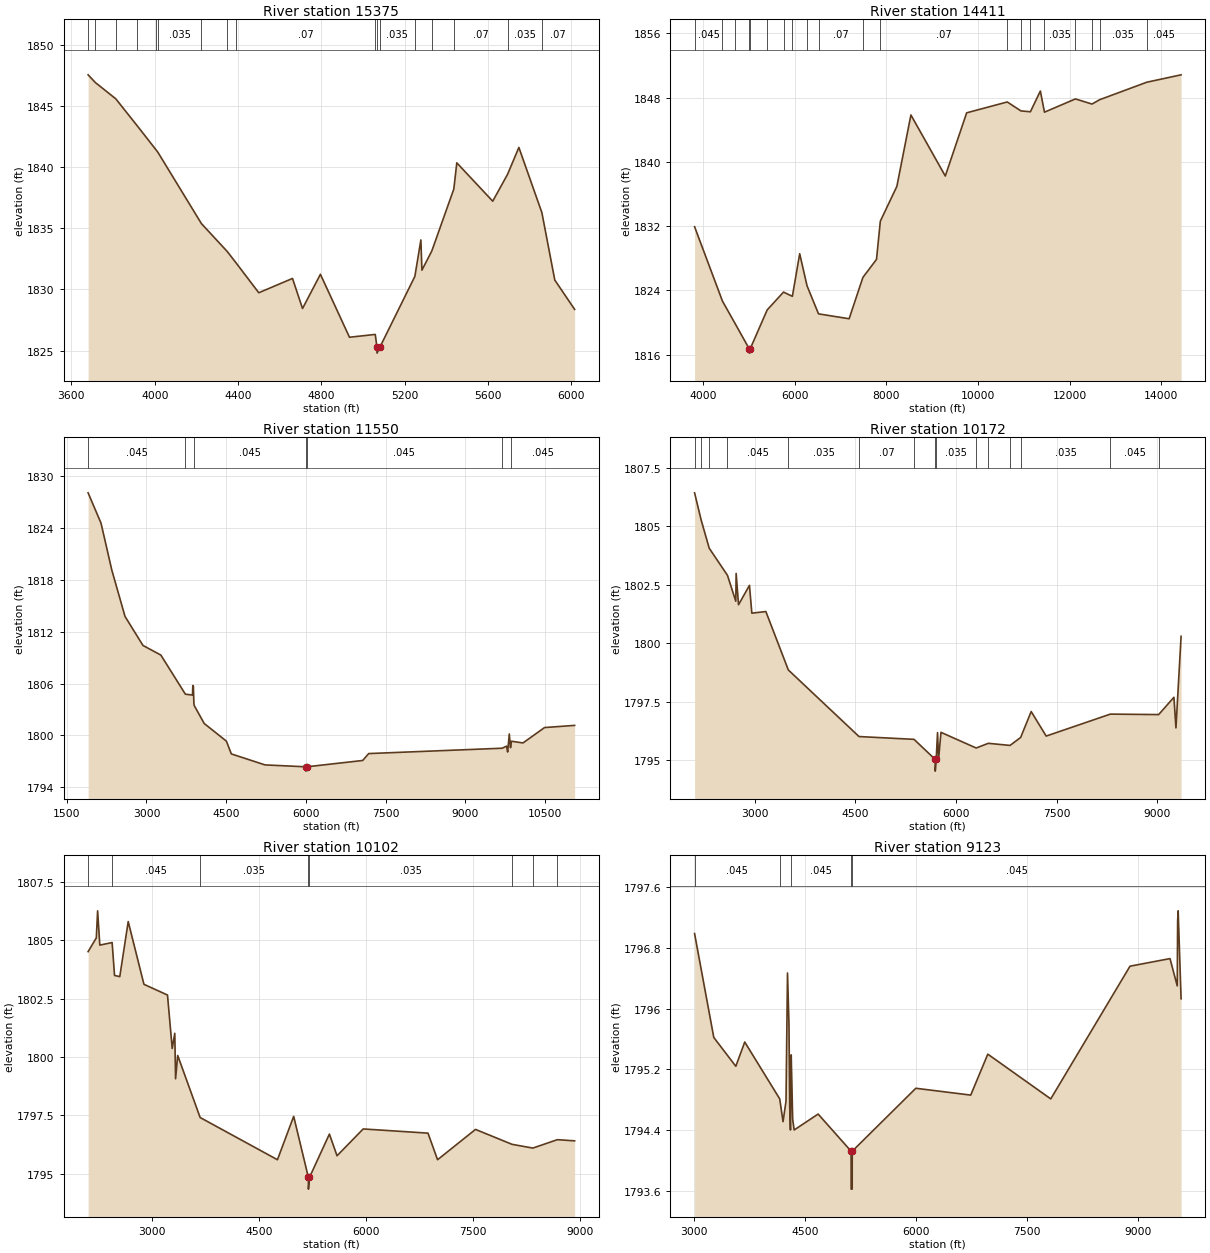
Type RM Length L Ch R = 1,15375,964,964,964
BEGIN DESCRIPTION:
Mapping XS 8e599fe8
END DESCRIPTION:
XS GIS Cut Line= 5
      1458180.57      6939945.15      1457222.23      6939712.51
      1456979.17      6939656.96      1456899.31      6939639.60
      1455909.82      6939400.04
#Sta/Elev= 30
  3680.2 1847.56  3714.9 1846.93  3812.9 1845.60  3914.1 1843.43  4005.9 1841.43
  4015.3 1841.22  4224.0 1835.39  4347.8 1833.11  4387.9 1832.23  4499.4 1829.73
  4661.3 1830.90  4709.4 1828.44  4795.3 1831.24  4934.8 1826.09  5058.5 1826.32
  5066.6 1825.29  5067.1 1824.79  5081.1 1825.29  5248.7 1831.07  5277.5 1834.05
  5282.6 1831.58  5329.8 1833.14  5435.7 1838.22  5449.9 1840.36  5622.4 1837.22
  5693.9 1839.43  5747.9 1841.62  5858.3 1836.29  5920.3 1830.77  6015.5 1828.37
#Mann=17,-1,0
  3680.2    0.07       0  3714.9   0.035       0  3812.9    0.07       0
  3914.1   0.035       0  4005.9    0.07       0  4015.3   0.035       0
  4224.0    0.07       0  4347.8   0.035       0  4387.9    0.07       0
  5058.5   0.035       0  5066.6    0.07       0  5081.1   0.035       0
  5248.7    0.07       0  5329.8   0.035       0  5435.7    0.07       0
  5693.9   0.035       0  5858.3    0.07       0
Bank Sta=5066.6,5081.1
Exp/Cntr=0.3,0.1

Type RM Length L Ch R = 1,14411,2861,2861,2861
BEGIN DESCRIPTION:
Mapping XS 2c649eb2
END DESCRIPTION:
XS GIS Cut Line= 3
      1457638.91      6938004.17      1456784.72      6938818.12
      1448714.42      6943703.10
#Sta/Elev= 30
  3820.1 1831.92  4428.7 1822.65  4703.5 1819.87  5015.7 1816.68  5016.2 1816.18
  5030.3 1816.68  5404.1 1821.56  5760.5 1823.78  5953.7 1823.25  6113.1 1828.56
  6273.0 1824.57  6523.6 1821.07  7191.5 1820.46  7492.5 1825.61  7788.9 1827.85
  7872.4 1832.61  8233.1 1836.94  8539.5 1845.83  9289.6 1838.23  9755.7 1846.10
 10641.0 1847.45 10939.7 1846.34 11146.0 1846.23 11363.7 1848.81 11453.5 1846.18
 12128.7 1847.83 12490.3 1847.19 12656.0 1847.73 13686.0 1849.91 14433.6 1850.83
#Mann=20,-1,0
  3820.1   0.045       0  4428.7   0.045       0  4703.5    0.07       0
  5015.7   0.045       0  5030.3   0.045       0  5404.1    0.07       0
  5760.5   0.045       0  5953.7    0.07       0  6273.0   0.035       0
  6523.6    0.07       0  7492.5   0.045       0  7872.4    0.07       0
 10641.0    0.07       0 10939.7   0.035       0 11146.0    0.07       0
 11453.5   0.035       0 12128.7   0.035       0 12490.3    0.07       0
 12656.0   0.035       0 13686.0   0.045       0
Bank Sta=5015.7,5030.3
Exp/Cntr=0.3,0.1

Type RM Length L Ch R = 1,11550,1378,1378,1378
BEGIN DESCRIPTION:
Mapping XS f81a725e
END DESCRIPTION:
XS GIS Cut Line= 3
      1457701.02      6937786.05      1456218.32      6938151.36
      1448751.40      6936605.50
#Sta/Elev= 30
  1902.1 1828.06  2145.2 1824.55  2347.6 1819.13  2596.6 1813.76  2933.7 1810.41
  3270.9 1809.29  3732.0 1804.77  3865.8 1804.67  3871.6 1805.77  3881.9 1805.73
  3892.1 1803.68  3898.3 1803.46  4086.1 1801.38  4503.0 1799.34  4596.7 1797.86
  5229.9 1796.59  5998.7 1796.37  5999.2 1795.87  6013.3 1796.37  7067.1 1797.10
  7180.4 1797.90  9691.7 1798.52  9774.2 1798.76  9794.6 1798.08  9825.3 1800.17
  9848.4 1798.58  9866.1 1799.33 10082.9 1799.13 10489.1 1800.91 11054.4 1801.16
#Mann=7,-1,0
  1902.1   0.045       0  3732.0   0.035       0  3898.3   0.045       0
  5998.7   0.045       0  6013.3   0.045       0  9691.7   0.035       0
  9848.4   0.045       0
Bank Sta=5998.7,6013.3
Exp/Cntr=0.3,0.1

Type RM Length L Ch R = 1,10172,70,70,70
BEGIN DESCRIPTION:
Mapping XS d95e4f17
END DESCRIPTION:
XS GIS Cut Line= 4
      1457583.69      6937166.21      1455668.43      6936675.22
      1451427.41      6935673.14      1450508.65      6935579.53
#Sta/Elev= 30
  2099.9 1806.44  2197.7 1805.28  2318.4 1804.07  2590.5 1802.91  2714.8 1801.80
  2720.0 1802.99  2755.6 1801.65  2918.7 1802.48  2954.3 1801.29  3163.4 1801.36
  3498.6 1798.86  4553.1 1796.01  5374.2 1795.89  5690.0 1795.03  5690.5 1794.53
  5704.8 1795.03  5724.7 1796.18  5739.7 1795.03  5776.0 1796.19  6301.0 1795.52
  6482.7 1795.72  6806.3 1795.63  6964.4 1795.97  7122.1 1797.08  7345.7 1796.03
  8303.2 1796.97  9023.9 1796.95  9251.5 1797.69  9281.7 1796.38  9358.4 1800.30
#Mann=15,-1,0
  2099.9    0.07       0  2197.7   0.045       0  2318.4    0.07       0
  2590.5   0.045       0  3498.6   0.035       0  4553.1    0.07       0
  5374.2   0.035       0  5690.0    0.07       0  5704.8   0.035       0
  6301.0    0.07       0  6482.7   0.035       0  6806.3    0.07       0
  6964.4   0.035       0  8303.2   0.045       0  9023.9   0.035       0
Bank Sta=5690,5704.8
Exp/Cntr=0.3,0.1

Type RM Length L Ch R = 1,10102,979,979,979
BEGIN DESCRIPTION:
Mapping XS be5adc46
END DESCRIPTION:
XS GIS Cut Line= 4
      1457594.08      6937100.37      1454798.96      6936397.25
      1453861.46      6936197.60      1450970.82      6935477.11
#Sta/Elev= 30
  2102.3 1804.52  2217.2 1805.11  2235.4 1806.27  2266.3 1804.80  2439.1 1804.91
  2472.6 1803.50  2546.2 1803.45  2664.4 1805.81  2885.0 1803.12  3215.0 1802.66
  3281.2 1800.37  3317.1 1801.02  3328.4 1799.07  3358.2 1800.07  3672.6 1797.41
  4756.3 1795.60  4984.0 1797.46  5190.1 1794.84  5190.6 1794.34  5204.9 1794.84
  5484.7 1796.70  5591.8 1795.77  5958.4 1796.92  6866.7 1796.74  7000.9 1795.60
  7532.5 1796.90  8045.4 1796.26  8336.4 1796.10  8680.1 1796.46  8922.1 1796.41
#Mann=8,-1,0
  2102.3    0.07       0  2439.1   0.045       0  3672.6   0.035       0
  5190.1   0.035       0  5204.9   0.035       0  8045.4    0.07       0
  8336.4   0.035       0  8680.1   0.045       0
Bank Sta=5190.1,5204.9
Exp/Cntr=0.3,0.1

Type RM Length L Ch R = 1,9123,976,976,976
BEGIN DESCRIPTION:
Mapping XS 0dda1cb5
END DESCRIPTION:
XS GIS Cut Line= 5
      1456718.88      6936110.82      1456157.79      6935483.33
      1454977.23      6935439.93      1453011.73      6935302.58
      1450435.38      6935364.18
#Sta/Elev= 30
  3009.0 1796.99  3268.4 1795.62  3566.0 1795.24  3686.3 1795.56  4159.0 1794.81
  4203.8 1794.51  4243.8 1794.78  4263.8 1796.47  4283.8 1795.79  4293.9 1794.71
  4303.9 1794.40  4307.3 1794.74  4313.9 1795.39  4333.9 1794.54  4353.9 1794.40
  4677.7 1794.61  5123.1 1794.12  5123.6 1793.62  5137.5 1793.62  5138.0 1794.12
  5997.0 1794.95  6738.5 1794.86  6969.1 1795.40  7819.4 1794.81  8889.7 1796.56
  9429.8 1796.66  9527.6 1796.30  9532.6 1797.15  9539.9 1797.29  9579.5 1796.13
#Mann=5,-1,0
  3009.0   0.045       0  4159.0   0.035       0  4307.3   0.045       0
  5123.1   0.045       0  5138.0   0.045       0
Bank Sta=5123.1,5138
Exp/Cntr=0.3,0.1

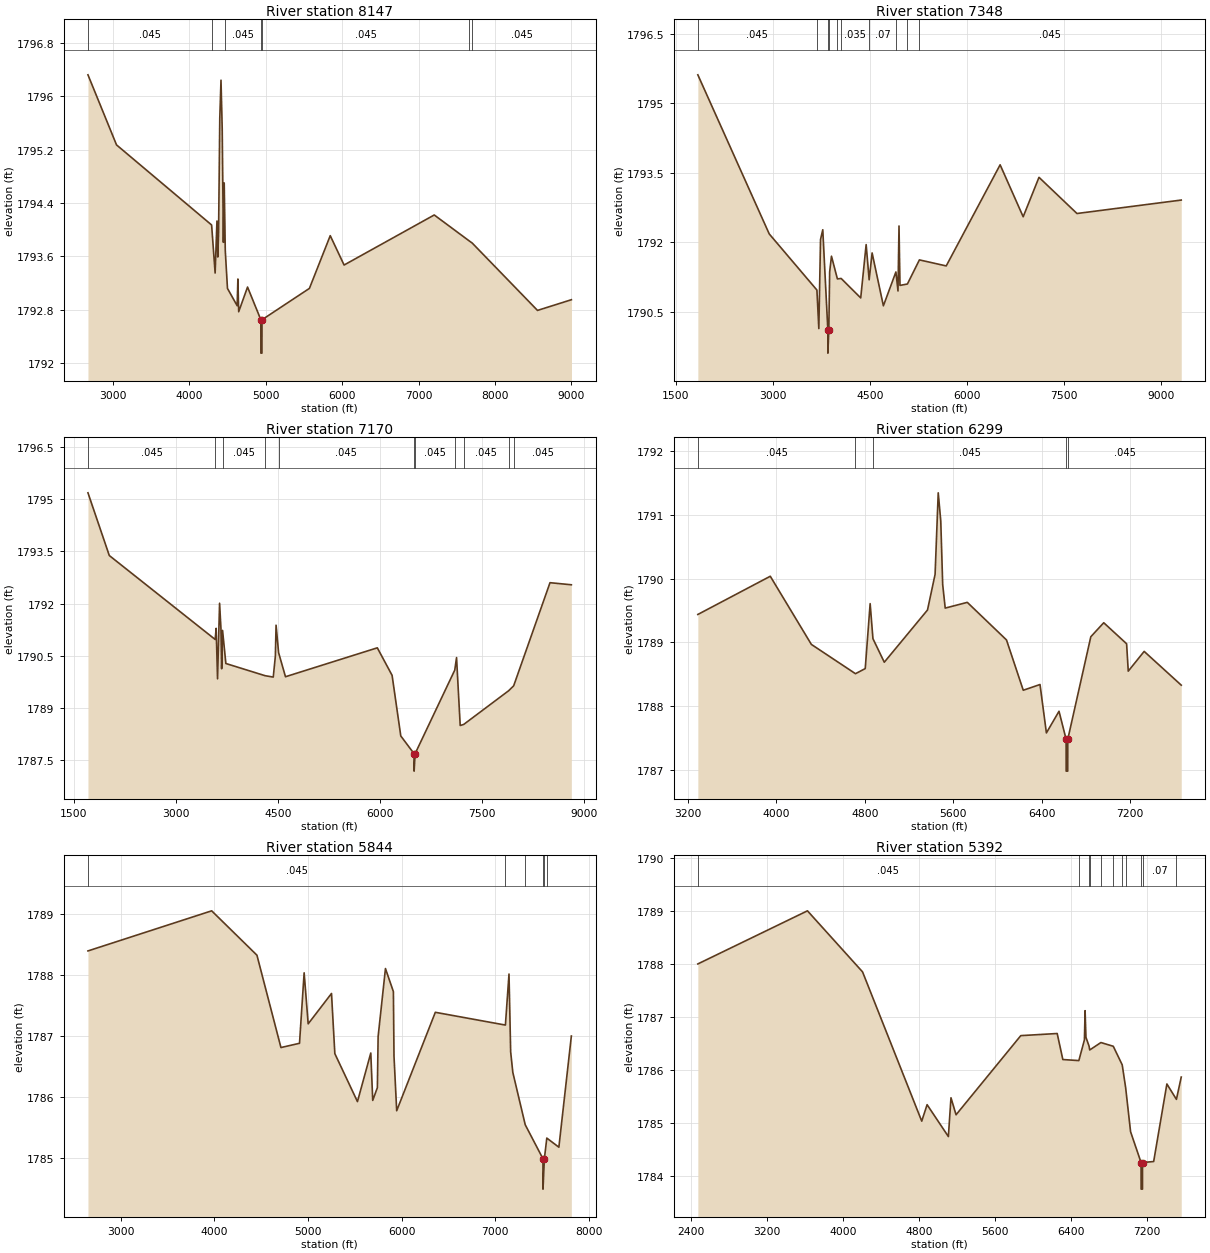
Type RM Length L Ch R = 1,8147,799,799,799
BEGIN DESCRIPTION:
Clear Fork Trib11 10.0
END DESCRIPTION:
XS GIS Cut Line= 4
      1456895.04      6936183.64      1455996.10      6934768.23
      1455311.60      6934542.17      1451415.45      6934035.19
#Sta/Elev= 30
  2673.6 1796.32  3047.5 1795.27  4292.0 1794.07  4338.0 1793.35  4361.9 1794.13
  4372.6 1793.59  4383.1 1793.96  4398.9 1795.67  4414.7 1796.24  4430.6 1795.51
  4446.3 1793.81  4456.8 1794.70  4470.6 1793.69  4499.4 1793.12  4626.4 1792.86
  4635.8 1793.26  4646.4 1792.77  4762.2 1793.14  4936.3 1792.65  4936.8 1792.15
  4950.8 1792.15  4951.3 1792.65  5572.0 1793.12  5844.5 1793.91  6025.8 1793.47
  7205.7 1794.22  7665.1 1793.83  7702.0 1793.80  8557.1 1792.79  9000.2 1792.95
#Mann=7,-1,0
  2673.6   0.045       0  4292.0   0.035       0  4470.6   0.045       0
  4936.3   0.045       0  4951.3   0.045       0  7665.1    0.07       0
  7702.0   0.045       0
Bank Sta=4936.3,4951.3
Exp/Cntr=0.3,0.1

Type RM Length L Ch R = 1,7348,178,178,178
BEGIN DESCRIPTION:
Mapping XS 6681d667
END DESCRIPTION:
XS GIS Cut Line= 5
      1456935.39      6936121.08      1456771.54      6934230.64
      1455543.85      6933952.75      1454405.02      6933828.00
      1451238.71      6933980.44
#Sta/Elev= 30
  1840.3 1795.61  2943.7 1792.18  3680.7 1790.97  3710.4 1790.14  3736.6 1792.06
  3771.3 1792.27  3849.8 1790.11  3850.3 1789.61  3864.8 1790.11  3877.8 1791.36
  3905.9 1791.70  3997.4 1791.21  4055.3 1791.22  4357.9 1790.80  4441.7 1791.95
  4488.2 1791.19  4534.0 1791.77  4708.3 1790.63  4901.8 1791.36  4933.9 1790.95
  4949.7 1792.35  4964.6 1791.07  5079.5 1791.10  5265.0 1791.62  5679.5 1791.49
  6512.7 1793.67  6869.1 1792.55  7113.4 1793.40  7700.5 1792.62  9312.2 1792.91
#Mann=10,-1,0
  1840.3   0.045       0  3680.7   0.035       0  3849.8   0.045       0
  3864.8   0.035       0  3997.4   0.045       0  4055.3   0.035       0
  4488.2    0.07       0  4901.8   0.045       0  5079.5    0.07       0
  5265.0   0.045       0
Bank Sta=3849.8,3864.8
Exp/Cntr=0.3,0.1

Type RM Length L Ch R = 1,7170,871,871,871
BEGIN DESCRIPTION:
Clear Fork Trib11 8.0
END DESCRIPTION:
XS GIS Cut Line= 5
      1457013.51      6936152.34      1456798.72      6934136.28
      1455578.05      6933814.29      1453825.99      6933355.60
      1451879.06      6933839.63
#Sta/Elev= 30
  1710.1 1795.18  2023.8 1793.38  3580.6 1790.97  3595.0 1791.29  3615.2 1789.84
  3645.3 1792.01  3665.4 1791.28  3675.5 1790.13  3689.0 1791.23  3737.6 1790.28
  4313.9 1789.93  4434.3 1789.89  4465.4 1790.49  4475.7 1791.38  4513.1 1790.59
  4614.2 1789.90  5964.5 1790.73  6181.6 1789.94  6309.4 1788.20  6504.9 1787.69
  6505.4 1787.19  6519.9 1787.69  7103.0 1790.09  7129.2 1790.45  7183.1 1788.50
  7234.2 1788.53  7896.6 1789.50  7969.3 1789.64  8503.4 1792.60  8817.3 1792.54
#Mann=11,-1,0
  1710.1   0.045       0  3580.6   0.035       0  3689.0   0.045       0
  4313.9   0.035       0  4513.1   0.045       0  6504.9   0.045       0
  6519.9   0.045       0  7103.0    0.07       0  7234.2   0.045       0
  7896.6    0.07       0  7969.3   0.045       0
Bank Sta=6504.9,6519.9
Exp/Cntr=0.3,0.1

Type RM Length L Ch R = 1,6299,455,455,455
BEGIN DESCRIPTION:
Clear Fork Trib11 7.0
END DESCRIPTION:
XS GIS Cut Line= 4
      1457499.86      6934274.95      1456105.00      6933288.00
      1454841.37      6932701.21      1454130.27      6931648.04
#Sta/Elev= 30
  3290.7 1789.44  3945.9 1790.04  4317.5 1788.97  4716.6 1788.51  4804.9 1788.59
  4849.3 1789.61  4874.6 1789.06  4977.2 1788.69  5368.1 1789.51  5436.8 1790.07
  5465.2 1791.35  5488.1 1790.91  5505.5 1789.91  5528.4 1789.54  5728.1 1789.63
  6082.6 1789.04  6234.3 1788.25  6385.8 1788.34  6443.7 1787.58  6557.7 1787.92
  6622.0 1787.48  6622.5 1786.98  6636.6 1786.98  6637.1 1787.48  6845.4 1789.09
  6962.3 1789.31  7169.1 1788.98  7184.1 1788.55  7328.0 1788.86  7663.4 1788.33
#Mann=5,-1,0
  3290.7   0.045       0  4716.6   0.035       0  4874.6   0.045       0
  6622.0   0.045       0  6637.1   0.045       0
Bank Sta=6622,6637.1
Exp/Cntr=0.3,0.1

Type RM Length L Ch R = 1,5844,452,452,452
BEGIN DESCRIPTION:
Clear Fork Trib11 6.0
END DESCRIPTION:
XS GIS Cut Line= 4
      1458128.29      6934413.90      1456305.00      6932938.00
      1455676.16      6932154.20      1454937.56      6930497.00
#Sta/Elev= 30
  2649.4 1788.40  3971.2 1789.06  4454.8 1788.33  4711.4 1786.81  4909.7 1786.88
  4959.2 1788.04  5002.4 1787.20  5251.6 1787.70  5287.2 1786.71  5528.9 1785.92
  5671.3 1786.72  5692.1 1785.94  5741.7 1786.15  5749.7 1786.99  5828.1 1788.11
  5912.9 1787.73  5919.3 1786.67  5948.1 1785.77  6360.9 1787.39  7109.7 1787.18
  7148.1 1788.02  7165.8 1786.74  7189.0 1786.40  7321.4 1785.54  7510.9 1784.98
  7511.4 1784.48  7526.0 1784.98  7552.1 1785.32  7681.0 1785.17  7814.4 1787.00
#Mann=6,-1,0
  2649.4   0.045       0  7109.7    0.07       0  7321.4   0.045       0
  7510.9   0.045       0  7526.0   0.045       0  7552.1   0.035       0
Bank Sta=7510.9,7526
Exp/Cntr=0.3,0.1

Type RM Length L Ch R = 1,5392,1220,1220,1220
BEGIN DESCRIPTION:
Clear Fork Trib11 5.0
END DESCRIPTION:
XS GIS Cut Line= 3
      1458290.35      6934373.35      1456505.00      6932588.00
      1455250.04      6930356.32
#Sta/Elev= 30
  2474.9 1788.00  3628.0 1789.00  4207.8 1787.85  4830.1 1785.04  4886.6 1785.35
  5110.4 1784.75  5137.8 1785.48  5191.3 1785.16  5872.1 1786.65  6255.2 1786.69
  6314.5 1786.20  6482.9 1786.18  6541.5 1786.57  6548.6 1787.12  6557.4 1786.62
  6590.7 1786.45  6597.3 1786.38  6714.9 1786.52  6845.0 1786.45  6939.1 1786.10
  6975.3 1785.67  7027.2 1784.84  7137.6 1784.26  7138.1 1783.76  7152.2 1783.76
  7152.7 1784.26  7270.1 1784.28  7409.0 1785.74  7509.4 1785.45  7560.1 1785.87
#Mann=11,-1,0
  2474.9   0.045       0  6482.9    0.07       0  6590.7   0.045       0
  6597.3    0.07       0  6714.9   0.035       0  6845.0    0.07       0
  6939.1   0.035       0  6975.3    0.07       0  7137.6   0.045       0
  7152.7    0.07       0  7509.4   0.035       0
Bank Sta=7137.6,7152.7
Exp/Cntr=0.3,0.1

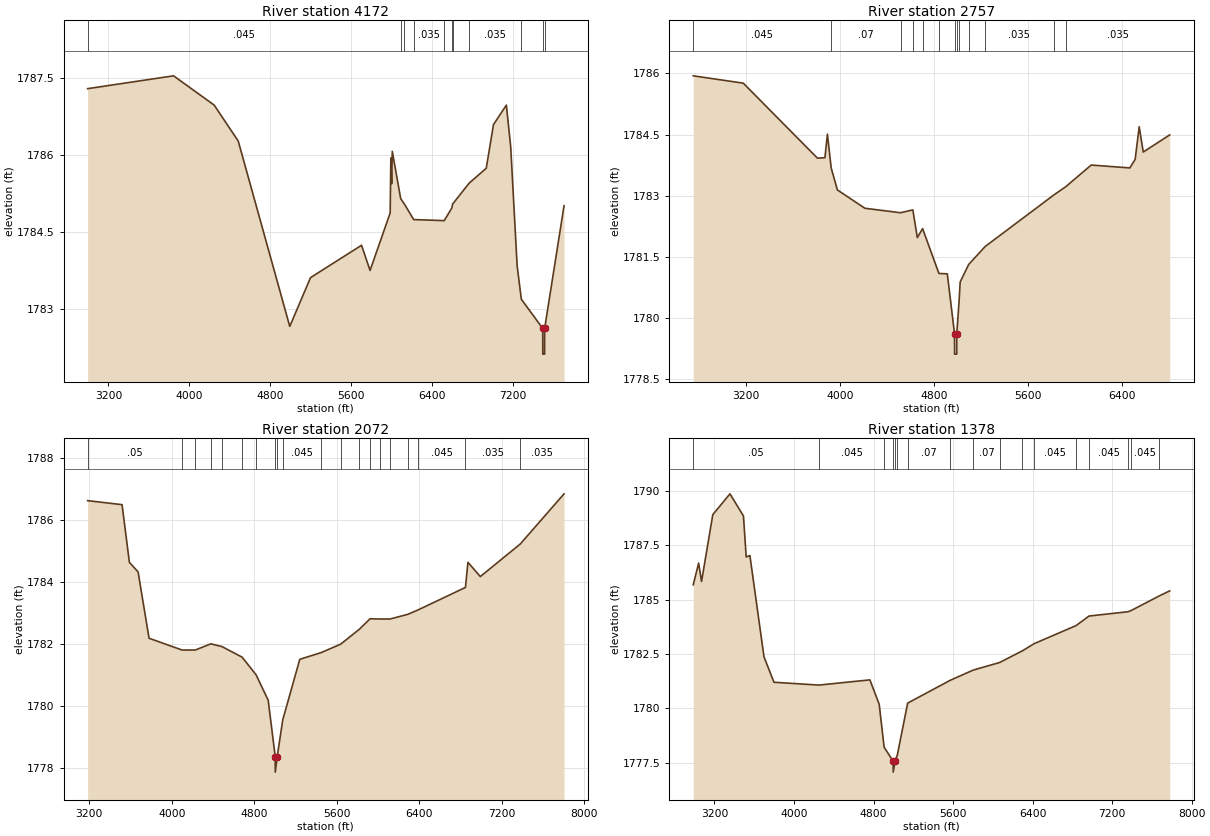
Type RM Length L Ch R = 1,4172,1415,1415,1415
BEGIN DESCRIPTION:
Mapping XS c1318bbe
END DESCRIPTION:
XS GIS Cut Line= 3
      1458406.03      6933893.02      1457503.27      6932148.26
      1455406.88      6930372.47
#Sta/Elev= 30
  2994.0 1787.30  3844.1 1787.55  4245.7 1786.98  4483.6 1786.28  4993.3 1782.67
  5198.7 1783.62  5703.0 1784.25  5787.5 1783.76  5986.4 1784.88  5992.9 1785.95
  6000.7 1785.45  6007.2 1786.08  6090.1 1785.16  6127.9 1785.05  6219.0 1784.75
  6521.1 1784.73  6597.2 1784.98  6603.1 1785.05  6767.2 1785.46  6936.6 1785.75
  7008.0 1786.60  7135.4 1786.98  7178.3 1786.17  7242.0 1783.85  7283.3 1783.20
  7495.0 1782.63  7495.5 1782.13  7513.6 1782.13  7514.1 1782.63  7705.9 1785.02
#Mann=11,-1,0
  2994.0   0.045       0  6090.1    0.07       0  6127.9   0.045       0
  6219.0   0.035       0  6521.1   0.045       0  6597.2   0.035       0
  6603.1   0.045       0  6767.2   0.035       0  7283.3    0.07       0
  7495.0   0.045       0  7514.1    0.07       0
Bank Sta=7495,7514.1
Exp/Cntr=0.3,0.1

Type RM Length L Ch R = 1,2757,685,685,685
BEGIN DESCRIPTION:
Clear Fork Trib11 4.0
END DESCRIPTION:
XS GIS Cut Line= 3
      1459919.37      6932854.64      1458305.00      6931288.00
      1456572.19      6930814.15
#Sta/Elev= 30
  2754.9 1785.94  3179.8 1785.76  3809.3 1783.92  3873.0 1783.93  3894.2 1784.51
  3926.2 1783.68  3979.0 1783.14  4212.4 1782.69  4515.2 1782.58  4619.7 1782.65
  4657.9 1781.97  4702.7 1782.19  4841.1 1781.09  4912.5 1781.08  4973.7 1779.61
  4974.2 1779.11  4992.4 1779.11  4992.9 1779.61  5012.3 1780.41  5021.7 1780.88
  5093.7 1781.31  5233.3 1781.75  5814.2 1783.01  5918.8 1783.22  6134.5 1783.75
  6462.6 1783.68  6507.7 1783.89  6541.9 1784.69  6576.4 1784.07  6800.9 1784.49
#Mann=13,-1,0
  2754.9   0.045       0  3926.2    0.07       0  4515.2    0.05       0
  4619.7    0.07       0  4702.7    0.05       0  4841.1   0.045       0
  4973.7   0.045       0  4992.9   0.045       0  5012.3    0.05       0
  5093.7   0.045       0  5233.3   0.035       0  5814.2   0.045       0
  5918.8   0.035       0
Bank Sta=4973.7,4992.9
Exp/Cntr=0.3,0.1

Type RM Length L Ch R = 1,2072,694,694,694
BEGIN DESCRIPTION:
Clear Fork Trib11 3.0
END DESCRIPTION:
XS GIS Cut Line= 3
      1460069.52      6931984.86      1458633.13      6930712.31
      1455933.14      6930712.31
#Sta/Elev= 30
  3184.0 1786.62  3518.0 1786.49  3589.1 1784.63  3673.5 1784.32  3779.7 1782.18
  4099.7 1781.80  4228.8 1781.80  4378.3 1782.00  4486.8 1781.91  4681.8 1781.57
  4817.4 1781.00  4934.8 1780.18  5002.9 1778.36  5003.4 1777.86  5022.2 1778.36
  5076.1 1779.55  5241.1 1781.50  5450.6 1781.72  5637.8 1781.99  5818.5 1782.47
  5922.9 1782.81  6016.5 1782.80  6115.5 1782.80  6286.8 1782.95  6385.5 1783.09
  6847.1 1783.82  6871.1 1784.63  6991.1 1784.17  7378.4 1785.22  7803.0 1786.84
#Mann=20,-1,0
  3184.0    0.05       0  4099.7   0.035       0  4228.8   0.035       0
  4378.3   0.035       0  4486.8   0.045       0  4681.8   0.035       0
  4817.4   0.045       0  5002.9   0.045       0  5022.2   0.045       0
  5076.1   0.045       0  5450.6   0.035       0  5637.8   0.045       0
  5818.5   0.035       0  5922.9   0.045       0  6016.5   0.035       0
  6115.5   0.045       0  6286.8   0.035       0  6385.5   0.045       0
  6847.1   0.035       0  7378.4   0.035       0
Bank Sta=5002.9,5022.2
Exp/Cntr=0.3,0.1

Type RM Length L Ch R = 1,1378,985,985,985
BEGIN DESCRIPTION:
Clear Fork Trib11 2.0
END DESCRIPTION:
XS GIS Cut Line= 3
      1460232.55      6931826.04      1458987.29      6930143.21
      1456288.66      6930143.21
#Sta/Elev= 30
  2986.9 1785.69  3041.0 1786.69  3070.3 1785.84  3183.5 1788.92  3356.2 1789.88
  3491.9 1788.86  3519.4 1786.97  3556.6 1787.04  3698.5 1782.37  3798.7 1781.20
  4251.2 1781.07  4763.4 1781.31  4857.0 1780.19  4906.7 1778.21  4997.6 1777.56
  4998.1 1777.06  5017.0 1777.56  5040.1 1777.86  5143.5 1780.24  5571.6 1781.29
  5802.4 1781.76  6068.6 1782.11  6298.3 1782.65  6416.8 1782.98  6837.2 1783.81
  6967.9 1784.25  7362.5 1784.45  7393.9 1784.51  7670.9 1785.17  7779.0 1785.41
#Mann=17,-1,0
  2986.9    0.05       0  4251.2   0.045       0  4906.7    0.07       0
  4997.6    0.07       0  5017.0    0.07       0  5040.1   0.045       0
  5143.5    0.07       0  5571.6   0.035       0  5802.4    0.07       0
  6068.6   0.045       0  6298.3    0.07       0  6416.8   0.045       0
  6837.2   0.035       0  6967.9   0.045       0  7362.5    0.07       0
  7393.9   0.045       0  7670.9    0.07       0
Bank Sta=4997.6,5017
Exp/Cntr=0.3,0.1