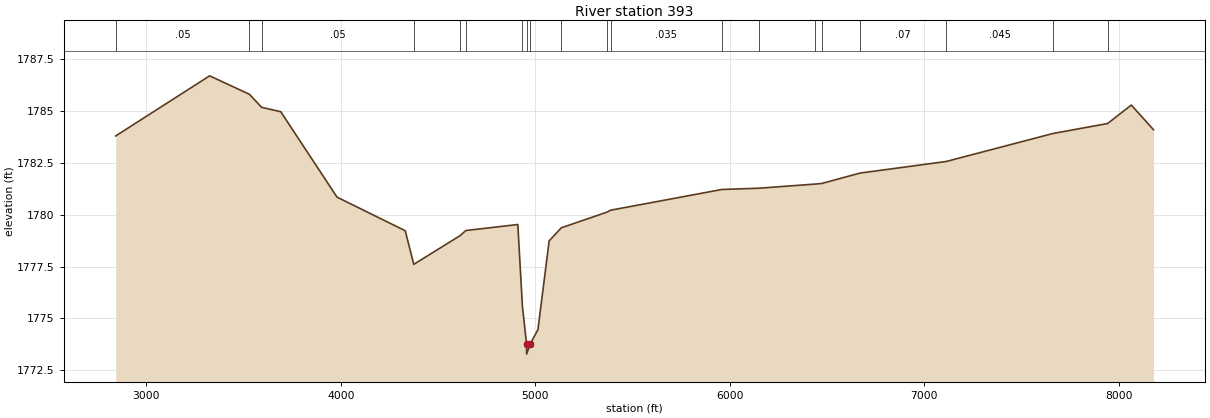
HEC-RAS study Clear Fork Trib11.prj: Clear Fork Trib11 Base Level Engineering

--- Clear Fork Trib11.g01 (geometry) --- (continued)

Type RM Length L Ch R = 1,393,0,0,0
BEGIN DESCRIPTION:
Clear Fork Trib11 1.0
END DESCRIPTION:
XS GIS Cut Line= 4
      1460610.51      6931861.93      1459877.30      6929853.21
      1459491.12      6929370.48      1456958.18      6929864.93
#Sta/Elev= 30
  2842.3 1783.80  3325.5 1786.70  3530.0 1785.81  3593.0 1785.18  3691.2 1784.97
  3980.7 1780.85  4331.3 1779.23  4375.4 1777.61  4612.9 1778.99  4643.1 1779.24
  4910.4 1779.53  4934.0 1775.59  4955.2 1773.78  4955.7 1773.28  4974.6 1773.78
  5013.8 1774.46  5071.5 1778.74  5133.8 1779.37  5369.8 1780.13  5387.6 1780.22
  5960.1 1781.22  6150.4 1781.28  6438.8 1781.48  6473.9 1781.51  6670.0 1782.01
  7113.7 1782.57  7662.8 1783.92  7943.6 1784.40  8065.4 1785.29  8179.6 1784.10
#Mann=20,-1,0
  2842.3    0.05       0  3530.0   0.035       0  3593.0    0.05       0
  4375.4   0.045       0  4612.9    0.05       0  4643.1   0.045       0
  4934.0    0.07       0  4955.2    0.07       0  4974.6    0.07       0
  5133.8   0.045       0  5369.8    0.07       0  5387.6   0.035       0
  5960.1    0.07       0  6150.4   0.035       0  6438.8    0.07       0
  6473.9   0.035       0  6670.0    0.07       0  7113.7   0.045       0
  7662.8   0.035       0  7943.6   0.045       0
Bank Sta=4955.2,4974.6
Exp/Cntr=0.3,0.1

Chan Stop Cuts=-1