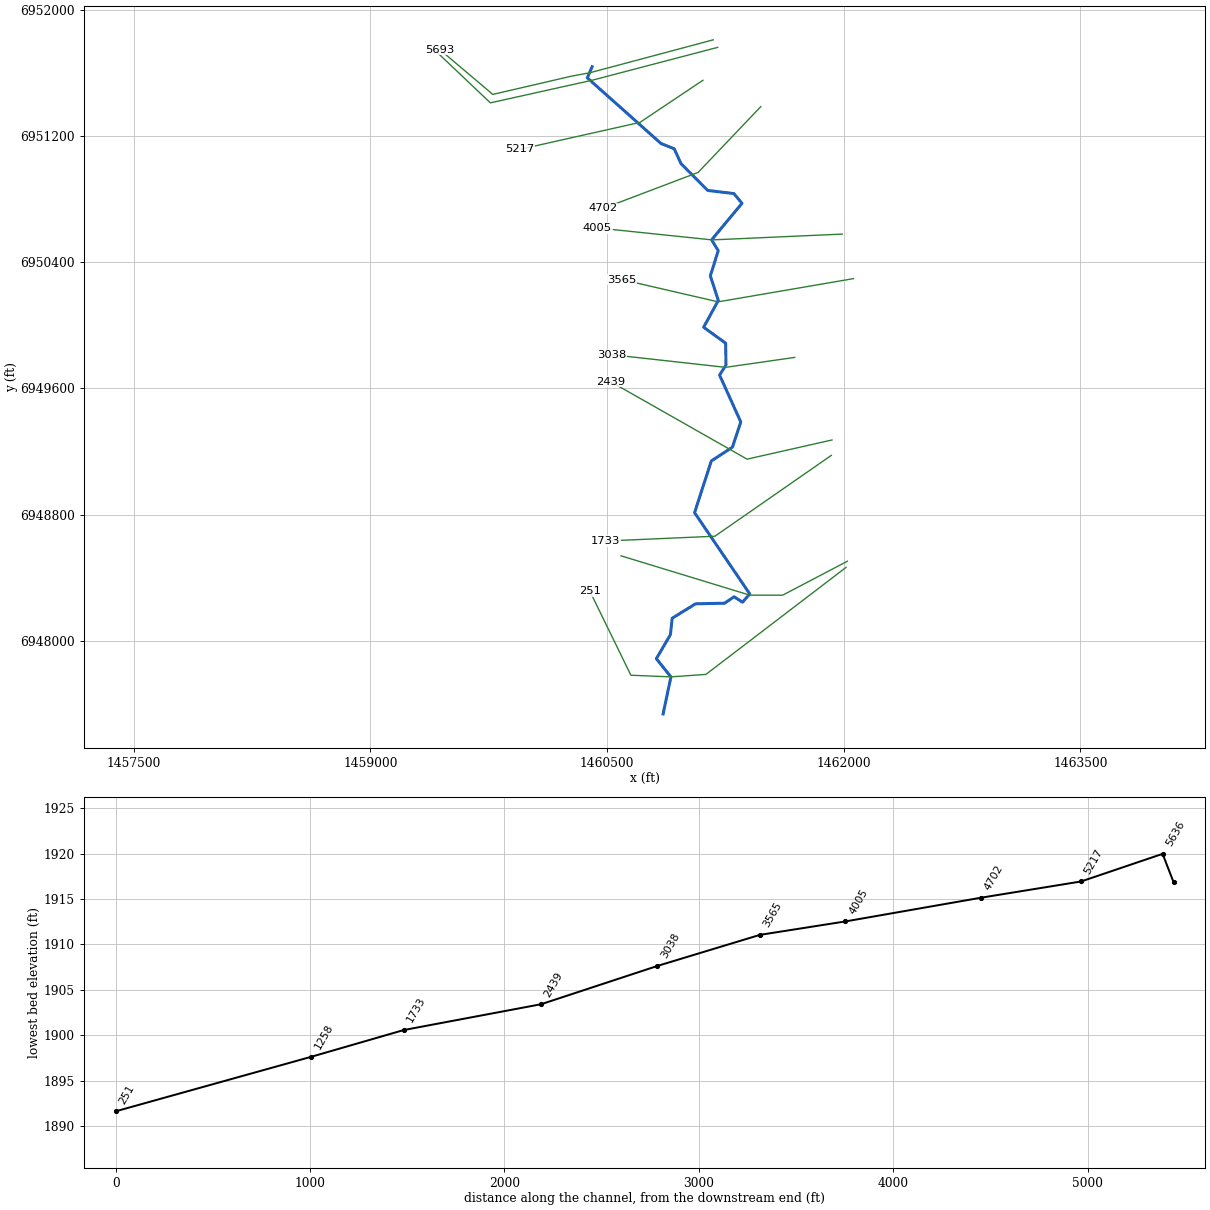
--- Clear Fork Trib11_1.prj (project) ---

Proj Title=Clear Fork Trib11_1 Base Level Engineering
Current Plan=p01
Default Exp/Contr=0.3,0.1
English Units
Geom File=g01
Flow File=f01
Plan File=p01
BEGIN DESCRIPTION:
Clear Fork Trib11_1
END DESCRIPTION:

--- Clear Fork Trib11_1.p01 (plan) ---

Plan Title=Multiple Run
Short Identifier=Multiple
Geom File=g01
Flow File=f01
Subcritical Flow
K Sum by GR= 0
Std Step Tol= 0.01
Critical Tol= 0.01
Num of Std Step Trials= 20
Max Error Tol= 0.3
Flow Tol Ratio= 0.001
Split Flow NTrial= 30
Split Flow Tol= 0.02
Split Flow Ratio= 0.02
Log Output Level= 0
Friction Slope Method= 1
Unsteady Friction Slope Method= 2
Unsteady Bridges Friction Slope Method= 1
Parabolic Critical Depth
Global Vel Dist=  1 , 1 , 1
Global Log Level= 0
CheckData=True
Encroach Param= -1, 0, 0, 0
BEGIN DESCRIPTION:
Multiple Run
END DESCRIPTION:

--- Clear Fork Trib11_1.f01 (steady flow) ---

Flow Title=Multiple
Number of Profiles=7
Profile Names=10-year,25-year,50-year,1pct_min,100-year,1pct_plu,500-year
River Rch & RM= Clear Fork Trib1,Reach-1,5693
     201     273     330     198     396     790     578
River Rch & RM= Clear Fork Trib1,Reach-1,5217
     230     315     383     232     462     923     681
Boundary for River Rch & Prof#=Clear Fork Trib1,Reach-1,1
Up Type=0
Dn Type=3
Dn Slope=0.005
Boundary for River Rch & Prof#=Clear Fork Trib1,Reach-1,2
Up Type=0
Dn Type=3
Dn Slope=0.005
Boundary for River Rch & Prof#=Clear Fork Trib1,Reach-1,3
Up Type=0
Dn Type=3
Dn Slope=0.005
Boundary for River Rch & Prof#=Clear Fork Trib1,Reach-1,4
Up Type=0
Dn Type=3
Dn Slope=0.005
Boundary for River Rch & Prof#=Clear Fork Trib1,Reach-1,5
Up Type=0
Dn Type=3
Dn Slope=0.005
Boundary for River Rch & Prof#=Clear Fork Trib1,Reach-1,6
Up Type=0
Dn Type=3
Dn Slope=0.005
Boundary for River Rch & Prof#=Clear Fork Trib1,Reach-1,7
Up Type=0
Dn Type=3
Dn Slope=0.005

--- Clear Fork Trib11_1.g01 (geometry) ---

Geom Title=Existing Conditions

River Reach=Clear Fork Trib1,Reach-1
Reach XY= 30
      1460405.00      6951638.00      1460374.35      6951568.00
      1460841.80      6951151.64      1460925.47      6951118.36
      1460968.49      6951024.45      1461137.86      6950854.28
      1461303.81      6950834.54      1461355.17      6950772.78
      1461162.80      6950541.42      1461204.48      6950472.78
      1461154.60      6950313.00      1461205.11      6950158.09
      1461112.20      6949987.70      1461251.56      6949886.75
      1461253.63      6949748.44      1461213.08      6949684.70
      1461347.47      6949388.01      1461294.61      6949227.90
      1461160.73      6949140.55      1461054.50      6948812.96
      1461404.45      6948298.31      1461358.66      6948245.89
      1461305.11      6948280.19      1461244.57      6948239.38
      1461060.93      6948235.76      1460912.74      6948144.46
      1460901.17      6948039.59      1460812.30      6947887.92
      1460904.62      6947772.84      1460855.00      6947538.00

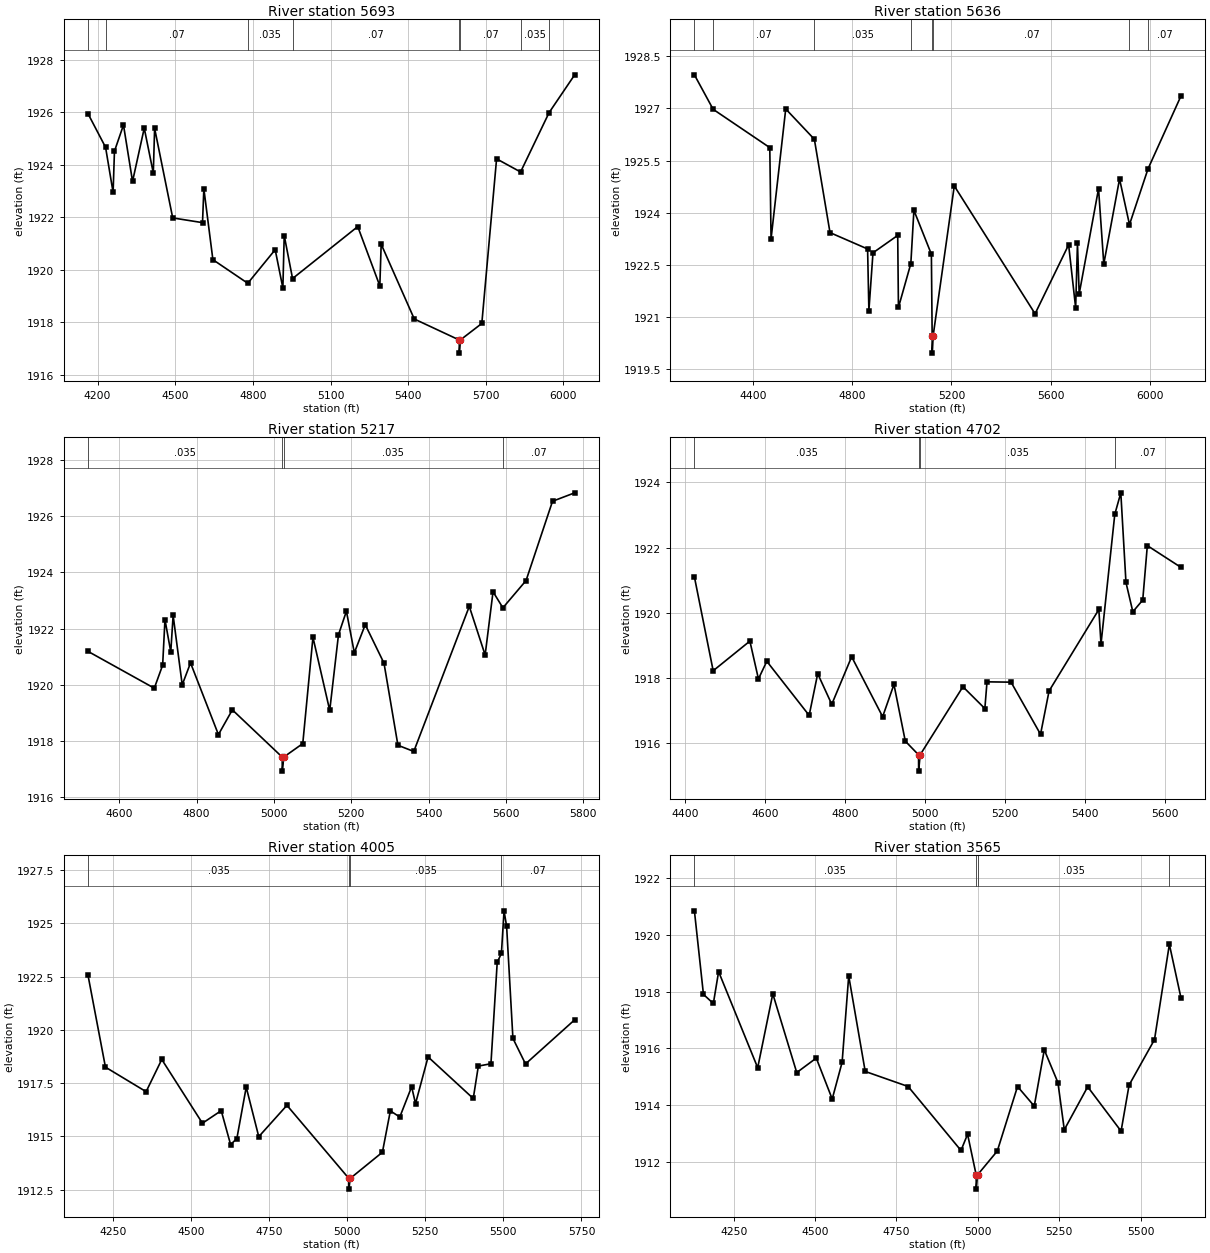
Type RM Length L Ch R = 1,5693,57,57,57
BEGIN DESCRIPTION:
Mapping XS 17ee5e4f
END DESCRIPTION:
XS GIS Cut Line= 5
      1461172.58      6951808.31      1460391.36      6951599.99
      1460274.18      6951578.28      1459775.62      6951462.62
      1459438.89      6951747.10
#Sta/Elev= 30
  4162.9 1925.94  4230.8 1924.66  4259.9 1922.94  4265.1 1924.51  4300.0 1925.51
  4335.0 1923.36  4380.2 1925.39  4415.2 1923.68  4420.3 1925.38  4490.2 1921.97
  4605.3 1921.79  4610.5 1923.08  4645.4 1920.38  4780.2 1919.48  4886.1 1920.76
  4915.8 1919.30  4921.0 1921.30  4953.2 1919.66  5205.1 1921.64  5290.4 1919.38
  5295.6 1920.97  5423.5 1918.12  5597.3 1917.32  5597.5 1916.82  5601.3 1917.32
  5684.4 1917.95  5741.5 1924.22  5834.2 1923.72  5944.3 1925.98  6043.2 1927.42
#Mann=8,-1,0
  4162.9   0.035       0  4230.8    0.07       0  4780.2   0.035       0
  4953.2    0.07       0  5597.3    0.07       0  5601.3    0.07       0
  5834.2   0.035       0  5944.3    0.07       0
Bank Sta=5597.3,5601.3
Exp/Cntr=0.3,0.1

Type RM Length L Ch R = 1,5636,419,419,419
BEGIN DESCRIPTION:
Mapping XS c44c80c3
END DESCRIPTION:
XS GIS Cut Line= 4
      1461200.81      6951760.57      1460404.39      6951552.24
      1459760.04      6951409.19      1459413.99      6951737.12
#Sta/Elev= 30
  4164.8 1927.96  4240.3 1926.97  4468.4 1925.87  4473.5 1923.25  4532.6 1926.98
  4647.9 1926.11  4710.9 1923.43  4862.3 1922.96  4867.5 1921.19  4884.0 1922.85
  4983.6 1923.35  4986.5 1921.28  5036.4 1922.54  5048.8 1924.07  5119.2 1922.81
  5122.3 1920.47  5122.6 1919.97  5126.3 1920.47  5211.4 1924.77  5536.8 1921.10
  5671.9 1923.08  5700.2 1921.27  5707.5 1923.12  5714.4 1921.67  5792.4 1924.69
  5813.5 1922.53  5877.0 1924.97  5917.0 1923.66  5991.6 1925.26  6124.8 1927.36
#Mann=8,-1,0
  4164.8   0.035       0  4240.3    0.07       0  4647.9   0.035       0
  5036.4    0.07       0  5122.3   0.035       0  5126.3    0.07       0
  5917.0   0.035       0  5991.6    0.07       0
Bank Sta=5122.3,5126.3
Exp/Cntr=0.3,0.1

Type RM Length L Ch R = 1,5217,515,515,515
BEGIN DESCRIPTION:
Mapping XS 5476ac0e
END DESCRIPTION:
XS GIS Cut Line= 3
      1461107.51      6951552.24      1460708.21      6951285.32
      1459949.06      6951115.09
#Sta/Elev= 30
  4519.3 1921.19  4690.7 1919.88  4712.3 1920.70  4718.3 1922.32  4733.3 1921.17
  4739.4 1922.47  4762.9 1920.00  4784.4 1920.78  4856.5 1918.23  4892.5 1919.11
  5021.4 1917.43  5021.6 1916.93  5025.4 1917.43  5074.6 1917.91  5100.9 1921.69
  5144.3 1919.09  5166.9 1921.78  5187.4 1922.62  5207.9 1921.14  5236.1 1922.14
  5284.6 1920.77  5320.6 1917.85  5361.6 1917.63  5505.1 1922.79  5546.1 1921.06
  5566.5 1923.31  5592.0 1922.74  5651.9 1923.71  5720.3 1926.53  5777.6 1926.83
#Mann=4,-1,0
  4519.3   0.035       0  5021.4   0.035       0  5025.4   0.035       0
  5592.0    0.07       0
Bank Sta=5021.4,5025.4
Exp/Cntr=0.3,0.1

Type RM Length L Ch R = 1,4702,697,697,697
BEGIN DESCRIPTION:
Mapping XS d1de9e0d
END DESCRIPTION:
XS GIS Cut Line= 3
      1461474.27      6951385.15      1461077.13      6950968.47
      1460475.99      6950740.61
#Sta/Elev= 30
  4423.0 1921.10  4470.0 1918.22  4561.9 1919.13  4583.3 1917.97  4604.3 1918.51
  4710.3 1916.85  4731.7 1918.13  4766.9 1917.19  4816.7 1918.65  4894.3 1916.81
  4922.6 1917.80  4951.0 1916.06  4984.2 1915.64  4984.4 1915.14  4988.2 1915.64
  5095.3 1917.73  5150.2 1917.06  5155.6 1917.88  5215.8 1917.87  5289.6 1916.27
  5311.0 1917.60  5435.6 1920.10  5441.0 1919.04  5475.5 1923.02  5490.6 1923.68
  5503.5 1920.93  5520.7 1920.03  5545.5 1920.39  5557.0 1922.06  5641.5 1921.39
#Mann=4,-1,0
  4423.0   0.035       0  4984.2   0.035       0  4988.2   0.035       0
  5475.5    0.07       0
Bank Sta=4984.2,4988.2
Exp/Cntr=0.3,0.1

Type RM Length L Ch R = 1,4005,440,440,440
BEGIN DESCRIPTION:
Mapping XS fa6de608
END DESCRIPTION:
XS GIS Cut Line= 3
      1461990.74      6950577.85      1461166.10      6950540.96
      1460438.50      6950616.75
#Sta/Elev= 30
  4171.2 1922.56  4227.0 1918.25  4357.1 1917.10  4407.2 1918.61  4537.3 1915.62
  4597.4 1916.21  4627.4 1914.62  4647.4 1914.90  4677.4 1917.31  4717.5 1914.99
  4807.6 1916.46  5005.8 1913.03  5006.0 1912.53  5009.9 1913.03  5113.1 1914.26
  5138.5 1916.20  5168.7 1915.91  5206.6 1917.33  5219.0 1916.54  5259.2 1918.73
  5403.7 1916.78  5420.0 1918.30  5460.3 1918.41  5480.4 1923.17  5493.8 1923.58
  5502.2 1925.58  5510.5 1924.85  5530.6 1919.60  5570.9 1918.40  5728.2 1920.47
#Mann=4,-1,0
  4171.2   0.035       0  5005.8   0.035       0  5009.9   0.035       0
  5493.8    0.07       0
Bank Sta=5005.8,5009.9
Exp/Cntr=0.3,0.1

Type RM Length L Ch R = 1,3565,527,527,527
BEGIN DESCRIPTION:
Clear Fork Trib11_1 4.0
END DESCRIPTION:
XS GIS Cut Line= 3
      1462062.39      6950295.73      1461203.91      6950148.54
      1460595.36      6950289.22
#Sta/Elev= 30
  4129.0 1920.84  4156.8 1917.90  4187.2 1917.58  4203.4 1918.70  4323.5 1915.32
  4369.9 1917.92  4443.5 1915.15  4503.5 1915.66  4552.5 1914.22  4582.9 1915.51
  4603.2 1918.55  4653.9 1915.19  4785.8 1914.66  4948.2 1912.41  4968.5 1912.98
  4994.9 1911.55  4995.1 1911.05  4999.0 1911.55  5059.8 1912.39  5122.0 1914.66
  5173.4 1913.97  5204.2 1915.95  5246.1 1914.80  5265.7 1913.14  5337.6 1914.65
  5440.2 1913.09  5464.8 1914.71  5542.9 1916.31  5588.6 1919.66  5624.6 1917.76
#Mann=4,-1,0
  4129.0   0.035       0  4994.9   0.035       0  4999.0   0.035       0
  5588.6    0.07       0
Bank Sta=4994.9,4999
Exp/Cntr=0.3,0.1

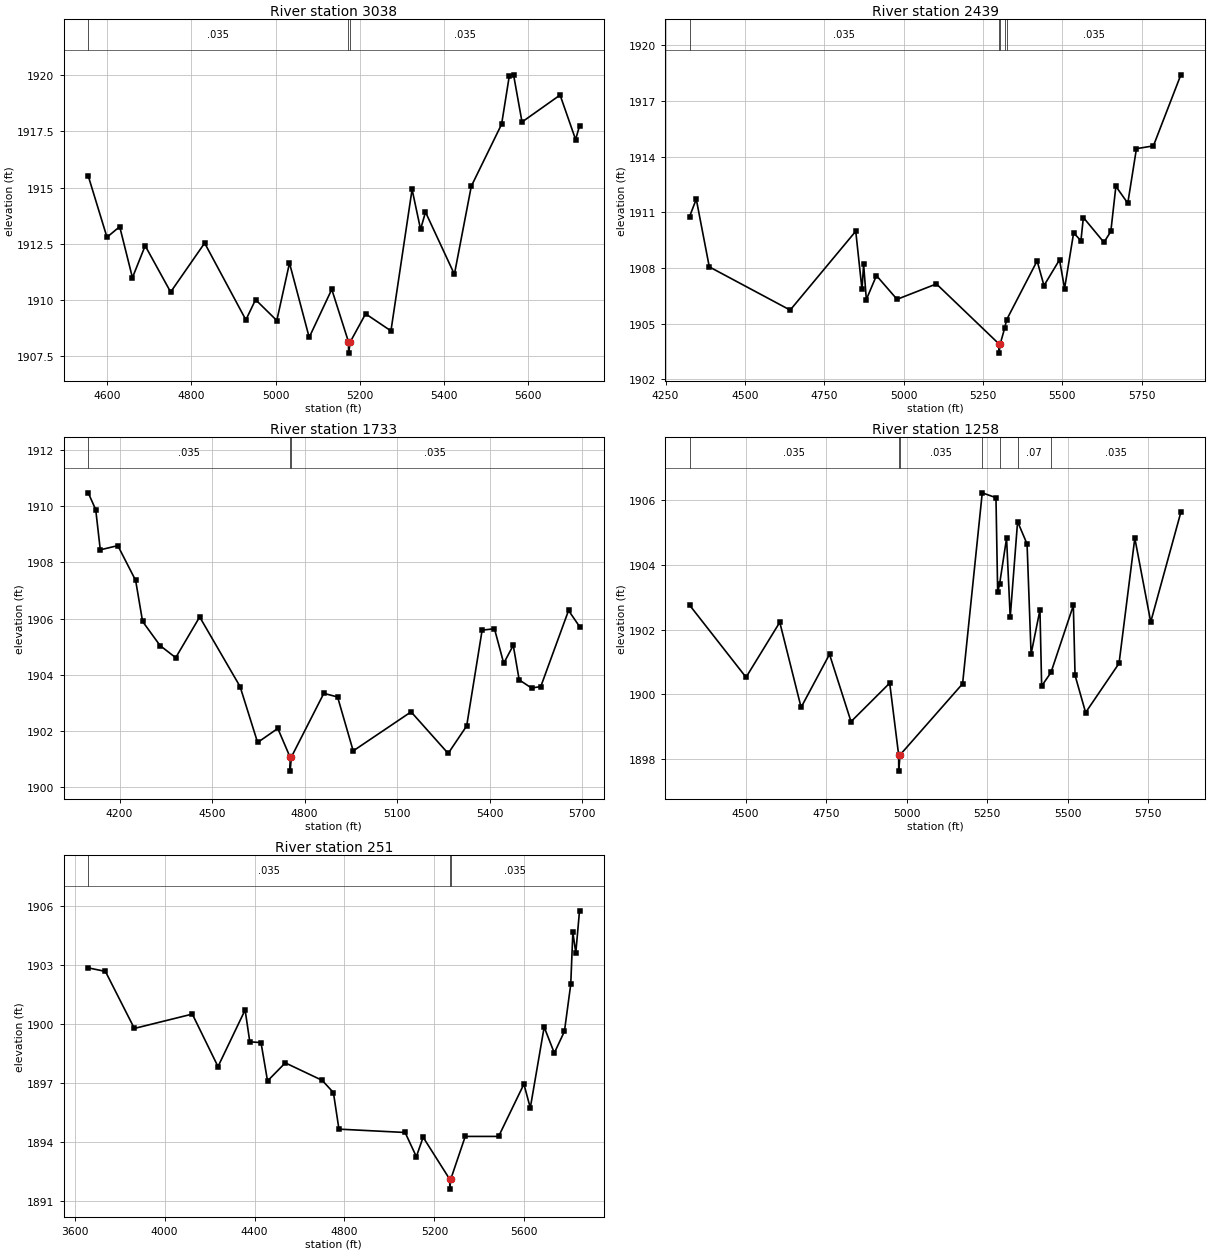
Type RM Length L Ch R = 1,3038,599,599,599
BEGIN DESCRIPTION:
Mapping XS 8b9cafd3
END DESCRIPTION:
XS GIS Cut Line= 3
      1461689.15      6949796.61      1461250.74      6949733.67
      1460529.08      6949813.85
#Sta/Elev= 30
  4554.3 1915.52  4598.9 1912.79  4629.2 1913.26  4659.5 1910.99  4689.8 1912.41
  4750.4 1910.35  4831.3 1912.53  4929.4 1909.11  4952.5 1910.01  5003.0 1909.08
  5033.2 1911.64  5080.1 1908.33  5133.8 1910.47  5173.6 1908.13  5173.9 1907.63
  5177.8 1908.13  5214.3 1909.38  5274.6 1908.62  5324.9 1914.92  5345.1 1913.14
  5356.8 1913.91  5425.6 1911.14  5465.8 1915.06  5537.9 1917.82  5556.4 1919.99
  5566.4 1920.02  5586.5 1917.92  5677.1 1919.12  5714.0 1917.14  5723.3 1917.74
#Mann=3,-1,0
  4554.3   0.035       0  5173.6   0.035       0  5177.8   0.035       0
Bank Sta=5173.6,5177.8
Exp/Cntr=0.3,0.1

Type RM Length L Ch R = 1,2439,706,706,706
BEGIN DESCRIPTION:
Mapping XS b645f790
END DESCRIPTION:
XS GIS Cut Line= 3
      1461925.61      6949273.59      1461387.46      6949152.07
      1460521.22      6949643.66
#Sta/Elev= 30
  4325.6 1910.77  4346.7 1911.71  4387.7 1908.06  4642.5 1905.73  4849.1 1909.98
  4868.8 1906.84  4873.9 1908.20  4882.5 1906.30  4914.3 1907.59  4979.2 1906.31
  5103.2 1907.14  5300.1 1903.91  5300.4 1903.41  5304.3 1903.91  5318.0 1904.74
  5324.5 1905.21  5420.5 1908.38  5442.1 1907.05  5491.1 1908.44  5507.0 1906.89
  5535.5 1909.89  5558.5 1909.47  5566.2 1910.72  5631.0 1909.38  5652.7 1909.97
  5668.6 1912.40  5706.1 1911.49  5733.4 1914.43  5786.8 1914.58  5873.3 1918.41
#Mann=5,-1,0
  4325.6   0.035       0  5300.1   0.035       0  5304.3   0.035       0
  5318.0    0.07       0  5324.5   0.035       0
Bank Sta=5300.1,5304.3
Exp/Cntr=0.3,0.1

Type RM Length L Ch R = 1,1733,475,475,475
BEGIN DESCRIPTION:
Mapping XS 1d175809
END DESCRIPTION:
XS GIS Cut Line= 3
      1461921.28      6949175.91      1461183.47      6948663.79
      1460489.56      6948633.43
#Sta/Elev= 30
  4098.4 1910.48  4122.7 1909.88  4137.5 1908.45  4194.3 1908.60  4252.1 1907.36
  4274.6 1905.90  4331.4 1905.04  4382.0 1904.61  4459.7 1906.06  4590.7 1903.58
  4647.5 1901.59  4713.0 1902.09  4752.7 1901.07  4753.0 1900.57  4756.9 1901.07
  4862.2 1903.34  4906.8 1903.21  4957.4 1901.29  5145.1 1902.68  5265.3 1901.20
  5325.3 1902.18  5375.4 1905.59  5415.4 1905.64  5445.4 1904.41  5476.3 1905.05
  5495.5 1903.82  5535.5 1903.53  5565.5 1903.58  5655.6 1906.29  5691.1 1905.72
#Mann=3,-1,0
  4098.4   0.035       0  4752.7   0.035       0  4756.9   0.035       0
Bank Sta=4752.7,4756.9
Exp/Cntr=0.3,0.1

Type RM Length L Ch R = 1,1258,1007,1007,1007
BEGIN DESCRIPTION:
Mapping XS 7b757df4
END DESCRIPTION:
XS GIS Cut Line= 4
      1462023.32      6948505.38      1461613.15      6948290.52
      1461404.82      6948290.52      1460588.33      6948539.59
#Sta/Elev= 30
  4326.3 1902.76  4501.6 1900.53  4606.3 1902.23  4672.5 1899.60  4760.7 1901.24
  4827.5 1899.16  4947.5 1900.35  4975.3 1898.13  4975.6 1897.63  4979.6 1898.13
  5173.8 1900.33  5234.8 1906.23  5277.4 1906.08  5282.7 1903.15  5288.8 1903.42
  5310.3 1904.83  5321.6 1902.38  5344.5 1905.34  5373.9 1904.65  5386.4 1901.25
  5413.9 1902.61  5419.2 1900.26  5448.2 1900.68  5517.6 1902.75  5522.9 1900.59
  5555.7 1899.44  5659.4 1900.96  5708.4 1904.83  5757.8 1902.24  5851.3 1905.63
#Mann=7,-1,0
  4326.3   0.035       0  4975.3   0.035       0  4979.6   0.035       0
  5234.8    0.07       0  5288.8   0.035       0  5344.5    0.07       0
  5448.2   0.035       0
Bank Sta=4975.3,4979.6
Exp/Cntr=0.3,0.1

Type RM Length L Ch R = 1,251,0,0,0
BEGIN DESCRIPTION:
Mapping XS 37cd5ab0
END DESCRIPTION:
XS GIS Cut Line= 5
      1462014.66      6948466.33      1461126.52      6947788.49
      1460904.62      6947772.84      1460650.82      6947783.29
      1460391.21      6948314.64
#Sta/Elev= 30
  3660.3 1902.87  3736.7 1902.69  3865.5 1899.79  4123.2 1900.52  4237.5 1897.85
  4358.1 1900.73  4378.9 1899.11  4428.8 1899.07  4457.8 1897.12  4536.8 1898.04
  4700.9 1897.15  4750.8 1896.53  4775.4 1894.67  5069.7 1894.50  5119.7 1893.27
  5149.8 1894.26  5268.2 1892.12  5268.5 1891.62  5272.6 1892.12  5337.2 1894.30
  5485.6 1894.30  5598.1 1896.96  5626.5 1895.75  5688.2 1899.86  5733.3 1898.54
  5778.3 1899.64  5806.4 1902.03  5815.8 1904.68  5828.9 1903.63  5845.4 1905.77
#Mann=3,-1,0
  3660.3   0.035       0  5268.2   0.035       0  5272.6   0.035       0
Bank Sta=5268.2,5272.6
Exp/Cntr=0.3,0.1

Chan Stop Cuts=-1