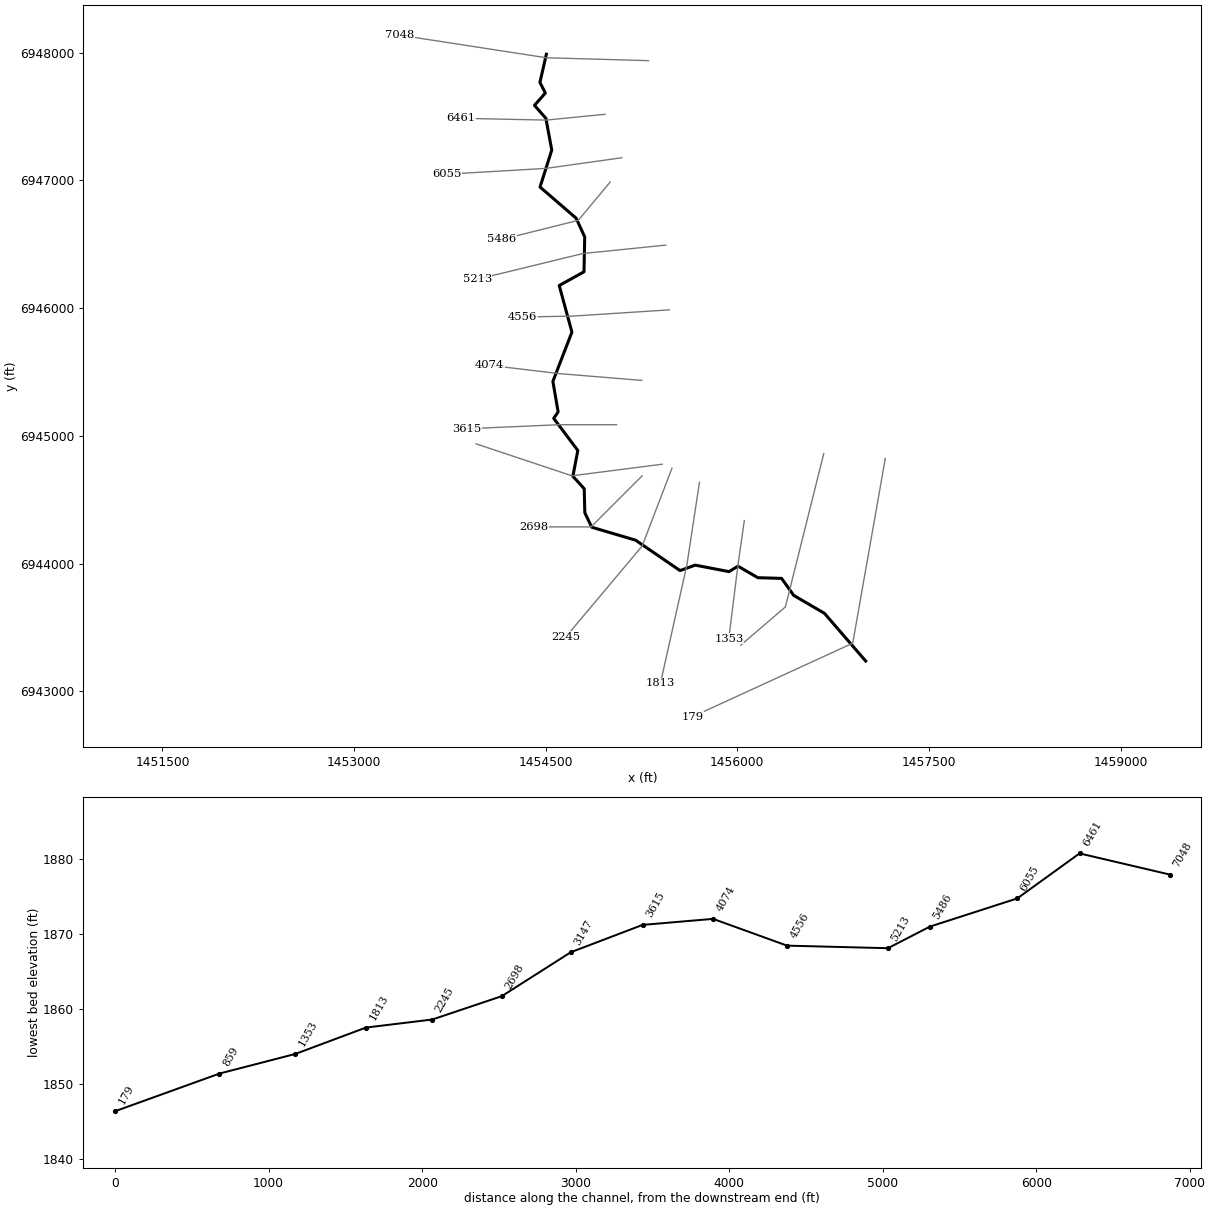
--- Clear Fork Trib11_2.prj (project) ---

Proj Title=Clear Fork Trib11_2 Base Level Engineering
Current Plan=p01
Default Exp/Contr=0.3,0.1
English Units
Geom File=g01
Flow File=f01
Plan File=p01
BEGIN DESCRIPTION:
Clear Fork Trib11_2
END DESCRIPTION:

--- Clear Fork Trib11_2.p01 (plan) ---

Plan Title=Multiple Run
Short Identifier=Multiple
Geom File=g01
Flow File=f01
Subcritical Flow
K Sum by GR= 0
Std Step Tol= 0.01
Critical Tol= 0.01
Num of Std Step Trials= 20
Max Error Tol= 0.3
Flow Tol Ratio= 0.001
Split Flow NTrial= 30
Split Flow Tol= 0.02
Split Flow Ratio= 0.02
Log Output Level= 0
Friction Slope Method= 1
Unsteady Friction Slope Method= 2
Unsteady Bridges Friction Slope Method= 1
Parabolic Critical Depth
Global Vel Dist=  1 , 1 , 1
Global Log Level= 0
CheckData=True
Encroach Param= -1, 0, 0, 0
BEGIN DESCRIPTION:
Multiple Run
END DESCRIPTION:

--- Clear Fork Trib11_2.f01 (steady flow) ---

Flow Title=Multiple
Number of Profiles=7
Profile Names=10-year,25-year,50-year,1pct_min,100-year,1pct_plu,500-year
River Rch & RM= Clear Fork Trib1,Reach-1,7048
     226     311     380     231     461     920     686
River Rch & RM= Clear Fork Trib1,Reach-1,6055
     304     425     525     322     642    1281     973
Boundary for River Rch & Prof#=Clear Fork Trib1,Reach-1,1
Up Type=0
Dn Type=3
Dn Slope=0.005
Boundary for River Rch & Prof#=Clear Fork Trib1,Reach-1,2
Up Type=0
Dn Type=3
Dn Slope=0.005
Boundary for River Rch & Prof#=Clear Fork Trib1,Reach-1,3
Up Type=0
Dn Type=3
Dn Slope=0.005
Boundary for River Rch & Prof#=Clear Fork Trib1,Reach-1,4
Up Type=0
Dn Type=3
Dn Slope=0.005
Boundary for River Rch & Prof#=Clear Fork Trib1,Reach-1,5
Up Type=0
Dn Type=3
Dn Slope=0.005
Boundary for River Rch & Prof#=Clear Fork Trib1,Reach-1,6
Up Type=0
Dn Type=3
Dn Slope=0.005
Boundary for River Rch & Prof#=Clear Fork Trib1,Reach-1,7
Up Type=0
Dn Type=3
Dn Slope=0.005

--- Clear Fork Trib11_2.g01 (geometry) ---

Geom Title=Existing Conditions

River Reach=Clear Fork Trib1,Reach-1
Reach XY= 30
      1454505.00      6947988.00      1454454.79      6947767.79
      1454497.15      6947684.59      1454412.11      6947588.00
      1454501.44      6947486.54      1454547.44      6947238.00
      1454455.60      6946948.62      1454738.37      6946704.71
      1454805.36      6946558.15      1454799.66      6946285.26
      1454605.86      6946177.69      1454705.23      6945812.93
      1454556.22      6945427.50      1454597.19      6945187.90
      1454562.55      6945138.00      1454751.26      6944886.44
      1454712.81      6944684.59      1454801.44      6944586.54
      1454806.20      6944398.50      1454860.71      6944285.41
      1455203.42      6944184.18      1455551.68      6943946.04
      1455670.06      6943988.69      1455934.84      6943937.90
      1456005.00      6943980.44      1456160.93      6943890.24
      1456346.70      6943884.93      1456441.76      6943751.62
      1456681.88      6943611.73      1457005.00      6943238.00

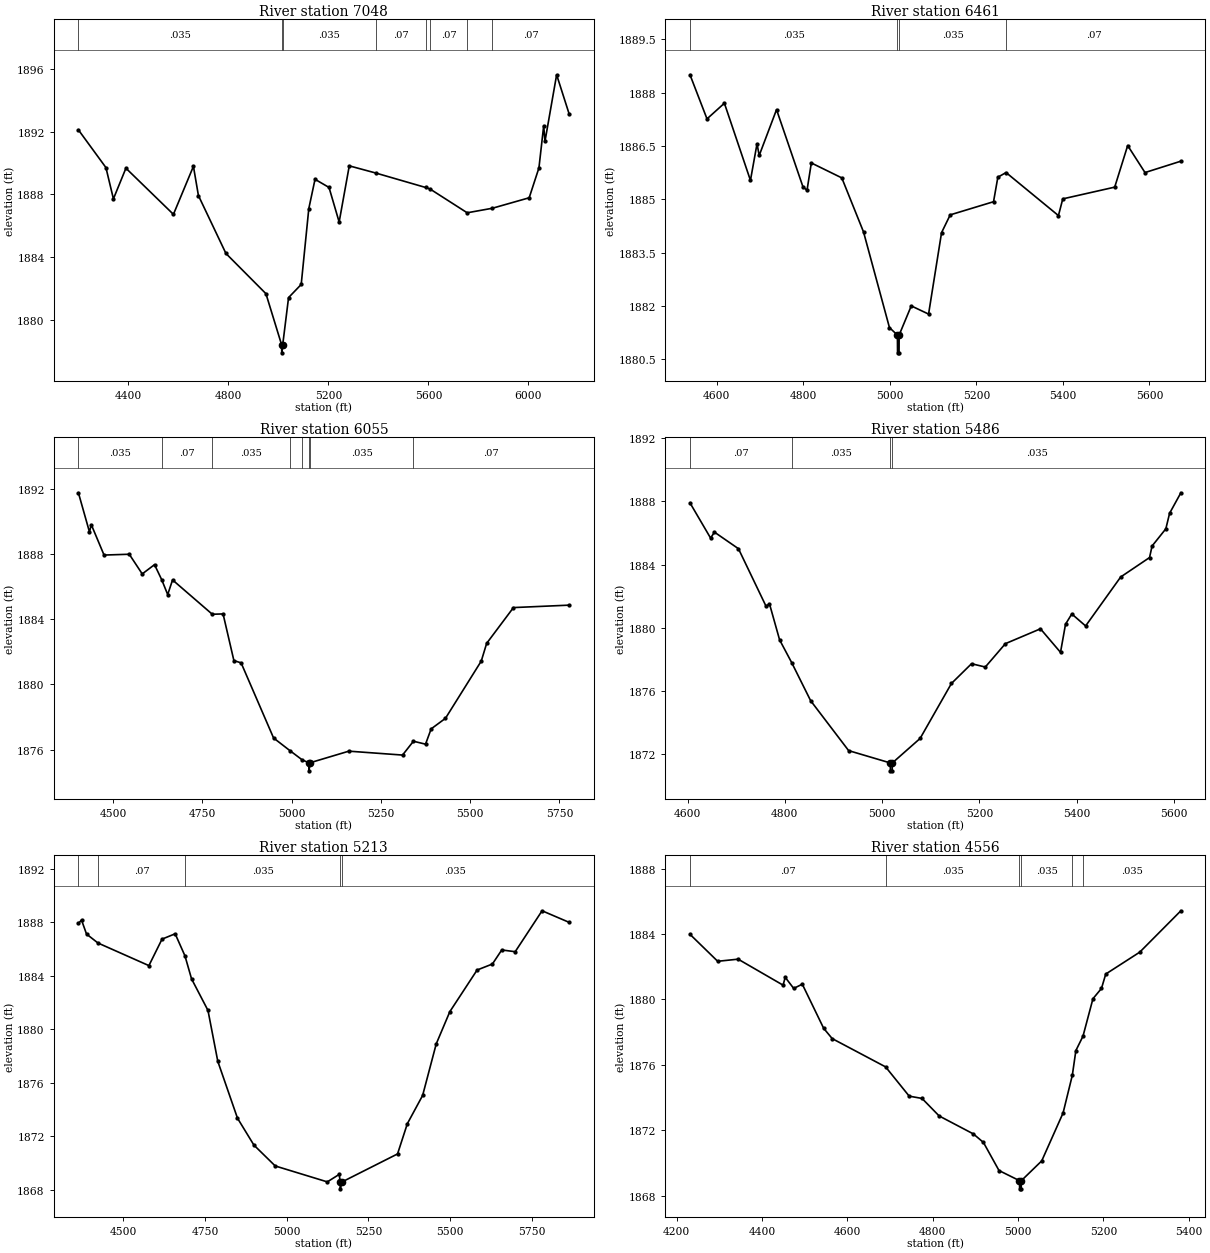
Type RM Length L Ch R = 1,7048,587,587,587
BEGIN DESCRIPTION:
Clear Fork Trib11_2 15.0
END DESCRIPTION:
XS GIS Cut Line= 3
      1455305.04      6947938.00      1454505.06      6947960.76
      1453355.04      6948137.99
#Sta/Elev= 30
  4199.7 1892.12  4309.8 1889.71  4339.8 1887.71  4389.8 1889.67  4579.9 1886.72
  4659.9 1889.79  4679.9 1887.92  4790.0 1884.22  4950.0 1881.65  5013.0 1878.37
  5013.2 1877.87  5017.0 1878.37  5040.5 1881.40  5091.1 1882.24  5121.5 1887.09
  5146.4 1888.96  5202.4 1888.44  5242.9 1886.23  5283.4 1889.82  5389.7 1889.36
  5588.4 1888.44  5606.6 1888.34  5755.2 1886.82  5855.8 1887.11  6003.2 1887.78
  6042.2 1889.69  6061.3 1892.39  6066.3 1891.38  6113.0 1895.64  6163.6 1893.11
#Mann=8,-1,0
  4199.7   0.035       0  5013.0   0.035       0  5017.0   0.035       0
  5389.7    0.07       0  5588.4   0.035       0  5606.6    0.07       0
  5755.2   0.035       0  5855.8    0.07       0
Bank Sta=5013,5017
Exp/Cntr=0.3,0.1

Type RM Length L Ch R = 1,6461,406,406,406
BEGIN DESCRIPTION:
Clear Fork Trib11_2 14.0
END DESCRIPTION:
XS GIS Cut Line= 3
      1454964.07      6947518.23      1454504.61      6947472.84
      1453832.15      6947486.98
#Sta/Elev= 30
  4538.3 1888.50  4577.6 1887.26  4617.8 1887.70  4678.0 1885.53  4693.2 1886.56
  4698.2 1886.23  4738.3 1887.52  4799.3 1885.35  4808.7 1885.25  4818.7 1886.02
  4889.1 1885.60  4939.3 1884.08  4999.2 1881.39  5017.6 1881.18  5017.9 1880.68
  5021.4 1880.68  5021.6 1881.18  5049.6 1882.00  5089.6 1881.77  5119.6 1884.06
  5139.6 1884.56  5239.7 1884.93  5249.7 1885.62  5268.7 1885.75  5389.7 1884.54
  5399.7 1885.01  5519.7 1885.34  5549.7 1886.51  5589.7 1885.75  5672.6 1886.07
#Mann=4,-1,0
  4538.3   0.035       0  5017.6   0.035       0  5021.6   0.035       0
  5268.7    0.07       0
Bank Sta=5017.6,5021.6
Exp/Cntr=0.3,0.1

Type RM Length L Ch R = 1,6055,569,569,569
BEGIN DESCRIPTION:
Mapping XS b6d13220
END DESCRIPTION:
XS GIS Cut Line= 3
      1455096.05      6947177.96      1454502.26      6947094.62
      1453728.99      6947049.54
#Sta/Elev= 30
  4403.4 1891.79  4434.4 1889.38  4439.5 1889.83  4475.2 1887.96  4545.8 1888.01
  4582.1 1886.80  4616.5 1887.37  4636.7 1886.44  4653.4 1885.53  4667.0 1886.43
  4778.2 1884.32  4808.4 1884.34  4838.7 1881.47  4858.9 1881.33  4949.8 1876.71
  4995.1 1875.94  5030.2 1875.36  5048.4 1875.19  5048.6 1874.69  5052.4 1875.19
  5160.5 1875.90  5310.8 1875.66  5341.3 1876.51  5375.2 1876.33  5390.9 1877.27
  5431.0 1877.92  5531.2 1881.44  5546.3 1882.53  5621.3 1884.73  5777.6 1884.88
#Mann=8,-1,0
  4403.4   0.035       0  4636.7    0.07       0  4778.2   0.035       0
  4995.1    0.07       0  5030.2   0.035       0  5048.4    0.07       0
  5052.4   0.035       0  5341.3    0.07       0
Bank Sta=5048.4,5052.4
Exp/Cntr=0.3,0.1

Type RM Length L Ch R = 1,5486,273,273,273
BEGIN DESCRIPTION:
Clear Fork Trib11_2 12.0
END DESCRIPTION:
XS GIS Cut Line= 3
      1455005.03      6946988.04      1454755.00      6946688.00
      1454155.02      6946538.01
#Sta/Elev= 30
  4605.1 1887.90  4647.5 1885.67  4655.3 1886.05  4704.7 1885.00  4761.4 1881.36
  4768.5 1881.51  4789.3 1879.23  4814.3 1877.78  4853.1 1875.38  4931.2 1872.22
  5016.8 1871.44  5017.1 1870.94  5020.7 1870.94  5021.0 1871.44  5078.1 1872.99
  5142.5 1876.47  5183.8 1877.72  5212.1 1877.51  5253.4 1878.99  5325.5 1879.93
  5366.7 1878.44  5377.0 1880.22  5389.9 1880.87  5418.3 1880.11  5490.4 1883.21
  5549.7 1884.44  5554.9 1885.17  5583.2 1886.26  5590.9 1887.24  5614.1 1888.54
#Mann=4,-1,0
  4605.1    0.07       0  4814.3   0.035       0  5016.8   0.035       0
  5021.0   0.035       0
Bank Sta=5016.8,5021
Exp/Cntr=0.3,0.1

Type RM Length L Ch R = 1,5213,657,657,657
BEGIN DESCRIPTION:
Mapping XS d250e9f3
END DESCRIPTION:
XS GIS Cut Line= 3
      1455439.75      6946493.93      1454790.45      6946427.96
      1453964.08      6946226.57
#Sta/Elev= 30
  4362.0 1887.91  4371.5 1888.17  4386.9 1887.12  4421.9 1886.45  4577.9 1884.76
  4618.1 1886.74  4658.3 1887.14  4688.3 1885.49  4708.5 1883.77  4758.8 1881.41
  4788.9 1877.60  4849.2 1873.35  4899.5 1871.34  4964.8 1869.78  5124.2 1868.59
  5160.7 1869.15  5163.8 1868.57  5164.1 1868.07  5168.0 1868.57  5339.3 1870.68
  5369.3 1872.94  5416.1 1875.05  5457.8 1878.91  5499.5 1881.32  5582.9 1884.43
  5629.8 1884.88  5658.4 1885.93  5699.6 1885.80  5781.9 1888.86  5865.2 1887.99
#Mann=5,-1,0
  4362.0   0.035       0  4421.9    0.07       0  4688.3   0.035       0
  5163.8   0.035       0  5168.0   0.035       0
Bank Sta=5163.8,5168
Exp/Cntr=0.3,0.1

Type RM Length L Ch R = 1,4556,482,482,482
BEGIN DESCRIPTION:
Clear Fork Trib11_2 10.0
END DESCRIPTION:
XS GIS Cut Line= 3
      1455467.54      6945986.98      1454705.00      6945938.00
      1454319.07      6945931.44
#Sta/Elev= 30
  4231.4 1883.98  4296.3 1882.33  4344.2 1882.46  4449.5 1880.87  4454.5 1881.35
  4474.4 1880.67  4494.5 1880.93  4544.6 1878.23  4564.6 1877.60  4689.7 1875.87
  4745.0 1874.08  4775.1 1873.94  4815.1 1872.87  4895.3 1871.77  4918.9 1871.25
  4955.4 1869.53  5003.4 1868.91  5003.7 1868.41  5007.4 1868.41  5007.7 1868.91
  5055.5 1870.12  5105.5 1873.05  5127.2 1875.36  5135.5 1876.87  5152.2 1877.75
  5175.5 1880.04  5195.5 1880.67  5205.5 1881.55  5285.2 1882.89  5381.5 1885.42
#Mann=6,-1,0
  4231.4    0.07       0  4689.7   0.035       0  5003.4   0.035       0
  5007.7   0.035       0  5127.2    0.07       0  5152.2   0.035       0
Bank Sta=5003.4,5007.7
Exp/Cntr=0.3,0.1

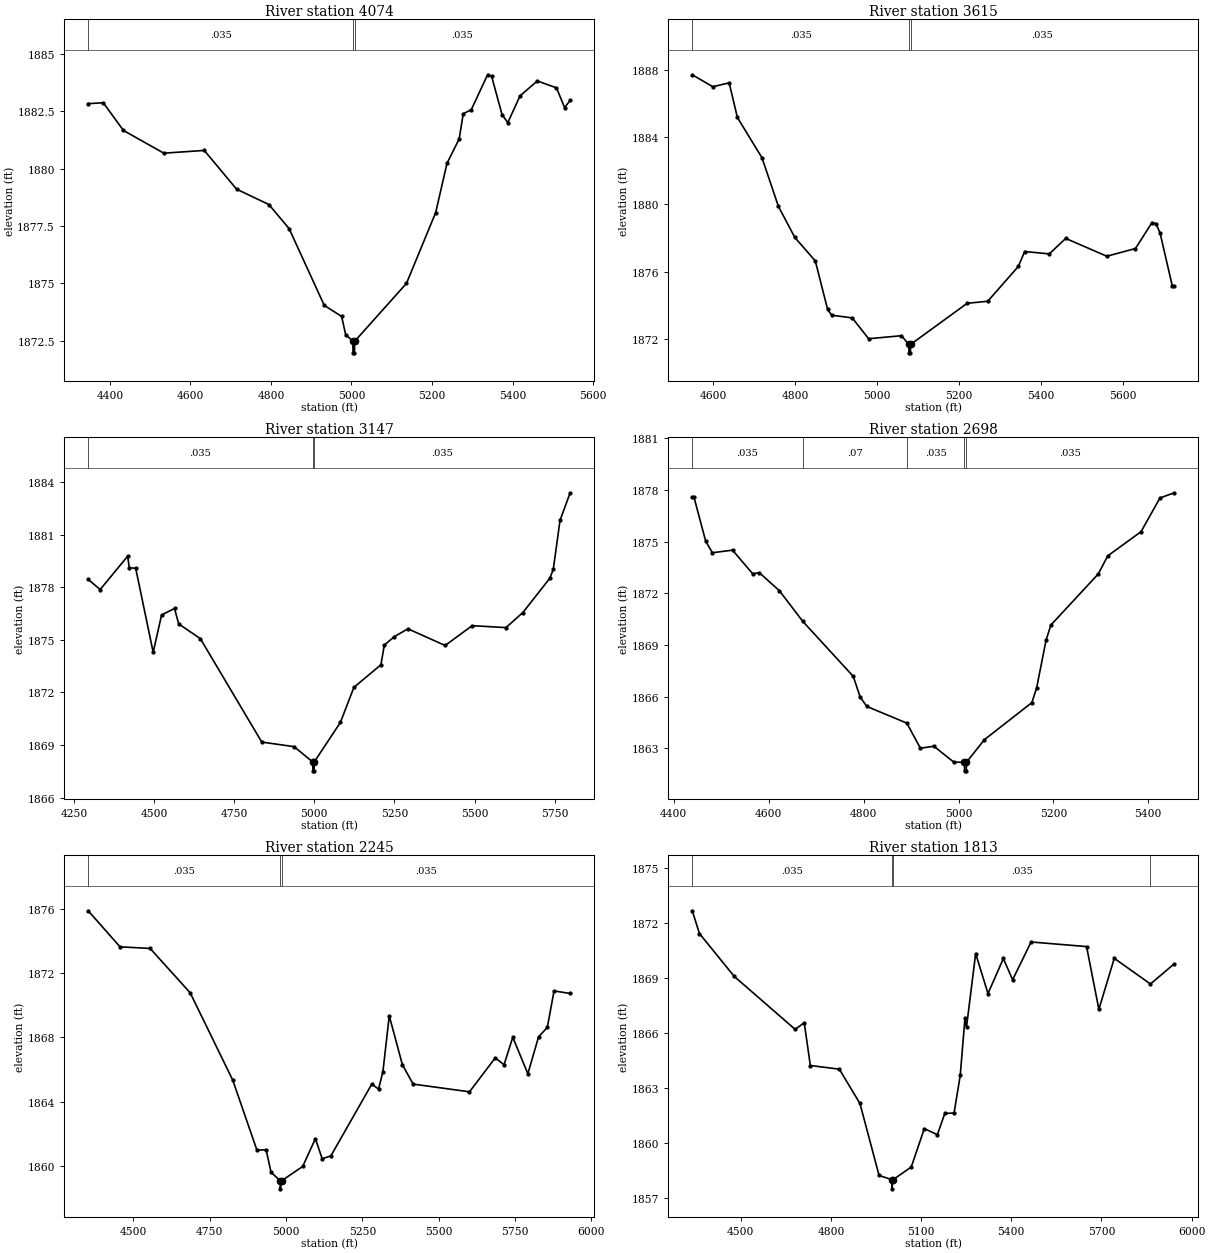
Type RM Length L Ch R = 1,4074,459,459,459
BEGIN DESCRIPTION:
Clear Fork Trib11_2 9.0
END DESCRIPTION:
XS GIS Cut Line= 3
      1455252.30      6945434.90      1454605.00      6945488.00
      1454061.24      6945552.96
#Sta/Elev= 30
  4346.1 1882.84  4383.5 1882.88  4433.7 1881.67  4534.0 1880.68  4634.4 1880.80
  4714.6 1879.11  4794.9 1878.44  4845.1 1877.39  4932.4 1874.04  4975.5 1873.56
  4985.5 1872.77  5003.5 1872.47  5003.8 1871.97  5007.5 1871.97  5007.8 1872.47
  5136.6 1875.00  5209.2 1878.09  5237.3 1880.24  5267.5 1881.30  5277.6 1882.40
  5297.7 1882.58  5338.0 1884.10  5348.1 1884.03  5374.1 1882.36  5388.3 1882.01
  5418.6 1883.18  5461.6 1883.83  5509.2 1883.53  5529.3 1882.67  5543.2 1882.98
#Mann=3,-1,0
  4346.1   0.035       0  5003.5   0.035       0  5007.8   0.035       0
Bank Sta=5003.5,5007.8
Exp/Cntr=0.3,0.1

Type RM Length L Ch R = 1,3615,468,468,468
BEGIN DESCRIPTION:
Clear Fork Trib11_2 8.0
END DESCRIPTION:
XS GIS Cut Line= 3
      1455055.05      6945088.00      1454605.00      6945088.00
      1453880.73      6945056.43
#Sta/Elev= 30
  4549.5 1887.72  4599.5 1887.01  4639.5 1887.24  4659.5 1885.18  4719.5 1882.78
  4759.5 1879.89  4799.5 1878.04  4849.5 1876.64  4879.5 1873.75  4889.5 1873.41
  4939.5 1873.25  4979.5 1872.01  5059.6 1872.19  5077.5 1871.67  5077.8 1871.17
  5081.5 1871.17  5081.8 1871.67  5219.8 1874.12  5269.8 1874.24  5344.4 1876.31
  5359.9 1877.20  5419.9 1877.06  5460.0 1877.98  5560.1 1876.92  5630.1 1877.38
  5670.2 1878.92  5680.2 1878.86  5690.2 1878.28  5719.9 1875.14  5724.5 1875.14
#Mann=3,-1,0
  4549.5   0.035       0  5077.5   0.035       0  5081.8   0.035       0
Bank Sta=5077.5,5081.8
Exp/Cntr=0.3,0.1

Type RM Length L Ch R = 1,3147,449,449,449
BEGIN DESCRIPTION:
Clear Fork Trib11_2 7.0
END DESCRIPTION:
XS GIS Cut Line= 3
      1455411.98      6944778.65      1454705.00      6944688.00
      1453955.03      6944937.99
#Sta/Elev= 30
  4294.8 1878.45  4332.1 1877.87  4417.8 1879.77  4422.9 1879.12  4443.0 1879.08
  4497.5 1874.29  4523.6 1876.42  4564.0 1876.79  4577.1 1875.91  4644.6 1875.07
  4836.2 1869.17  4937.0 1868.91  4995.3 1868.03  4995.6 1867.53  4999.4 1867.53
  4999.6 1868.03  5081.4 1870.29  5123.5 1872.29  5207.8 1873.58  5218.4 1874.70
  5250.0 1875.19  5292.2 1875.63  5408.1 1874.68  5492.4 1875.81  5597.9 1875.70
  5650.6 1876.56  5734.9 1878.52  5745.4 1879.02  5766.5 1881.82  5798.1 1883.39
#Mann=3,-1,0
  4294.8   0.035       0  4995.3   0.035       0  4999.6   0.035       0
Bank Sta=4995.3,4999.6
Exp/Cntr=0.3,0.1

Type RM Length L Ch R = 1,2698,453,453,453
BEGIN DESCRIPTION:
Clear Fork Trib11_2 6.0
END DESCRIPTION:
XS GIS Cut Line= 3
      1455255.00      6944688.00      1454855.00      6944288.00
      1454404.99      6944288.00
#Sta/Elev= 30
  4438.9 1877.59  4442.4 1877.59  4467.2 1875.02  4481.3 1874.35  4523.8 1874.50
  4566.2 1873.13  4580.3 1873.19  4622.7 1872.14  4671.7 1870.37  4778.3 1867.17
  4792.5 1865.99  4806.6 1865.43  4891.1 1864.46  4919.7 1863.00  4948.0 1863.12
  4990.4 1862.19  5012.4 1862.19  5012.7 1861.69  5016.5 1861.69  5016.8 1862.19
  5054.6 1863.50  5154.6 1865.65  5164.6 1866.50  5184.6 1869.28  5194.6 1870.15
  5294.6 1873.12  5314.6 1874.17  5384.6 1875.57  5424.6 1877.53  5454.6 1877.83
#Mann=5,-1,0
  4438.9   0.035       0  4671.7    0.07       0  4891.1   0.035       0
  5012.4   0.035       0  5016.8   0.035       0
Bank Sta=5012.4,5016.8
Exp/Cntr=0.3,0.1

Type RM Length L Ch R = 1,2245,432,432,432
BEGIN DESCRIPTION:
Clear Fork Trib11_2 5.0
END DESCRIPTION:
XS GIS Cut Line= 3
      1455488.38      6944747.42      1455255.00      6944138.00
      1454659.23      6943428.81
#Sta/Elev= 30
  4352.0 1875.86  4456.2 1873.62  4554.8 1873.52  4685.8 1870.77  4825.4 1865.34
  4904.8 1860.98  4934.8 1861.01  4951.0 1859.61  4981.0 1859.08  4981.3 1858.58
  4985.4 1859.08  5054.6 1859.97  5096.3 1861.70  5118.4 1860.45  5147.0 1860.63
  5281.0 1865.09  5303.1 1864.78  5317.4 1865.86  5338.2 1869.33  5381.1 1866.30
  5416.3 1865.09  5601.0 1864.61  5685.5 1866.72  5714.2 1866.29  5742.8 1868.00
  5792.2 1865.73  5827.4 1868.03  5855.9 1868.61  5878.0 1870.88  5930.8 1870.72
#Mann=3,-1,0
  4352.0   0.035       0  4981.0   0.035       0  4985.4   0.035       0
Bank Sta=4981,4985.4
Exp/Cntr=0.3,0.1

Type RM Length L Ch R = 1,1813,460,460,460
BEGIN DESCRIPTION:
Clear Fork Trib11_2 4.0
END DESCRIPTION:
XS GIS Cut Line= 3
      1455703.65      6944636.28      1455605.00      6943988.00
      1455398.10      6943063.41
#Sta/Elev= 30
  4338.8 1872.66  4362.7 1871.42  4478.7 1869.08  4681.0 1866.20  4711.3 1866.56
  4731.6 1864.23  4828.0 1864.03  4896.6 1862.16  4960.2 1858.24  5002.6 1858.01
  5002.9 1857.51  5007.0 1858.01  5067.3 1858.70  5110.7 1860.79  5154.1 1860.46
  5179.0 1861.62  5209.7 1861.64  5230.2 1863.69  5246.0 1866.82  5251.1 1866.33
  5281.5 1870.33  5322.5 1868.15  5373.7 1870.06  5404.4 1868.90  5465.9 1870.96
  5650.4 1870.71  5691.4 1867.29  5742.6 1870.07  5863.0 1868.67  5942.0 1869.77
#Mann=4,-1,0
  4338.8   0.035       0  5002.6   0.035       0  5007.0   0.035       0
  5863.0    0.07       0
Bank Sta=5002.6,5007
Exp/Cntr=0.3,0.1

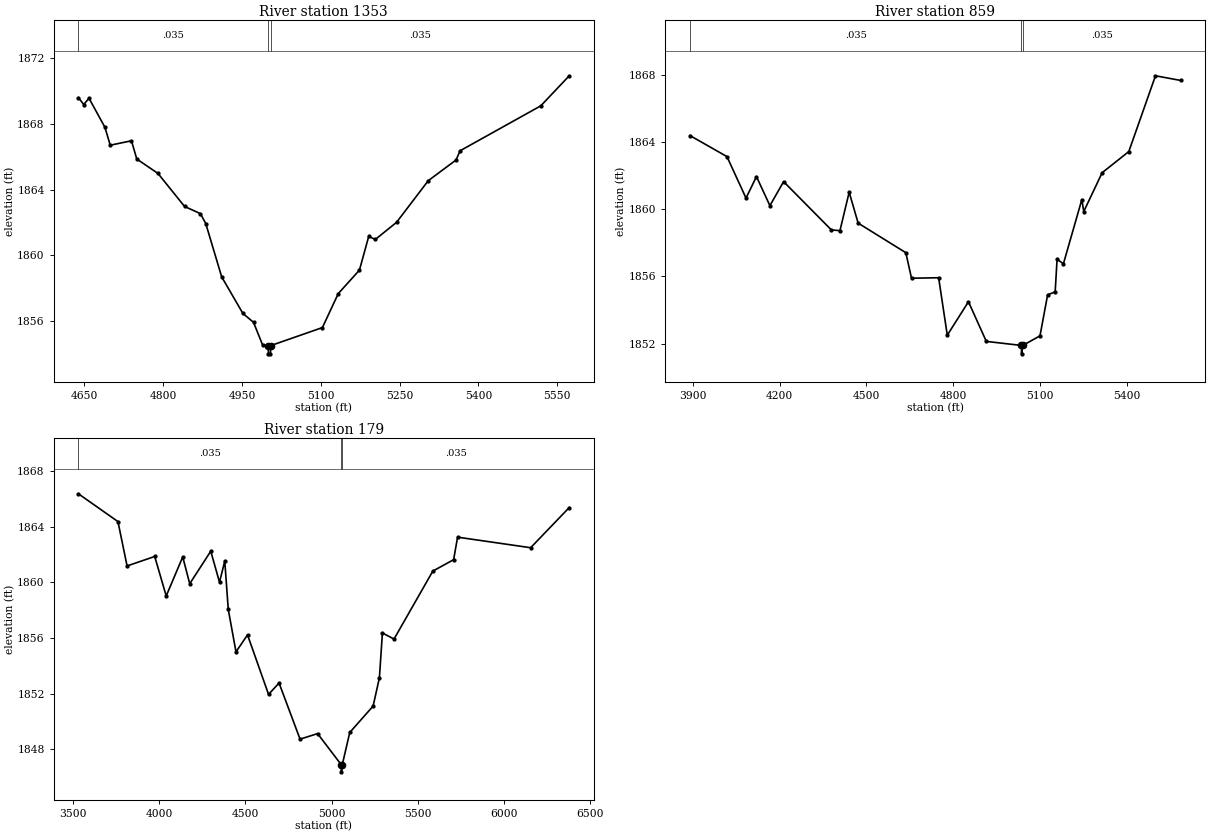
Type RM Length L Ch R = 1,1353,494,494,494
BEGIN DESCRIPTION:
Clear Fork Trib11_2 3.0
END DESCRIPTION:
XS GIS Cut Line= 3
      1456055.00      6944337.97      1456005.00      6943988.00
      1455932.97      6943411.81
#Sta/Elev= 30
  4638.7 1869.61  4648.8 1869.19  4658.9 1869.57  4689.2 1867.80  4699.3 1866.71
  4739.7 1866.98  4749.8 1865.87  4790.2 1864.99  4840.7 1862.98  4871.0 1862.54
  4881.1 1861.94  4911.4 1858.69  4951.8 1856.46  4972.0 1855.92  4989.7 1854.51
  5000.1 1854.50  5000.4 1854.00  5004.3 1854.00  5004.6 1854.50  5103.1 1855.60
  5133.3 1857.67  5173.6 1859.10  5191.2 1861.15  5203.9 1860.97  5244.2 1862.01
  5304.6 1864.55  5357.5 1865.81  5365.1 1866.37  5518.8 1869.11  5572.9 1870.94
#Mann=3,-1,0
  4638.7   0.035       0  5000.1   0.035       0  5004.6   0.035       0
Bank Sta=5000.1,5004.6
Exp/Cntr=0.3,0.1

Type RM Length L Ch R = 1,859,680,680,680
BEGIN DESCRIPTION:
Clear Fork Trib11_2 2.0
END DESCRIPTION:
XS GIS Cut Line= 3
      1456676.71      6944861.81      1456376.72      6943661.85
      1456027.38      6943362.42
#Sta/Elev= 30
  3890.0 1864.38  4017.6 1863.13  4083.6 1860.66  4119.7 1861.94  4166.1 1860.21
  4213.5 1861.64  4378.4 1858.77  4408.3 1858.72  4440.2 1861.01  4471.2 1859.17
  4636.1 1857.41  4655.7 1855.89  4749.5 1855.92  4779.4 1852.50  4852.6 1854.49
  4914.4 1852.13  5035.8 1851.89  5036.1 1851.39  5040.3 1851.89  5099.9 1852.46
  5126.3 1854.90  5152.4 1855.08  5159.0 1857.02  5180.9 1856.75  5244.6 1860.57
  5251.2 1859.86  5314.8 1862.17  5407.0 1863.43  5499.2 1867.94  5587.0 1867.66
#Mann=3,-1,0
  3890.0   0.035       0  5035.8   0.035       0  5040.3   0.035       0
Bank Sta=5035.8,5040.3
Exp/Cntr=0.3,0.1

Type RM Length L Ch R = 1,179,0,0,0
BEGIN DESCRIPTION:
Clear Fork Trib11_2 1.0
END DESCRIPTION:
XS GIS Cut Line= 3
      1457158.51      6944823.81      1456903.53      6943377.52
      1455651.58      6942802.96
#Sta/Elev= 30
  3531.4 1866.38  3760.7 1864.38  3813.7 1861.19  3973.9 1861.87  4040.6 1859.03
  4136.4 1861.84  4177.0 1859.91  4298.9 1862.25  4349.6 1860.02  4380.1 1861.54
  4400.4 1858.06  4445.2 1855.01  4512.1 1856.23  4634.0 1851.95  4694.9 1852.77
  4816.7 1848.73  4918.3 1849.13  5056.3 1846.88  5056.7 1846.38  5061.3 1846.88
  5104.8 1849.21  5240.4 1851.11  5276.8 1853.15  5294.2 1856.37  5361.5 1855.93
  5586.6 1860.82  5707.1 1861.64  5730.1 1863.26  6153.7 1862.50  6377.5 1865.39
#Mann=3,-1,0
  3531.4   0.035       0  5056.3   0.035       0  5061.3   0.035       0
Bank Sta=5056.3,5061.3
Exp/Cntr=0.3,0.1

Chan Stop Cuts=-1