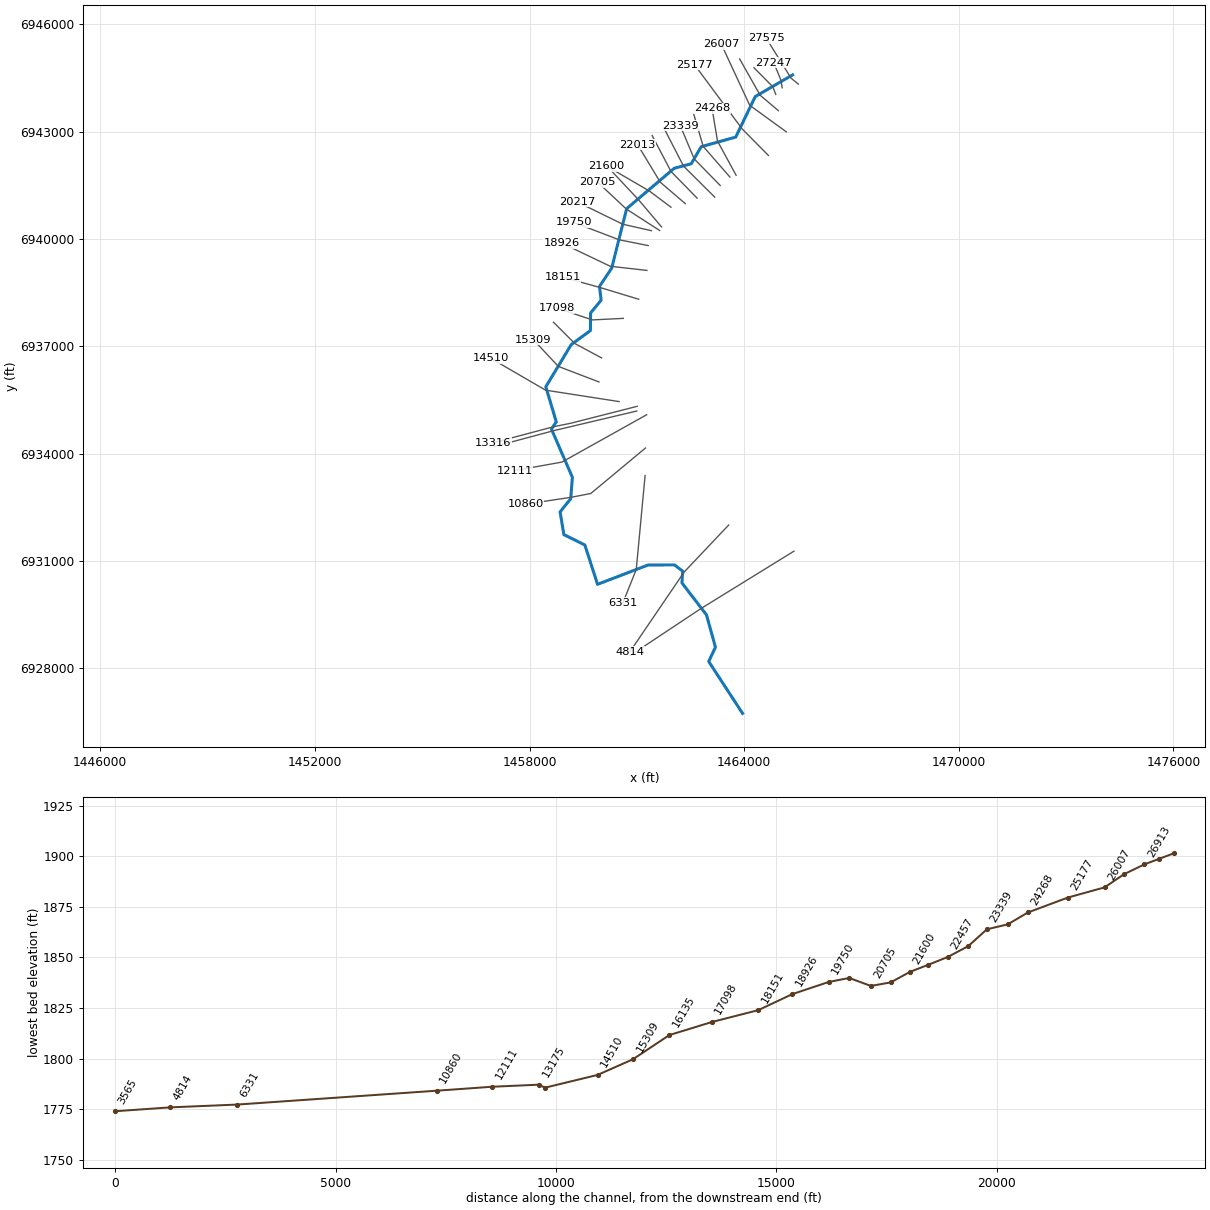
--- Clear Fork Trib12.prj (project) ---

Proj Title=Clear Fork Trib12 Base Level Engineering
Current Plan=p01
Default Exp/Contr=0.3,0.1
English Units
Geom File=g01
Flow File=f01
Plan File=p01
BEGIN DESCRIPTION:
Clear Fork Trib12
END DESCRIPTION:

--- Clear Fork Trib12.p01 (plan) ---

Plan Title=Multiple Run
Short Identifier=Multiple
Geom File=g01
Flow File=f01
Subcritical Flow
K Sum by GR= 0
Std Step Tol= 0.01
Critical Tol= 0.01
Num of Std Step Trials= 20
Max Error Tol= 0.3
Flow Tol Ratio= 0.001
Split Flow NTrial= 30
Split Flow Tol= 0.02
Split Flow Ratio= 0.02
Log Output Level= 0
Friction Slope Method= 1
Unsteady Friction Slope Method= 2
Unsteady Bridges Friction Slope Method= 1
Parabolic Critical Depth
Global Vel Dist=  1 , 1 , 1
Global Log Level= 0
CheckData=True
Encroach Param= -1, 0, 0, 0
BEGIN DESCRIPTION:
Multiple Run
END DESCRIPTION:

--- Clear Fork Trib12.f01 (steady flow) ---

Flow Title=Multiple
Number of Profiles=7
Profile Names=10-year,25-year,50-year,1pct_min,100-year,1pct_plu,500-year
River Rch & RM= Clear Fork Trib1,Reach-1,27575
     178     239     287     171     341     681     490
River Rch & RM= Clear Fork Trib1,Reach-1,25177
     325     453     560     343     685    1367    1038
River Rch & RM= Clear Fork Trib1,Reach-1,20705
     470     670     839     521    1040    2076    1620
River Rch & RM= Clear Fork Trib1,Reach-1,13175
     527     754     945     588    1173    2340    1828
River Rch & RM= Clear Fork Trib1,Reach-1,4814
     531     759     951     591    1179    2352    1835
River Rch & RM= Clear Fork Trib1,Reach-1,2760
     667     963    1214     759    1514    3022    2385
Boundary for River Rch & Prof#=Clear Fork Trib1,Reach-1,1
Up Type=0
Dn Type=3
Dn Slope=0.005
Boundary for River Rch & Prof#=Clear Fork Trib1,Reach-1,2
Up Type=0
Dn Type=3
Dn Slope=0.005
Boundary for River Rch & Prof#=Clear Fork Trib1,Reach-1,3
Up Type=0
Dn Type=3
Dn Slope=0.005
Boundary for River Rch & Prof#=Clear Fork Trib1,Reach-1,4
Up Type=0
Dn Type=3
Dn Slope=0.005
Boundary for River Rch & Prof#=Clear Fork Trib1,Reach-1,5
Up Type=0
Dn Type=3
Dn Slope=0.005
Boundary for River Rch & Prof#=Clear Fork Trib1,Reach-1,6
Up Type=0
Dn Type=3
Dn Slope=0.005
Boundary for River Rch & Prof#=Clear Fork Trib1,Reach-1,7
Up Type=0
Dn Type=3
Dn Slope=0.005

--- Clear Fork Trib12.g01 (geometry) ---

Geom Title=Existing Conditions

River Reach=Clear Fork Trib1,Reach-1
Reach XY= 30
      1465355.00      6944588.00      1464310.58      6943982.42
      1463764.68      6942848.78      1462798.81      6942580.14
      1462522.04      6942104.23      1462044.94      6941976.90
      1460715.52      6940847.79      1460296.76      6939184.77
      1459956.49      6938676.46      1460001.47      6938289.46
      1459707.23      6937932.07      1459701.18      6937439.58
      1459165.76      6937047.70      1458454.96      6935868.02
      1458747.68      6934887.90      1458612.77      6934684.59
      1459197.55      6933338.21      1459151.53      6932739.27
      1458855.20      6932371.96      1458960.40      6931735.29
      1459547.18      6931444.19      1459901.65      6930346.03
      1461315.44      6930886.94      1462055.00      6930888.00
      1462282.29      6930711.47      1462260.11      6930385.71
      1462947.01      6929491.34      1463197.69      6928587.90
      1463008.67      6928189.58      1463955.00      6926738.00

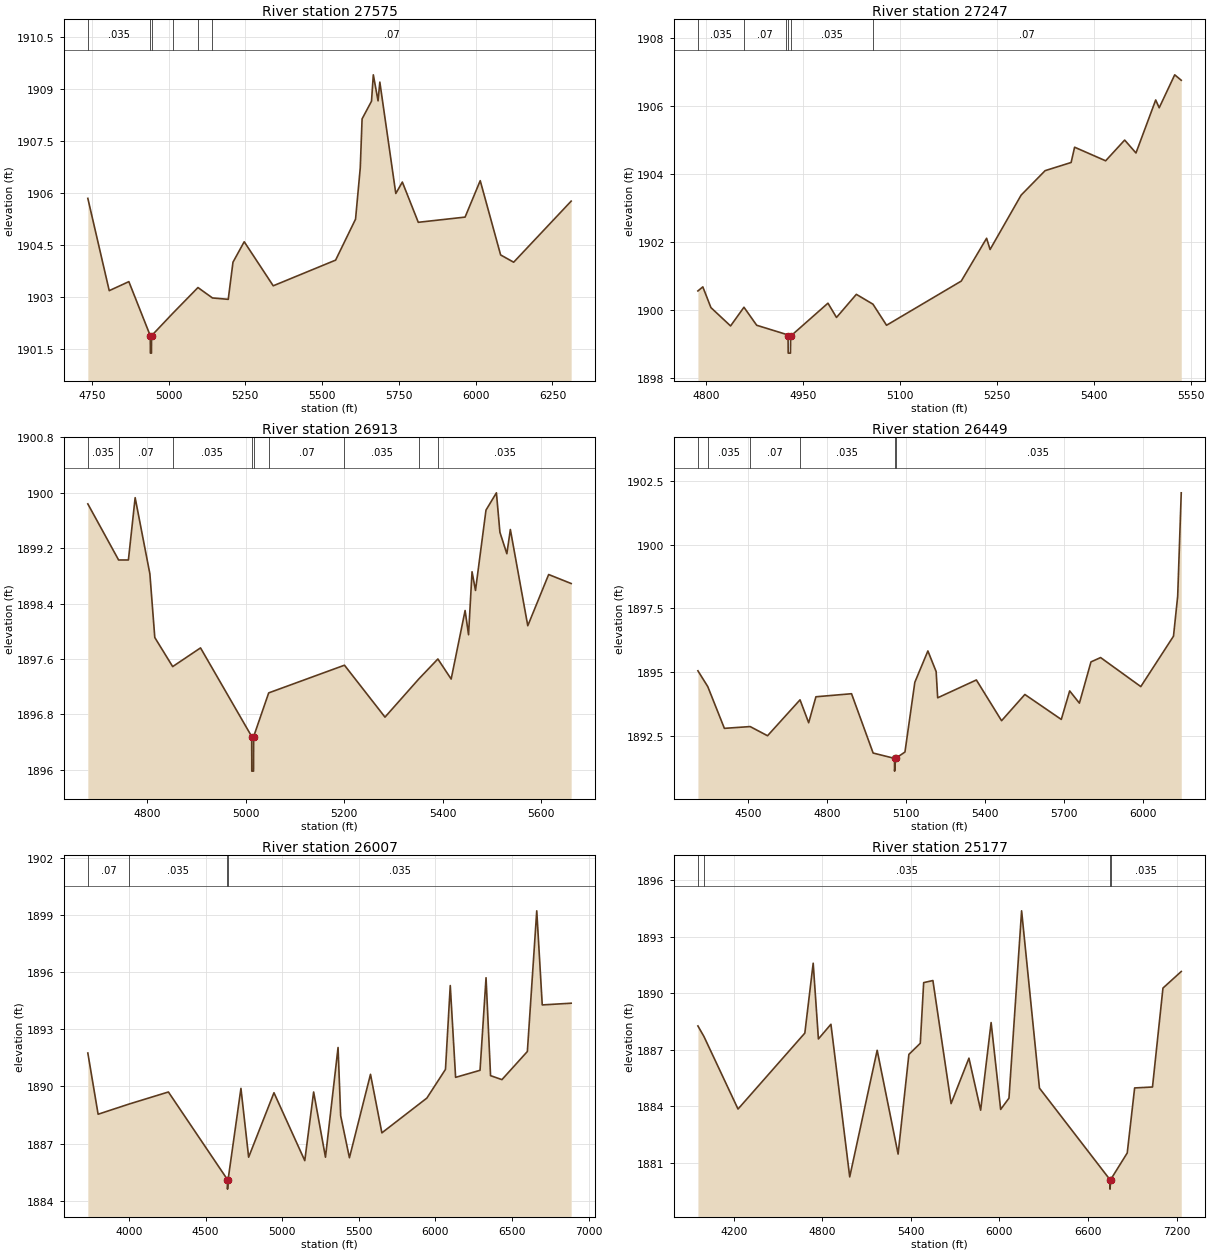
Type RM Length L Ch R = 1,27575,328,328,328
BEGIN DESCRIPTION:
Clear Fork Trib12 34.0
END DESCRIPTION:
XS GIS Cut Line= 3
      1465514.95      6944329.67      1465311.31      6944495.93
      1464619.68      6945609.54
#Sta/Elev= 30
  4737.1 1905.84  4806.8 1903.18  4870.7 1903.44  4940.5 1901.88  4940.8 1901.38
  4944.3 1901.38  4944.5 1901.88  5012.9 1902.52  5095.7 1903.27  5142.9 1902.97
  5194.3 1902.93  5209.7 1904.00  5246.3 1904.59  5340.8 1903.32  5543.9 1904.06
  5608.8 1905.24  5624.2 1906.72  5630.1 1908.13  5660.8 1908.64  5666.7 1909.40
  5682.1 1908.65  5687.9 1909.19  5739.9 1905.98  5761.2 1906.31  5813.1 1905.15
  5965.5 1905.30  6014.8 1906.35  6081.2 1904.21  6123.7 1904.00  6310.9 1905.76
#Mann=6,-1,0
  4737.1   0.035       0  4940.5   0.035       0  4944.5   0.035       0
  5012.9    0.07       0  5095.7   0.035       0  5142.9    0.07       0
Bank Sta=4940.5,4944.5
Exp/Cntr=0.3,0.1

Type RM Length L Ch R = 1,27247,334,334,334
BEGIN DESCRIPTION:
Mapping XS fe80b265
END DESCRIPTION:
XS GIS Cut Line= 3
      1465061.47      6944228.07      1465032.05      6944431.21
      1464826.33      6944932.80
#Sta/Elev= 30
  4787.4 1900.55  4795.0 1900.67  4807.5 1900.06  4837.9 1899.52  4858.6 1900.07
  4878.3 1899.54  4924.3 1899.27  4926.8 1899.22  4927.0 1898.72  4930.5 1898.72
  4930.8 1899.22  4988.5 1900.19  5001.7 1899.77  5032.4 1900.45  5058.1 1900.16
  5079.1 1899.54  5194.6 1900.84  5233.8 1902.10  5239.2 1901.77  5287.2 1903.37
  5324.3 1904.09  5364.5 1904.33  5369.9 1904.78  5417.9 1904.38  5447.3 1904.99
  5464.8 1904.61  5495.3 1906.17  5500.7 1905.94  5524.7 1906.91  5534.8 1906.75
#Mann=6,-1,0
  4787.4   0.035       0  4858.6    0.07       0  4924.3   0.035       0
  4926.8   0.035       0  4930.8   0.035       0  5058.1    0.07       0
Bank Sta=4926.8,4930.8
Exp/Cntr=0.3,0.1

Type RM Length L Ch R = 1,26913,464,464,464
BEGIN DESCRIPTION:
Mapping XS daf7bc7f
END DESCRIPTION:
XS GIS Cut Line= 3
      1464883.88      6944041.19      1464800.55      6944256.22
      1464272.59      6944790.29
#Sta/Elev= 30
  4679.2 1899.84  4741.7 1899.03  4761.6 1899.03  4775.3 1899.93  4805.2 1898.83
  4815.2 1897.91  4851.5 1897.49  4908.1 1897.76  5012.0 1896.48  5012.2 1895.98
  5015.7 1895.98  5016.0 1896.48  5046.5 1897.11  5200.4 1897.51  5282.7 1896.76
  5351.2 1897.31  5390.1 1897.60  5417.1 1897.31  5445.4 1898.30  5452.4 1897.95
  5459.5 1898.86  5466.5 1898.59  5487.8 1899.75  5509.0 1900.00  5516.1 1899.43
  5530.2 1899.12  5537.3 1899.47  5572.7 1898.08  5615.1 1898.82  5660.8 1898.69
#Mann=9,-1,0
  4679.2   0.035       0  4741.7    0.07       0  4851.5   0.035       0
  5012.0   0.035       0  5016.0   0.035       0  5046.5    0.07       0
  5200.4   0.035       0  5351.2    0.07       0  5390.1   0.035       0
Bank Sta=5012,5016
Exp/Cntr=0.3,0.1

Type RM Length L Ch R = 1,26449,442,442,442
BEGIN DESCRIPTION:
Mapping XS 77872c78
END DESCRIPTION:
XS GIS Cut Line= 3
      1464956.77      6943588.29      1464448.71      6944018.01
      1463873.02      6945034.14
#Sta/Elev= 30
  4310.8 1895.05  4348.2 1894.43  4411.2 1892.79  4508.9 1892.86  4574.9 1892.50
  4698.1 1893.91  4730.9 1893.01  4758.4 1894.03  4893.5 1894.15  4975.4 1891.82
  5056.6 1891.61  5056.8 1891.11  5060.6 1891.61  5096.1 1891.86  5133.6 1894.60
  5183.1 1895.83  5214.4 1895.02  5220.2 1893.99  5367.0 1894.69  5462.6 1893.09
  5550.9 1894.12  5689.1 1893.14  5720.9 1894.26  5757.8 1893.78  5801.7 1895.40
  5838.2 1895.57  5990.7 1894.43  6114.7 1896.41  6130.6 1897.98  6144.1 1902.04
#Mann=6,-1,0
  4310.8    0.07       0  4348.2   0.035       0  4508.9    0.07       0
  4698.1   0.035       0  5056.6   0.035       0  5060.6   0.035       0
Bank Sta=5056.6,5060.6
Exp/Cntr=0.3,0.1

Type RM Length L Ch R = 1,26007,830,830,830
BEGIN DESCRIPTION:
Clear Fork Trib12 33.0
END DESCRIPTION:
XS GIS Cut Line= 3
      1465177.86      6942996.13      1464155.00      6943738.00
      1463359.44      6945451.67
#Sta/Elev= 30
  3732.1 1891.76  3799.2 1888.54  4002.9 1889.08  4257.7 1889.71  4643.1 1885.10
  4643.3 1884.60  4647.1 1885.10  4730.9 1889.90  4781.1 1886.28  4946.3 1889.67
  5147.3 1886.10  5205.1 1889.71  5282.3 1886.28  5364.4 1892.05  5381.5 1888.46
  5438.6 1886.25  5576.0 1890.64  5650.2 1887.56  5943.8 1889.39  6065.1 1890.90
  6096.3 1895.31  6131.2 1890.48  6290.5 1890.85  6329.7 1895.72  6359.2 1890.57
  6433.4 1890.36  6599.3 1891.84  6660.5 1899.24  6696.4 1894.29  6885.0 1894.38
#Mann=4,-1,0
  3732.1    0.07       0  4002.9   0.035       0  4643.1   0.035       0
  4647.1   0.035       0
Bank Sta=4643.1,4647.1
Exp/Cntr=0.3,0.1

Type RM Length L Ch R = 1,25177,909,909,909
BEGIN DESCRIPTION:
Mapping XS 979faa0f
END DESCRIPTION:
XS GIS Cut Line= 3
      1464677.86      6942336.40      1463941.73      6943079.47
      1462614.06      6944869.60
#Sta/Elev= 30
  3957.2 1888.27  3998.1 1887.71  4229.0 1883.86  4681.6 1887.89  4738.2 1891.60
  4773.6 1887.58  4858.4 1888.36  4985.7 1880.26  5171.7 1886.98  5313.5 1881.47
  5386.6 1886.76  5463.8 1887.35  5486.8 1890.57  5549.3 1890.68  5672.5 1884.15
  5793.5 1886.56  5872.8 1883.80  5943.7 1888.45  6008.4 1883.84  6064.7 1884.44
  6150.3 1894.38  6271.3 1884.97  6749.2 1880.11  6749.5 1879.61  6753.2 1880.11
  6866.0 1881.53  6916.1 1884.98  7037.1 1885.03  7108.0 1890.28  7231.9 1891.16
#Mann=4,-1,0
  3957.2    0.07       0  3998.1   0.035       0  6749.2   0.035       0
  6753.2   0.035       0
Bank Sta=6749.2,6753.2
Exp/Cntr=0.3,0.1

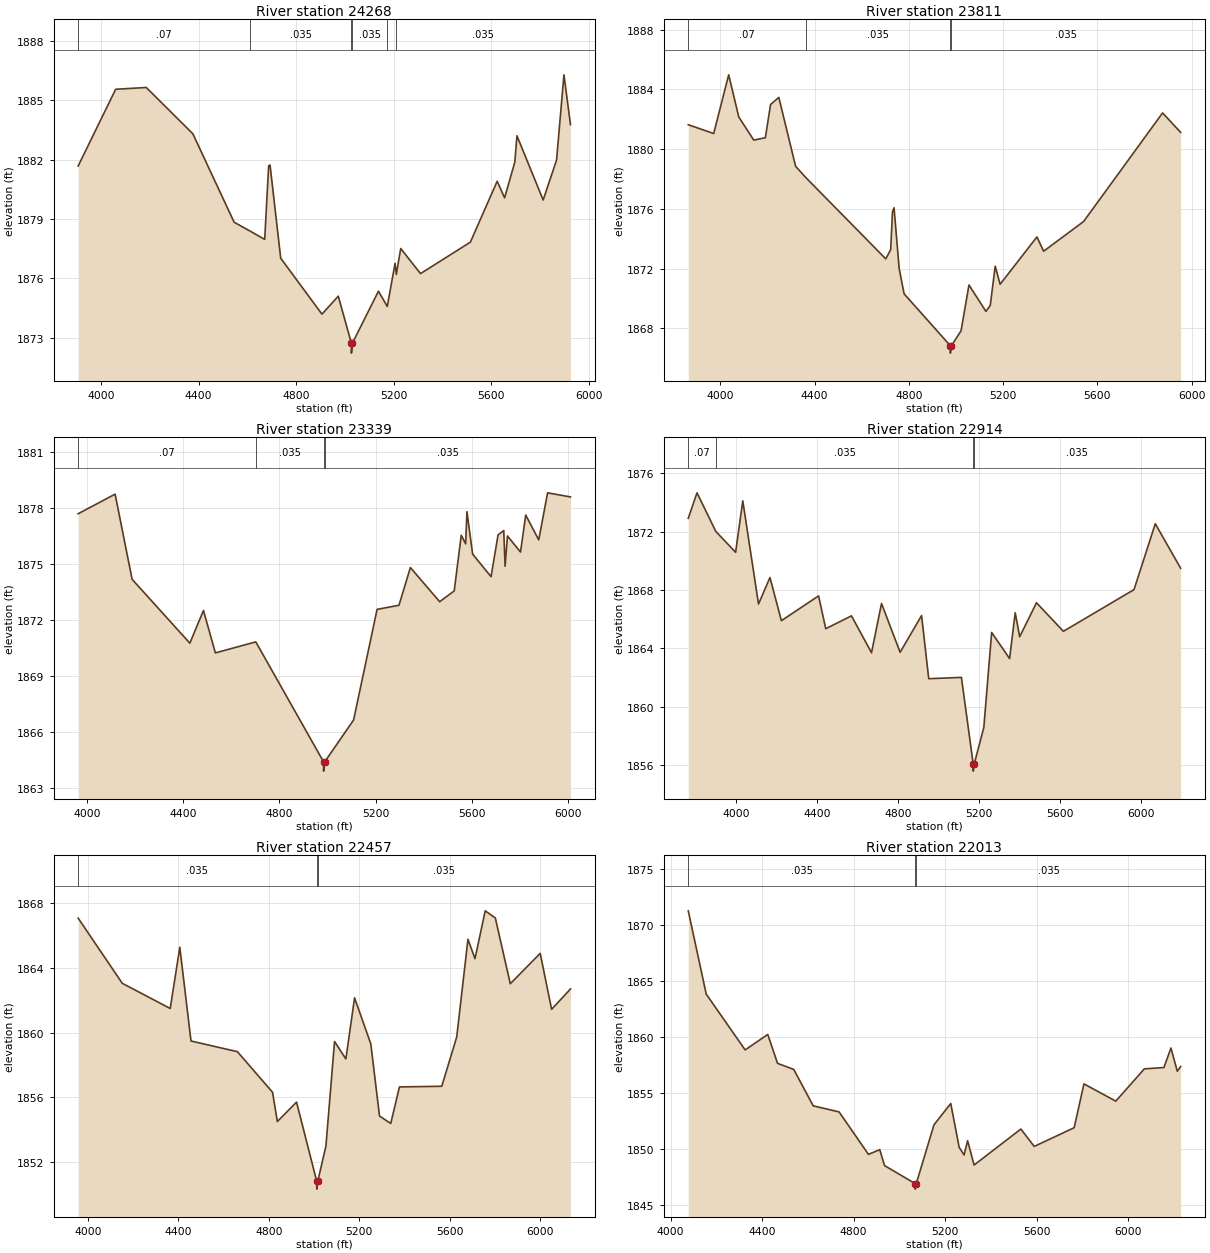
Type RM Length L Ch R = 1,24268,457,457,457
BEGIN DESCRIPTION:
Clear Fork Trib12 31.0
END DESCRIPTION:
XS GIS Cut Line= 3
      1463775.07      6941780.86      1463255.00      6942738.00
      1463101.69      6943654.46
#Sta/Elev= 30
  3906.4 1881.68  4060.2 1885.56  4185.6 1885.65  4376.6 1883.31  4545.8 1878.84
  4611.3 1878.39  4671.2 1877.97  4687.4 1881.69  4693.1 1881.73  4736.8 1877.02
  4905.9 1874.19  4972.9 1875.10  5026.6 1872.72  5026.8 1872.22  5030.6 1872.72
  5137.6 1875.35  5173.7 1874.58  5205.7 1876.76  5210.8 1876.20  5228.9 1877.51
  5310.0 1876.24  5514.4 1877.83  5624.3 1880.91  5654.7 1880.07  5696.5 1881.87
  5705.4 1883.21  5812.9 1879.96  5867.7 1881.98  5898.1 1886.29  5924.9 1883.77
#Mann=6,-1,0
  3906.4    0.07       0  4611.3   0.035       0  5026.6   0.035       0
  5030.6   0.035       0  5173.7    0.07       0  5210.8   0.035       0
Bank Sta=5026.6,5030.6
Exp/Cntr=0.3,0.1

Type RM Length L Ch R = 1,23811,472,472,472
BEGIN DESCRIPTION:
Clear Fork Trib12 30.0
END DESCRIPTION:
XS GIS Cut Line= 3
      1463601.47      6941732.24      1462855.00      6942588.00
      1462587.58      6943503.04
#Sta/Elev= 30
  3864.4 1881.64  3972.3 1881.05  4035.9 1884.98  4078.7 1882.16  4142.3 1880.61
  4191.6 1880.77  4213.5 1882.99  4248.6 1883.47  4319.8 1878.86  4362.0 1878.12
  4702.4 1872.66  4723.2 1873.28  4730.9 1875.81  4737.5 1876.08  4759.3 1872.00
  4780.2 1870.32  4976.1 1866.85  4976.5 1866.35  4981.2 1866.85  5021.9 1867.85
  5055.4 1870.91  5127.5 1869.14  5145.8 1869.55  5166.7 1872.17  5187.5 1870.96
  5343.8 1874.13  5372.1 1873.17  5541.7 1875.16  5876.9 1882.43  5953.3 1881.13
#Mann=4,-1,0
  3864.4    0.07       0  4362.0   0.035       0  4976.1   0.035       0
  4981.2   0.035       0
Bank Sta=4976.1,4981.2
Exp/Cntr=0.3,0.1

Type RM Length L Ch R = 1,23339,425,425,425
BEGIN DESCRIPTION:
Clear Fork Trib12 29.0
END DESCRIPTION:
XS GIS Cut Line= 3
      1463330.61      6941496.16      1462605.00      6942238.00
      1462212.58      6943169.73
#Sta/Elev= 30
  3962.3 1877.71  4116.1 1878.76  4186.8 1874.20  4427.1 1870.78  4483.7 1872.53
  4533.3 1870.26  4701.5 1870.85  4983.4 1864.43  4983.7 1863.93  4988.5 1864.43
  5108.5 1866.67  5206.2 1872.59  5297.3 1872.81  5344.8 1874.83  5466.6 1873.00
  5527.2 1873.58  5556.4 1876.56  5574.7 1876.10  5580.1 1877.82  5603.8 1875.55
  5680.4 1874.34  5709.6 1876.58  5733.3 1876.81  5738.8 1874.90  5748.7 1876.52
  5803.0 1875.66  5824.7 1877.64  5878.9 1876.31  5915.7 1878.83  6011.0 1878.61
#Mann=4,-1,0
  3962.3    0.07       0  4701.5   0.035       0  4983.4   0.035       0
  4988.5   0.035       0
Bank Sta=4983.4,4988.5
Exp/Cntr=0.3,0.1

Type RM Length L Ch R = 1,22914,457,457,457
BEGIN DESCRIPTION:
Clear Fork Trib12 28.0
END DESCRIPTION:
XS GIS Cut Line= 3
      1463177.86      6941169.74      1462305.00      6942038.00
      1461754.25      6943107.23
#Sta/Elev= 30
  3764.0 1872.92  3807.2 1874.67  3900.3 1872.02  3998.1 1870.59  4033.5 1874.12
  4111.3 1867.04  4167.8 1868.86  4224.4 1865.90  4408.3 1867.60  4443.6 1865.35
  4570.9 1866.23  4669.9 1863.70  4719.4 1867.08  4811.3 1863.73  4917.4 1866.25
  4952.8 1861.92  5114.3 1862.01  5172.5 1856.08  5172.9 1855.58  5177.7 1856.08
  5225.1 1858.57  5263.8 1865.09  5352.5 1863.30  5380.3 1866.44  5402.5 1864.80
  5485.5 1867.13  5618.5 1865.17  5967.6 1868.03  6072.8 1872.55  6197.9 1869.50
#Mann=4,-1,0
  3764.0    0.07       0  3900.3   0.035       0  5172.5   0.035       0
  5177.7   0.035       0
Bank Sta=5172.5,5177.7
Exp/Cntr=0.3,0.1

Type RM Length L Ch R = 1,22457,444,444,444
BEGIN DESCRIPTION:
Clear Fork Trib12 27.0
END DESCRIPTION:
XS GIS Cut Line= 3
      1462684.81      6941141.96      1461955.00      6941888.00
      1461427.85      6942891.97
#Sta/Elev= 30
  3956.3 1867.08  4151.3 1863.05  4363.5 1861.49  4405.9 1865.28  4455.4 1859.48
  4660.6 1858.82  4816.1 1856.31  4837.3 1854.50  4922.2 1855.70  5011.2 1850.82
  5011.6 1850.32  5016.4 1850.82  5052.2 1852.99  5090.3 1859.45  5140.4 1858.37
  5178.9 1862.15  5250.7 1859.30  5289.2 1854.84  5338.9 1854.38  5377.4 1856.64
  5564.5 1856.68  5630.7 1859.73  5680.4 1865.77  5711.5 1864.57  5756.7 1867.53
  5801.4 1867.09  5867.6 1863.02  5999.9 1864.90  6050.4 1861.44  6133.9 1862.70
#Mann=3,-1,0
  3956.3   0.035       0  5011.2   0.035       0  5016.4   0.035       0
Bank Sta=5011.2,5016.4
Exp/Cntr=0.3,0.1

Type RM Length L Ch R = 1,22013,413,413,413
BEGIN DESCRIPTION:
Clear Fork Trib12 26.0
END DESCRIPTION:
XS GIS Cut Line= 3
      1462355.01      6940987.99      1461655.00      6941588.00
      1461019.06      6942640.42
#Sta/Elev= 30
  4077.6 1871.27  4156.1 1863.84  4326.2 1858.86  4425.0 1860.24  4467.8 1857.66
  4538.6 1857.12  4623.7 1853.87  4736.7 1853.33  4865.1 1849.54  4914.5 1849.96
  4935.4 1848.54  5068.7 1846.94  5069.1 1846.44  5074.1 1846.94  5151.5 1852.18
  5224.7 1854.08  5261.5 1850.17  5282.9 1849.49  5298.4 1850.76  5326.7 1848.59
  5531.2 1851.80  5589.5 1850.25  5764.1 1851.92  5806.8 1855.83  5946.0 1854.29
  6070.7 1857.17  6156.3 1857.29  6187.1 1859.03  6214.7 1856.96  6229.2 1857.37
#Mann=3,-1,0
  4077.6   0.035       0  5068.7   0.035       0  5074.1   0.035       0
Bank Sta=5068.7,5074.1
Exp/Cntr=0.3,0.1

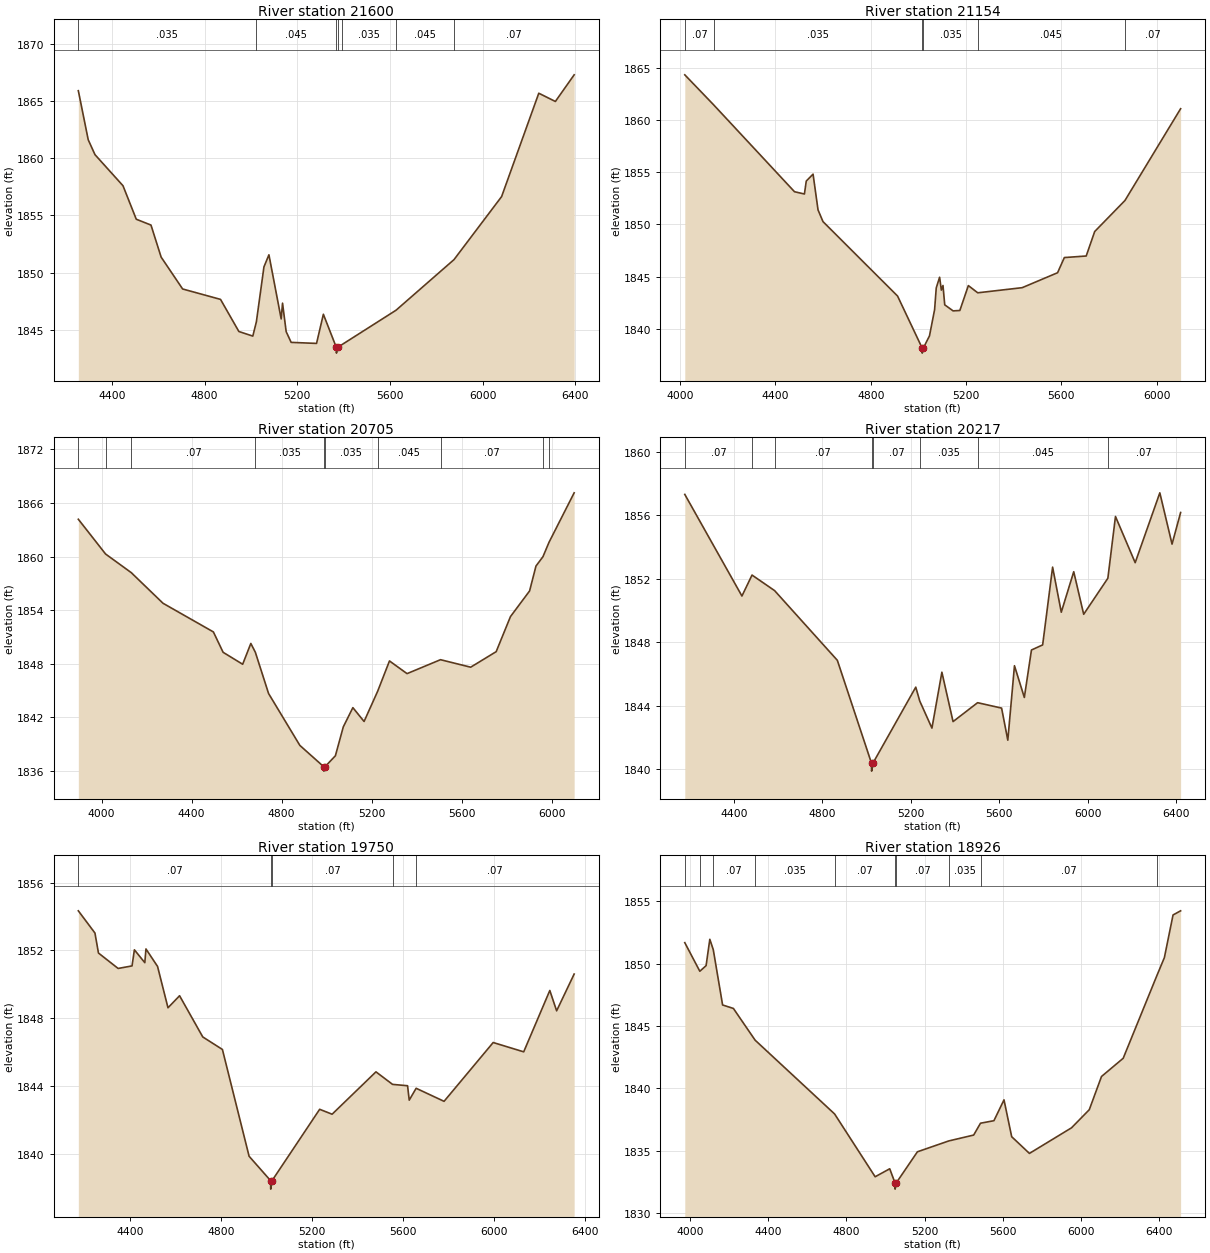
Type RM Length L Ch R = 1,21600,446,446,446
BEGIN DESCRIPTION:
Clear Fork Trib12 25.0
END DESCRIPTION:
XS GIS Cut Line= 3
      1461954.96      6940888.03      1461355.00      6941338.00
      1460155.00      6942038.00
#Sta/Elev= 30
  4255.3 1865.91  4298.0 1861.62  4327.1 1860.32  4448.0 1857.60  4505.3 1854.67
  4568.8 1854.16  4612.5 1851.36  4705.3 1848.57  4868.8 1847.66  4948.0 1844.85
  5008.1 1844.45  5023.5 1845.70  5056.1 1850.50  5077.6 1851.56  5130.5 1845.95
  5136.3 1847.33  5152.0 1844.84  5173.5 1843.90  5283.1 1843.81  5312.5 1846.36
  5368.4 1843.46  5368.9 1842.96  5373.9 1843.46  5393.2 1843.71  5625.9 1846.71
  5876.2 1851.14  6081.5 1856.65  6241.9 1865.69  6313.5 1864.97  6394.5 1867.30
#Mann=7,-1,0
  4255.3   0.035       0  5023.5   0.045       0  5368.4   0.035       0
  5373.9   0.045       0  5393.2   0.035       0  5625.9   0.045       0
  5876.2    0.07       0
Bank Sta=5368.4,5373.9
Exp/Cntr=0.3,0.1

Type RM Length L Ch R = 1,21154,449,449,449
BEGIN DESCRIPTION:
Clear Fork Trib12 24.0
END DESCRIPTION:
XS GIS Cut Line= 3
      1461691.76      6940336.39      1461055.00      6941088.00
      1460304.97      6941888.03
#Sta/Elev= 30
  4019.4 1864.31  4141.3 1861.42  4479.9 1853.13  4521.6 1852.91  4529.4 1854.15
  4557.9 1854.81  4578.8 1851.39  4599.6 1850.27  4912.7 1843.15  5015.7 1838.19
  5016.1 1837.69  5021.2 1838.19  5046.7 1839.34  5068.2 1841.85  5075.1 1843.93
  5089.2 1844.95  5096.5 1843.72  5103.4 1844.16  5110.7 1842.31  5145.9 1841.73
  5174.2 1841.77  5209.9 1844.15  5249.3 1843.46  5436.0 1843.95  5584.5 1845.38
  5612.9 1846.83  5704.7 1846.98  5740.3 1849.32  5867.4 1852.29  6101.1 1861.07
#Mann=6,-1,0
  4019.4    0.07       0  4141.3   0.035       0  5015.7   0.035       0
  5021.2   0.035       0  5249.3   0.045       0  5867.4    0.07       0
Bank Sta=5015.7,5021.2
Exp/Cntr=0.3,0.1

Type RM Length L Ch R = 1,20705,488,488,488
BEGIN DESCRIPTION:
Clear Fork Trib12 23.0
END DESCRIPTION:
XS GIS Cut Line= 3
      1461636.20      6940239.18      1460705.00      6940838.00
      1459905.01      6941587.99
#Sta/Elev= 30
  3896.9 1864.18  4017.9 1860.29  4132.2 1858.20  4273.3 1854.77  4497.2 1851.56
  4540.3 1849.28  4627.3 1847.94  4663.6 1850.27  4683.7 1849.28  4742.5 1844.66
  4881.5 1838.85  4987.4 1836.47  4987.9 1835.97  4993.6 1836.47  5039.4 1837.69
  5074.6 1840.93  5117.1 1843.08  5166.9 1841.53  5227.2 1844.91  5279.8 1848.31
  5357.9 1846.89  5506.6 1848.45  5640.7 1847.61  5754.0 1849.35  5817.6 1853.28
  5902.5 1856.15  5930.9 1858.94  5962.0 1859.99  5988.7 1861.59  6100.6 1867.14
#Mann=10,-1,0
  3896.9    0.07       0  4017.9   0.035       0  4132.2    0.07       0
  4683.7   0.035       0  4987.4   0.035       0  4993.6   0.035       0
  5227.2   0.045       0  5506.6    0.07       0  5962.0   0.035       0
  5988.7    0.07       0
Bank Sta=4987.4,4993.6
Exp/Cntr=0.3,0.1

Type RM Length L Ch R = 1,20217,467,467,467
BEGIN DESCRIPTION:
Clear Fork Trib12 22.0
END DESCRIPTION:
XS GIS Cut Line= 3
      1461406.97      6940232.26      1460605.39      6940413.00
      1459330.58      6941037.83
#Sta/Elev= 30
  4178.3 1857.32  4436.6 1850.92  4482.2 1852.24  4584.3 1851.26  4867.9 1846.87
  5022.3 1840.39  5022.8 1839.89  5028.7 1840.39  5222.4 1845.18  5240.3 1844.31
  5295.5 1842.60  5340.5 1846.12  5391.0 1843.01  5501.9 1844.20  5610.4 1843.86
  5638.5 1841.84  5668.6 1846.53  5713.2 1844.53  5745.4 1847.52  5796.0 1847.84
  5841.0 1852.74  5880.2 1849.90  5936.5 1852.45  5981.5 1849.77  6090.8 1852.04
  6125.2 1855.93  6214.3 1853.02  6325.7 1857.42  6380.9 1854.19  6419.7 1856.18
#Mann=8,-1,0
  4178.3    0.07       0  4482.2   0.035       0  4584.3    0.07       0
  5022.3    0.07       0  5028.7    0.07       0  5240.3   0.035       0
  5501.9   0.045       0  6090.8    0.07       0
Bank Sta=5022.3,5028.7
Exp/Cntr=0.3,0.1

Type RM Length L Ch R = 1,19750,824,824,824
BEGIN DESCRIPTION:
Clear Fork Trib12 21.0
END DESCRIPTION:
XS GIS Cut Line= 3
      1461316.73      6939815.59      1460505.11      6939977.95
      1459240.36      6940461.41
#Sta/Elev= 30
  4172.3 1854.34  4245.4 1853.03  4260.9 1851.85  4347.4 1850.94  4408.6 1851.09
  4419.0 1852.04  4464.8 1851.28  4469.9 1852.09  4520.9 1851.06  4566.8 1848.62
  4617.8 1849.33  4719.8 1846.90  4806.3 1846.16  4923.7 1839.86  5018.3 1838.42
  5018.8 1837.92  5024.7 1838.42  5234.2 1842.63  5289.0 1842.34  5481.9 1844.84
  5555.0 1844.10  5621.0 1844.02  5628.3 1843.17  5658.7 1843.87  5781.6 1843.10
  5997.7 1846.57  6132.0 1846.02  6246.9 1849.64  6276.9 1848.44  6354.0 1850.61
#Mann=5,-1,0
  4172.3    0.07       0  5018.3    0.07       0  5024.7    0.07       0
  5555.0   0.035       0  5658.7    0.07       0
Bank Sta=5018.3,5024.7
Exp/Cntr=0.3,0.1

Type RM Length L Ch R = 1,18926,775,775,775
BEGIN DESCRIPTION:
Clear Fork Trib12 19.0
END DESCRIPTION:
XS GIS Cut Line= 3
      1461282.06      6939121.14      1460255.00      6939238.00
      1458900.05      6939885.04
#Sta/Elev= 30
  3974.3 1851.67  4051.1 1849.38  4083.2 1849.83  4102.2 1851.94  4119.9 1851.11
  4167.6 1846.68  4222.9 1846.40  4333.9 1843.86  4740.3 1837.95  4947.6 1832.92
  5022.1 1833.56  5049.1 1832.43  5049.6 1831.93  5055.6 1832.43  5163.7 1834.92
  5324.1 1835.79  5451.3 1836.26  5486.3 1837.21  5554.9 1837.41  5606.4 1839.08
  5645.7 1836.13  5736.4 1834.79  5951.6 1836.84  6042.4 1838.29  6104.9 1840.95
  6215.9 1842.41  6387.8 1849.02  6426.4 1850.47  6470.8 1853.89  6509.5 1854.22
#Mann=10,-1,0
  3974.3    0.07       0  4051.1   0.035       0  4119.9    0.07       0
  4333.9   0.035       0  4740.3    0.07       0  5049.1    0.07       0
  5055.6    0.07       0  5324.1   0.035       0  5486.3    0.07       0
  6387.8   0.035       0
Bank Sta=5049.1,5055.6
Exp/Cntr=0.3,0.1

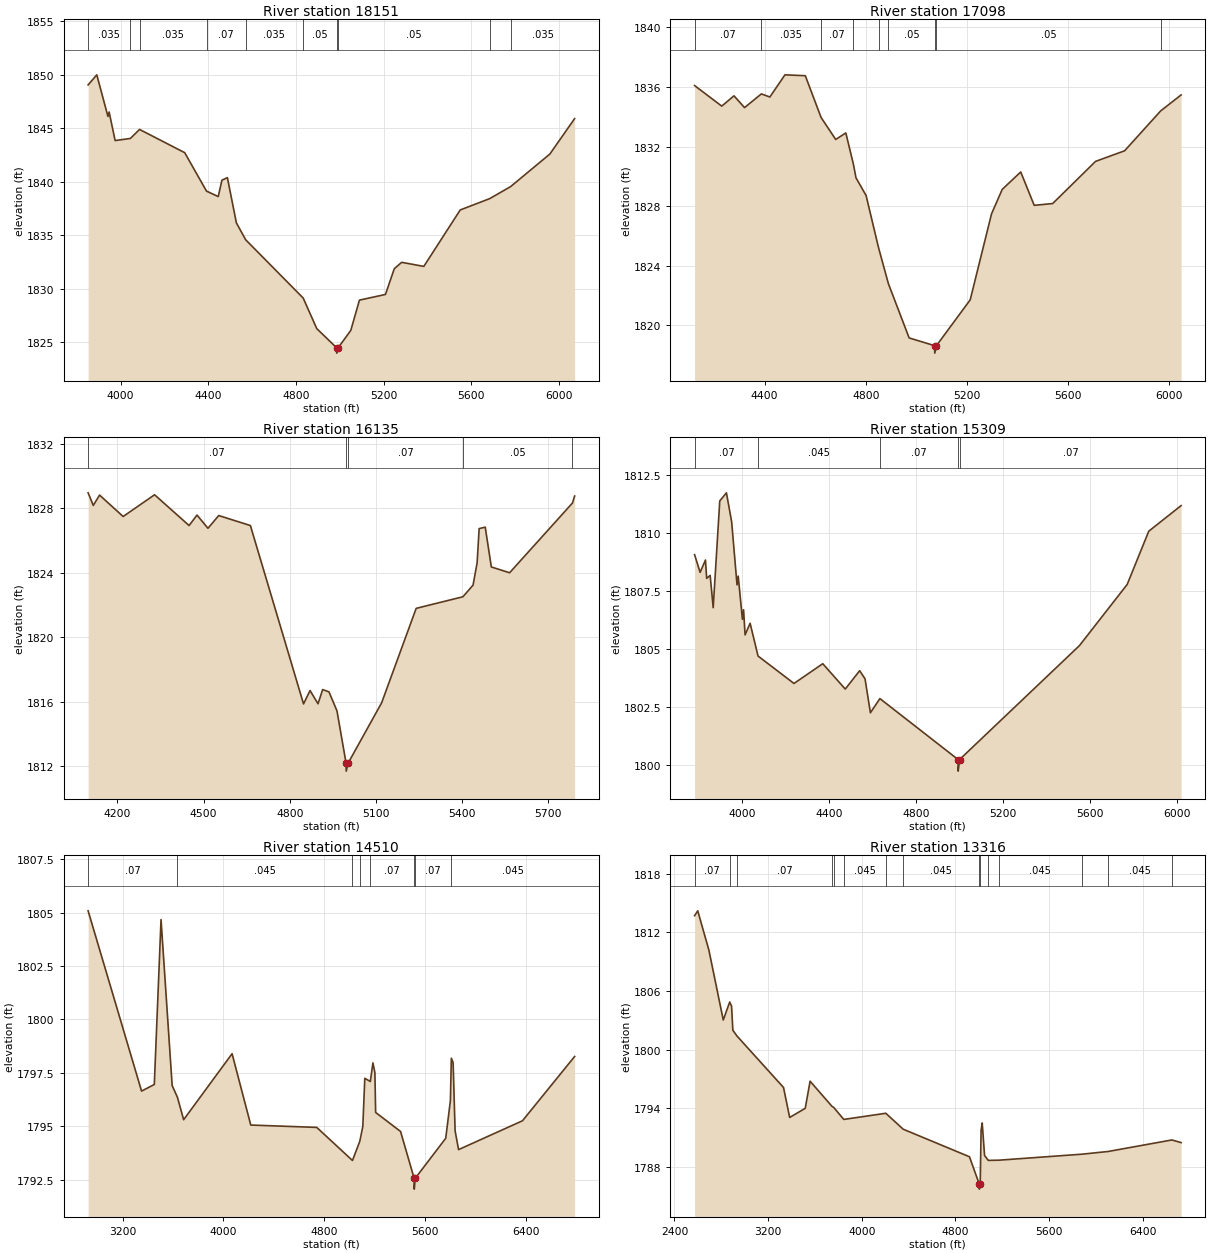
Type RM Length L Ch R = 1,18151,1053,1053,1053
BEGIN DESCRIPTION:
Clear Fork Trib12 17.0
END DESCRIPTION:
XS GIS Cut Line= 3
      1461052.86      6938315.58      1459954.25      6938648.67
      1458922.08      6938933.32
#Sta/Elev= 30
  3852.0 1849.05  3891.6 1849.99  3942.5 1846.10  3947.8 1846.52  3975.2 1843.85
  4044.8 1844.05  4086.6 1844.89  4292.5 1842.72  4392.0 1839.13  4445.4 1838.62
  4462.3 1840.15  4487.2 1840.39  4528.1 1836.17  4570.4 1834.59  4833.0 1829.14
  4894.7 1826.29  4985.3 1824.50  4985.8 1824.00  4992.3 1824.50  5049.9 1826.12
  5089.4 1828.95  5208.1 1829.48  5248.2 1831.88  5282.0 1832.48  5383.0 1832.10
  5549.0 1837.37  5683.6 1838.43  5778.7 1839.55  5957.7 1842.59  6070.7 1845.90
#Mann=10,-1,0
  3852.0   0.035       0  4044.8    0.07       0  4086.6   0.035       0
  4392.0    0.07       0  4570.4   0.035       0  4833.0    0.05       0
  4985.3    0.05       0  4992.3    0.05       0  5683.6   0.045       0
  5778.7   0.035       0
Bank Sta=4985.3,4992.3
Exp/Cntr=0.3,0.1

Type RM Length L Ch R = 1,17098,963,963,963
BEGIN DESCRIPTION:
Clear Fork Trib12 15.0
END DESCRIPTION:
XS GIS Cut Line= 3
      1460622.29      6937780.86      1459755.00      6937738.00
      1458754.27      6938072.52
#Sta/Elev= 30
  4123.0 1836.10  4230.4 1834.72  4278.9 1835.41  4320.5 1834.62  4387.2 1835.54
  4420.6 1835.33  4480.3 1836.82  4560.8 1836.76  4623.1 1833.96  4681.0 1832.48
  4721.0 1832.92  4751.2 1830.80  4761.1 1829.91  4801.1 1828.72  4850.3 1825.22
  4889.3 1822.80  4971.3 1819.16  5072.1 1818.64  5072.6 1818.14  5079.2 1818.64
  5212.8 1821.72  5297.1 1827.49  5339.3 1829.13  5412.5 1830.30  5465.8 1828.06
  5538.8 1828.18  5708.3 1831.01  5823.1 1831.72  5965.9 1834.40  6046.5 1835.47
#Mann=9,-1,0
  4123.0    0.07       0  4387.2   0.035       0  4623.1    0.07       0
  4751.2   0.035       0  4850.3    0.07       0  4889.3    0.05       0
  5072.1    0.05       0  5079.2    0.05       0  5965.9   0.045       0
Bank Sta=5072.1,5079.2
Exp/Cntr=0.3,0.1

Type RM Length L Ch R = 1,16135,826,826,826
BEGIN DESCRIPTION:
Clear Fork Trib12 12.0
END DESCRIPTION:
XS GIS Cut Line= 3
      1460015.43      6936674.26      1459266.22      6937077.21
      1458669.72      6937672.76
#Sta/Elev= 30
  4098.0 1828.97  4116.0 1828.19  4137.9 1828.83  4219.9 1827.50  4329.4 1828.85
  4449.5 1826.94  4477.1 1827.59  4515.2 1826.77  4552.7 1827.56  4662.9 1826.94
  4847.9 1815.87  4870.6 1816.70  4898.3 1815.88  4914.5 1816.76  4936.4 1816.62
  4964.3 1815.44  4996.0 1812.20  4996.5 1811.70  5003.3 1812.20  5119.8 1815.94
  5240.0 1821.80  5402.7 1822.52  5438.0 1823.24  5452.2 1824.63  5459.2 1826.75
  5480.4 1826.84  5501.7 1824.37  5565.3 1824.01  5784.2 1828.34  5791.6 1828.77
#Mann=5,-1,0
  4098.0    0.07       0  4996.0    0.07       0  5003.3    0.07       0
  5402.7    0.05       0  5784.2   0.045       0
Bank Sta=4996,5003.3
Exp/Cntr=0.3,0.1

Type RM Length L Ch R = 1,15309,799,799,799
BEGIN DESCRIPTION:
Clear Fork Trib12 11.0
END DESCRIPTION:
XS GIS Cut Line= 3
      1459941.73      6936003.09      1458805.00      6936438.00
      1458109.49      6937182.47
#Sta/Elev= 30
  3782.9 1809.06  3808.4 1808.30  3832.9 1808.83  3838.5 1808.04  3854.4 1808.17
  3868.5 1806.78  3898.6 1811.37  3929.3 1811.72  3953.3 1810.47  3978.0 1807.76
  3983.4 1808.14  4002.7 1806.28  4008.1 1806.69  4015.0 1805.61  4038.1 1806.11
  4074.6 1804.70  4239.8 1803.52  4372.0 1804.37  4475.4 1803.28  4541.6 1804.07
  4566.3 1803.72  4591.0 1802.26  4634.6 1802.87  4993.7 1800.25  4994.2 1799.75
  5001.0 1800.25  5551.8 1805.15  5771.1 1807.78  5870.3 1810.07  6018.8 1811.17
#Mann=5,-1,0
  3782.9    0.07       0  4074.6   0.045       0  4634.6    0.07       0
  4993.7    0.07       0  5001.0    0.07       0
Bank Sta=4993.7,5001
Exp/Cntr=0.3,0.1

Type RM Length L Ch R = 1,14510,1194,1194,1194
BEGIN DESCRIPTION:
Mapping XS aba71552
END DESCRIPTION:
XS GIS Cut Line= 3
      1460504.20      6935454.48      1458448.68      6935773.92
      1456908.51      6936668.88
#Sta/Elev= 30
  2926.0 1805.08  3350.2 1796.64  3451.4 1796.95  3504.8 1804.67  3593.1 1796.90
  3634.9 1796.35  3684.2 1795.30  4068.7 1798.39  4217.1 1795.05  4740.7 1794.94
  5024.2 1793.39  5082.4 1794.29  5106.3 1794.98  5122.1 1797.24  5165.9 1797.09
  5186.6 1797.96  5202.3 1797.50  5208.1 1795.64  5405.9 1794.75  5514.1 1792.55
  5514.6 1792.05  5521.4 1792.55  5764.4 1794.43  5801.6 1796.20  5809.1 1798.18
  5823.1 1797.97  5838.9 1794.78  5866.3 1793.90  6373.6 1795.25  6787.5 1798.26
#Mann=8,-1,0
  2926.0    0.07       0  3634.9   0.045       0  5024.2    0.07       0
  5082.4   0.045       0  5165.9    0.07       0  5514.1   0.045       0
  5521.4    0.07       0  5809.1   0.045       0
Bank Sta=5514.1,5521.4
Exp/Cntr=0.3,0.1

Type RM Length L Ch R = 1,13316,141,141,141
BEGIN DESCRIPTION:
Mapping XS bab3cedf
END DESCRIPTION:
XS GIS Cut Line= 4
      1461011.14      6935322.52      1459157.01      6934850.31
      1458650.07      6934746.14      1456983.36      6934301.69
#Sta/Elev= 30
  2571.8 1813.71  2598.8 1814.21  2694.1 1810.19  2816.8 1803.04  2871.8 1804.88
  2887.7 1804.46  2898.6 1802.00  2933.5 1801.41  3331.4 1796.14  3384.2 1793.07
  3517.2 1794.01  3558.5 1796.78  3745.5 1794.21  3760.9 1794.09  3846.5 1792.87
  4205.4 1793.50  4353.8 1791.87  4920.0 1789.05  5004.0 1786.24  5004.5 1785.74
  5011.8 1786.24  5019.1 1791.75  5028.6 1792.51  5048.9 1789.18  5080.8 1788.68
  5170.4 1788.70  5877.3 1789.31  6103.7 1789.59  6649.0 1790.77  6727.6 1790.50
#Mann=15,-1,0
  2571.8    0.07       0  2871.8   0.035       0  2933.5    0.07       0
  3745.5   0.045       0  3760.9   0.035       0  3846.5   0.045       0
  4205.4   0.035       0  4353.8   0.045       0  5004.0   0.045       0
  5011.8   0.045       0  5080.8   0.035       0  5170.4   0.045       0
  5877.3   0.035       0  6103.7   0.045       0  6649.0   0.035       0
Bank Sta=5004,5011.8
Exp/Cntr=0.3,0.1

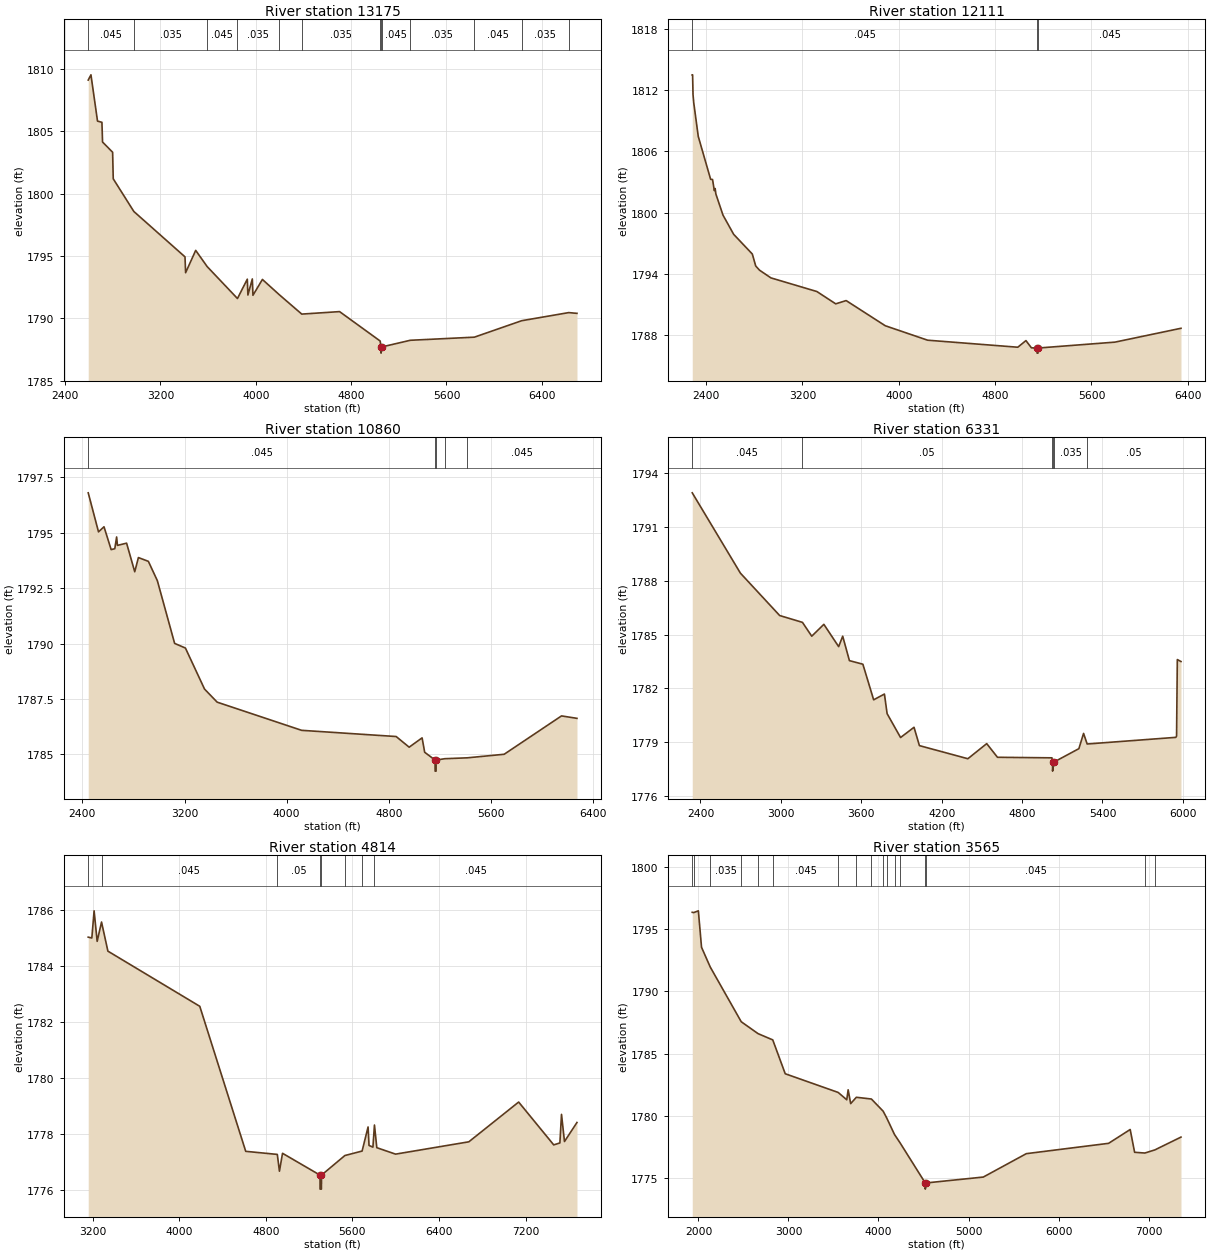
Type RM Length L Ch R = 1,13175,1064,1064,1064
BEGIN DESCRIPTION:
Mapping XS 73fbffe6
END DESCRIPTION:
XS GIS Cut Line= 3
      1460997.27      6935190.58      1458677.85      6934641.97
      1457019.11      6934197.79
#Sta/Elev= 30
  2594.3 1809.12  2617.2 1809.54  2672.2 1805.83  2709.3 1805.73  2714.5 1804.15
  2799.0 1803.33  2804.2 1801.20  2977.1 1798.58  3406.3 1794.94  3411.4 1793.67
  3496.0 1795.46  3592.3 1794.16  3846.4 1791.60  3929.0 1793.15  3934.1 1791.88
  3971.2 1793.17  3976.4 1791.86  4055.8 1793.13  4196.8 1791.91  4386.0 1790.35
  4703.2 1790.55  5043.9 1788.19  5050.6 1787.72  5051.1 1787.22  5058.8 1787.72
  5296.6 1788.25  5834.2 1788.50  6231.2 1789.82  6625.6 1790.47  6694.9 1790.41
#Mann=13,-1,0
  2594.3   0.045       0  2977.1   0.035       0  3592.3   0.045       0
  3846.4   0.035       0  4196.8   0.045       0  4386.0   0.035       0
  5043.9   0.045       0  5050.6   0.035       0  5058.8   0.045       0
  5296.6   0.035       0  5834.2   0.045       0  6231.2   0.035       0
  6625.6   0.045       0
Bank Sta=5050.6,5058.8
Exp/Cntr=0.3,0.1

Type RM Length L Ch R = 1,12111,1251,1251,1251
BEGIN DESCRIPTION:
Clear Fork Trib12 10.0
END DESCRIPTION:
XS GIS Cut Line= 3
      1461275.05      6935086.41      1458904.73      6933762.88
      1457582.82      6933525.82
#Sta/Elev= 30
  2285.2 1813.52  2288.1 1813.52  2291.6 1811.59  2297.3 1810.81  2335.0 1807.48
  2437.8 1803.26  2453.8 1803.24  2468.5 1802.15  2475.5 1802.35  2481.2 1801.82
  2540.6 1799.74  2628.9 1797.86  2784.0 1795.92  2812.1 1794.75  2843.4 1794.34
  2938.1 1793.58  3319.8 1792.24  3476.3 1791.03  3563.1 1791.35  3887.6 1788.88
  4239.4 1787.46  4988.2 1786.77  5055.8 1787.42  5101.3 1786.71  5148.0 1786.69
  5148.5 1786.19  5155.7 1786.19  5156.2 1786.69  5794.9 1787.27  6343.0 1788.63
#Mann=3,-1,0
  2285.2   0.045       0  5148.0   0.045       0  5156.2   0.045       0
Bank Sta=5148,5156.2
Exp/Cntr=0.3,0.1

Type RM Length L Ch R = 1,10860,4529,4529,4529
BEGIN DESCRIPTION:
Clear Fork Trib12 9.0
END DESCRIPTION:
XS GIS Cut Line= 4
      1461240.36      6934155.88      1459712.57      6932885.03
      1459155.56      6932777.77      1457895.32      6932588.32
#Sta/Elev= 30
  2445.5 1796.80  2526.1 1795.04  2569.1 1795.27  2625.0 1794.24  2653.7 1794.28
  2668.0 1794.81  2674.5 1794.43  2746.1 1794.53  2809.9 1793.24  2838.6 1793.88
  2916.7 1793.71  2987.0 1792.84  3122.4 1790.01  3207.0 1789.80  3356.7 1787.95
  3455.7 1787.36  4117.1 1786.09  4858.0 1785.81  4959.8 1785.33  5061.2 1785.75
  5081.5 1785.10  5162.8 1784.75  5163.3 1784.25  5170.7 1784.25  5171.2 1784.75
  5239.3 1784.81  5415.7 1784.85  5704.1 1785.01  6153.4 1786.74  6274.4 1786.63
#Mann=5,-1,0
  2445.5   0.045       0  5162.8   0.045       0  5171.2   0.045       0
  5239.3    0.07       0  5415.7   0.045       0
Bank Sta=5162.8,5171.2
Exp/Cntr=0.3,0.1

Type RM Length L Ch R = 1,6331,1517,1517,1517
BEGIN DESCRIPTION:
Mapping XS 67421f92
END DESCRIPTION:
XS GIS Cut Line= 3
      1461230.94      6933385.83      1460983.40      6930760.03
      1460607.72      6929822.65
#Sta/Elev= 30
  2338.7 1792.89  2698.1 1788.42  2991.2 1786.06  3161.2 1785.68  3230.5 1784.91
  3320.9 1785.57  3431.4 1784.33  3461.5 1784.91  3511.7 1783.55  3612.1 1783.35
  3692.5 1781.37  3772.9 1781.69  3792.9 1780.60  3893.4 1779.27  3993.8 1779.84
  4034.0 1778.82  4395.6 1778.09  4536.2 1778.93  4616.6 1778.17  5023.1 1778.14
  5027.4 1777.90  5027.9 1777.40  5037.0 1777.90  5224.0 1778.65  5259.0 1779.50
  5285.8 1778.91  5947.8 1779.28  5953.1 1779.35  5958.7 1783.61  5986.0 1783.50
#Mann=6,-1,0
  2338.7   0.045       0  3161.2    0.05       0  5023.1   0.035       0
  5027.4    0.05       0  5037.0   0.035       0  5285.8    0.05       0
Bank Sta=5027.4,5037
Exp/Cntr=0.3,0.1

Type RM Length L Ch R = 1,4814,1249,1249,1249
BEGIN DESCRIPTION:
Mapping XS ab0d8369
END DESCRIPTION:
XS GIS Cut Line= 3
      1463566.74      6932003.10      1462323.68      6930690.59
      1460801.33      6928452.74
#Sta/Elev= 30
  3159.9 1785.02  3193.2 1784.99  3214.2 1785.96  3242.5 1784.87  3282.8 1785.56
  3341.6 1784.52  4190.3 1782.55  4614.7 1777.37  4906.4 1777.26  4926.2 1776.66
  4954.5 1777.30  5301.0 1776.52  5301.5 1776.02  5313.9 1776.02  5314.4 1776.52
  5530.6 1777.22  5689.7 1777.38  5744.8 1778.24  5753.6 1777.58  5789.6 1777.52
  5803.7 1778.31  5825.5 1777.50  5998.8 1777.27  6675.5 1777.71  7135.7 1779.13
  7459.7 1777.60  7516.6 1777.67  7531.5 1778.69  7559.0 1777.72  7674.2 1778.40
#Mann=8,-1,0
  3159.9   0.035       0  3282.8   0.045       0  4906.4    0.05       0
  5301.0    0.05       0  5314.4    0.05       0  5530.6   0.045       0
  5689.7   0.035       0  5803.7   0.045       0
Bank Sta=5301,5314.4
Exp/Cntr=0.3,0.1

Type RM Length L Ch R = 1,3565,805,805,805
BEGIN DESCRIPTION:
Clear Fork Trib12 6.0
END DESCRIPTION:
XS GIS Cut Line= 3
      1465392.80      6931273.26      1462781.29      6929661.18
      1460815.06      6928355.27
#Sta/Elev= 30
  1931.0 1796.35  1947.8 1796.33  1998.9 1796.47  2034.2 1793.54  2130.6 1791.96
  2475.0 1787.56  2662.8 1786.60  2825.4 1786.10  2964.0 1783.38  3551.6 1781.88
  3647.5 1781.29  3662.9 1782.09  3691.2 1780.98  3754.1 1781.49  3921.2 1781.35
  4052.0 1780.37  4091.3 1779.83  4178.0 1778.50  4236.1 1777.87  4519.2 1774.61
  4519.7 1774.11  4532.8 1774.61  5164.5 1775.08  5642.6 1776.96  6556.6 1777.79
  6796.2 1778.90  6845.3 1777.07  6958.5 1777.01  7069.9 1777.26  7360.4 1778.29
#Mann=17,-1,0
  1931.0   0.045       0  1947.8    0.07       0  2130.6   0.035       0
  2475.0   0.045       0  2662.8    0.07       0  2825.4   0.045       0
  3551.6   0.035       0  3754.1    0.07       0  3921.2   0.035       0
  4052.0    0.07       0  4091.3   0.035       0  4178.0    0.07       0
  4236.1   0.045       0  4519.2   0.045       0  4532.8   0.045       0
  6958.5    0.07       0  7069.9   0.045       0
Bank Sta=4519.2,4532.8
Exp/Cntr=0.3,0.1