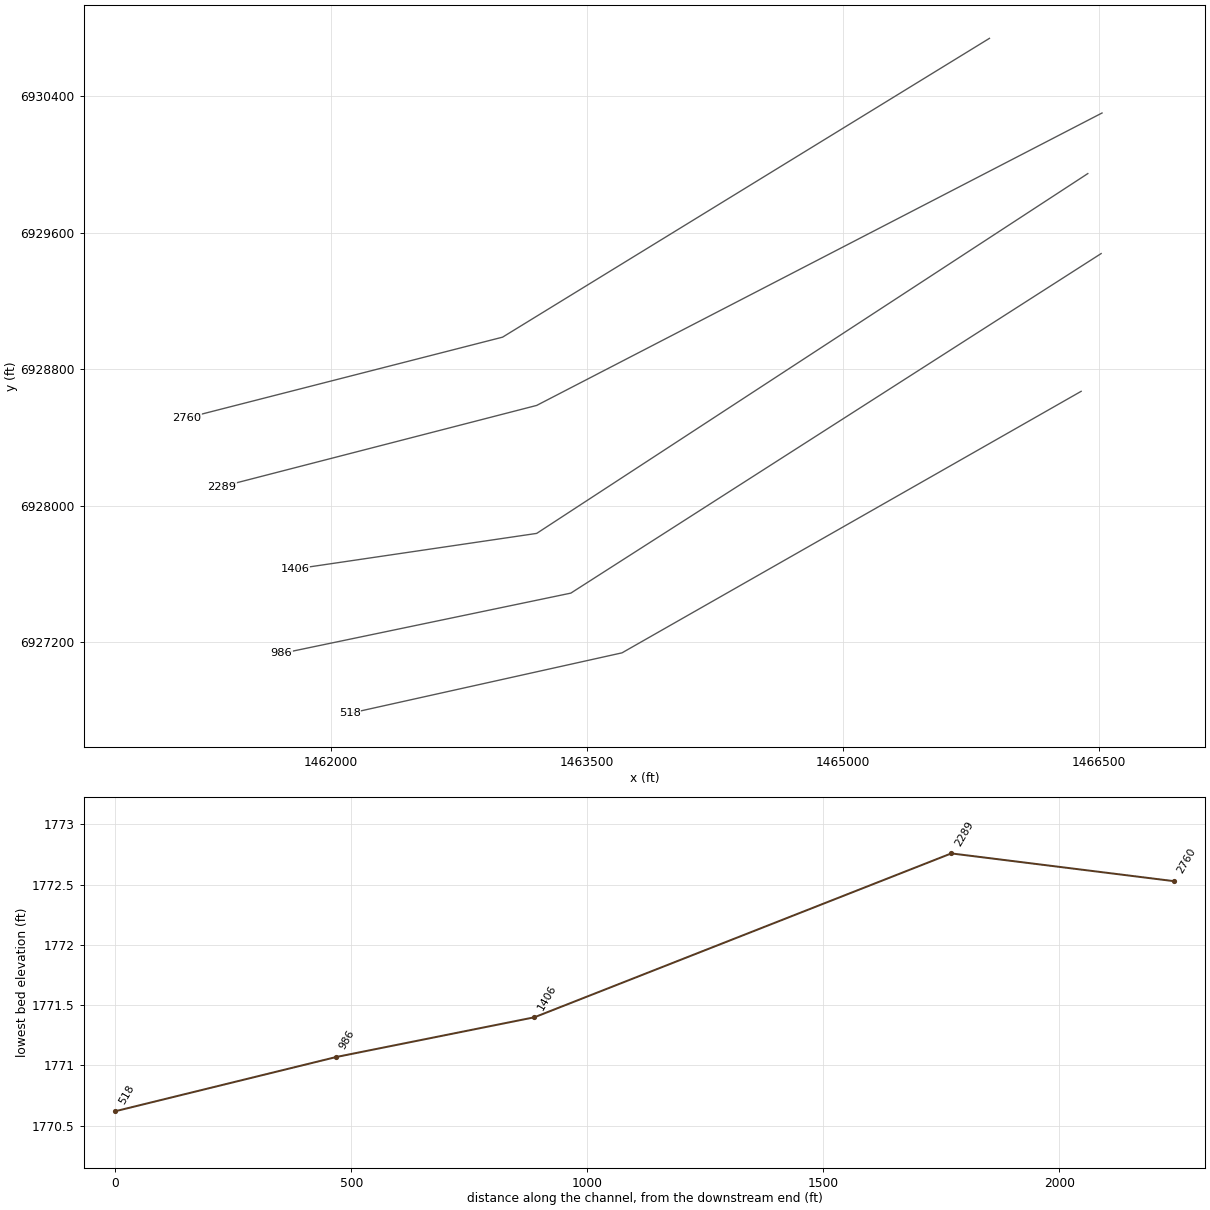
HEC-RAS study Clear Fork Trib12.prj: Clear Fork Trib12 Base Level Engineering

--- Clear Fork Trib12.g01 (geometry) --- (continued)

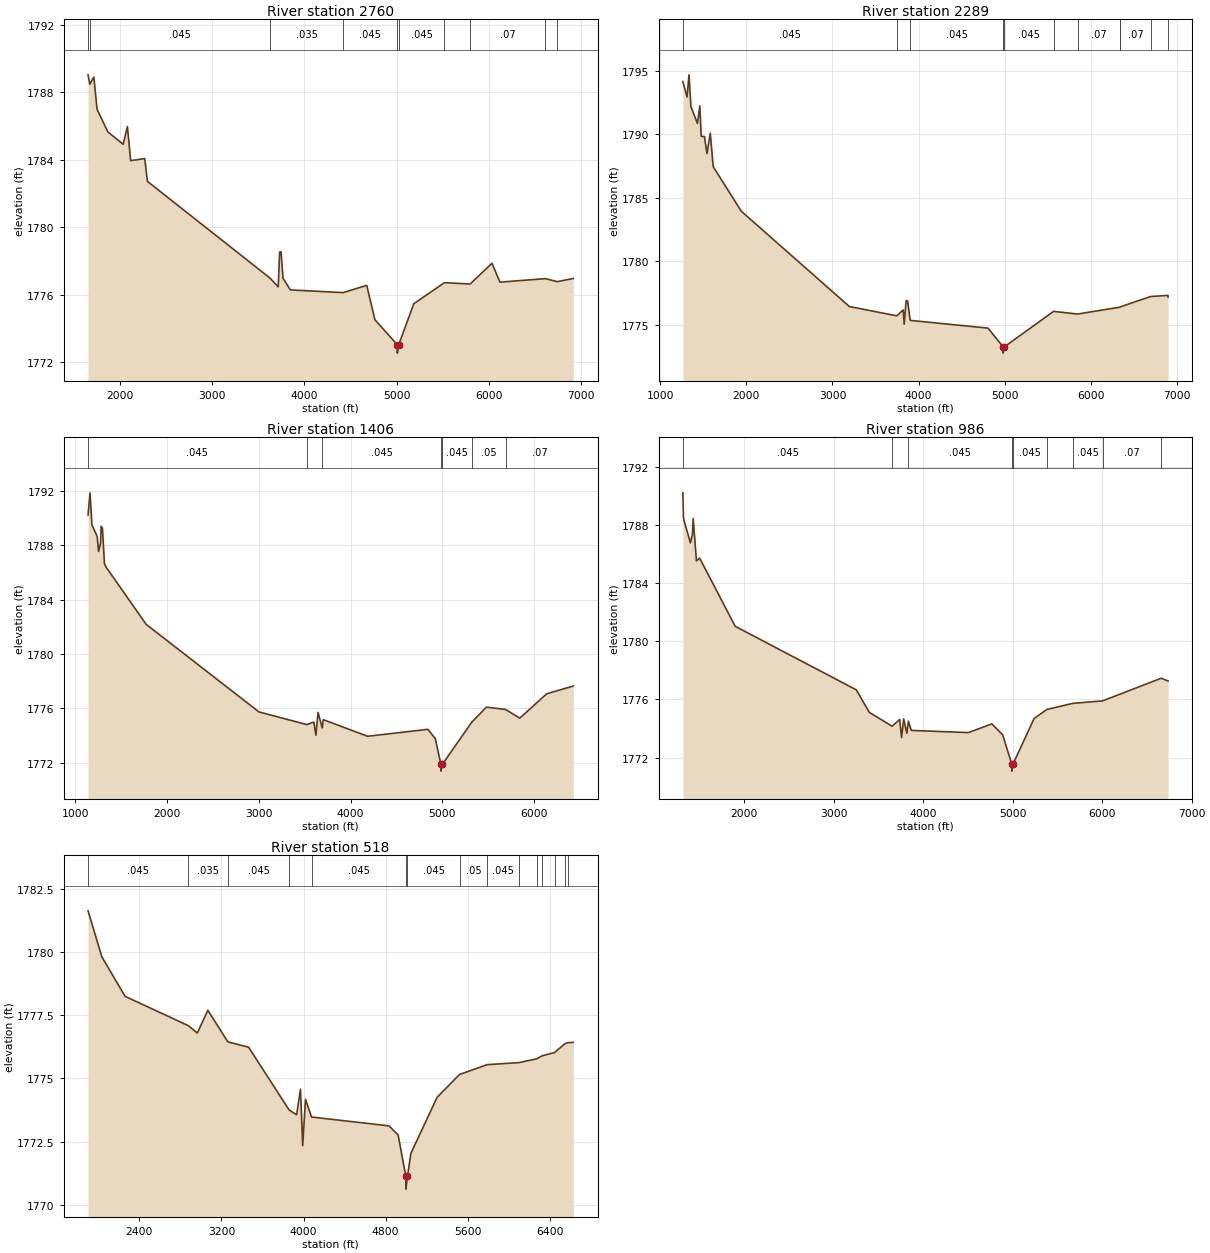
Type RM Length L Ch R = 1,2760,471,471,471
BEGIN DESCRIPTION:
Clear Fork Trib12 5.0
END DESCRIPTION:
XS GIS Cut Line= 3
      1465858.43      6930739.22      1463005.00      6928988.00
      1461155.29      6928514.97
#Sta/Elev= 30
  1656.4 1789.04  1675.3 1788.48  1719.1 1788.91  1754.3 1786.99  1871.6 1785.65
  2036.6 1784.92  2082.8 1785.97  2118.0 1783.95  2270.6 1784.07  2299.5 1782.72
  3630.5 1776.97  3716.7 1776.46  3732.2 1778.53  3747.6 1778.54  3768.9 1776.97
  3848.2 1776.28  4419.5 1776.12  4675.8 1776.55  4764.6 1774.51  5006.8 1773.03
  5007.3 1772.53  5022.5 1773.03  5185.5 1775.46  5517.6 1776.71  5795.6 1776.63
  6032.5 1777.86  6119.3 1776.74  6610.9 1776.95  6739.7 1776.77  6913.6 1776.96
#Mann=10,-1,0
  1656.4    0.07       0  1675.3   0.045       0  3630.5   0.035       0
  4419.5   0.045       0  5006.8   0.045       0  5022.5   0.045       0
  5517.6    0.05       0  5795.6    0.07       0  6610.9    0.05       0
  6739.7    0.07       0
Bank Sta=5006.8,5022.5
Exp/Cntr=0.3,0.1

Type RM Length L Ch R = 1,2289,883,883,883
BEGIN DESCRIPTION:
Clear Fork Trib12 4.0
END DESCRIPTION:
XS GIS Cut Line= 3
      1466518.11      6930301.69      1463205.00      6928588.00
      1461359.02      6928112.12
#Sta/Elev= 30
  1262.1 1794.16  1310.6 1792.94  1333.2 1794.69  1355.7 1792.19  1431.1 1790.86
  1458.9 1792.24  1475.4 1789.85  1513.3 1789.82  1541.8 1788.49  1580.5 1790.09
  1614.6 1787.45  1941.1 1783.94  3196.4 1776.43  3747.1 1775.70  3821.3 1776.16
  3832.9 1775.04  3855.1 1776.89  3871.6 1776.89  3902.8 1775.34  4806.8 1774.73
  4981.5 1773.26  4982.0 1772.76  4997.2 1773.26  5567.8 1776.05  5847.1 1775.84
  6337.1 1776.38  6344.8 1776.41  6695.2 1777.22  6896.5 1777.31  6898.5 1777.18
#Mann=11,-1,0
  1262.1   0.045       0  3747.1   0.035       0  3902.8   0.045       0
  4981.5   0.045       0  4997.2   0.045       0  5567.8    0.05       0
  5847.1    0.07       0  6337.1    0.05       0  6344.8    0.07       0
  6695.2    0.05       0  6896.5    0.07       0
Bank Sta=4981.5,4997.2
Exp/Cntr=0.3,0.1

Type RM Length L Ch R = 1,1406,420,420,420
BEGIN DESCRIPTION:
Clear Fork Trib12 3.0
END DESCRIPTION:
XS GIS Cut Line= 3
      1466434.77      6929946.65      1463205.00      6927838.00
      1461788.18      6927629.22
#Sta/Elev= 30
  1138.1 1790.21  1159.4 1791.84  1180.5 1789.47  1237.8 1788.64  1252.9 1787.53
  1274.0 1788.14  1281.1 1789.38  1295.1 1789.22  1317.0 1786.64  1331.3 1786.42
  1771.7 1782.18  3000.9 1775.75  3522.1 1774.82  3600.0 1775.00  3621.9 1774.04
  3645.3 1775.71  3690.5 1774.58  3702.6 1775.18  4185.2 1773.96  4842.9 1774.47
  4923.6 1773.78  4984.4 1771.90  4984.9 1771.40  5000.2 1771.90  5321.6 1775.00
  5480.5 1776.10  5689.5 1775.93  5844.4 1775.29  6137.5 1777.08  6427.4 1777.65
#Mann=7,-1,0
  1138.1   0.045       0  3522.1   0.035       0  3690.5   0.045       0
  4984.4   0.045       0  5000.2   0.045       0  5321.6    0.05       0
  5689.5    0.07       0
Bank Sta=4984.4,5000.2
Exp/Cntr=0.3,0.1

Type RM Length L Ch R = 1,986,468,468,468
BEGIN DESCRIPTION:
Clear Fork Trib12 2.0
END DESCRIPTION:
XS GIS Cut Line= 3
      1466512.88      6929477.89      1463405.00      6927488.00
      1461709.11      6927134.35
#Sta/Elev= 30
  1314.1 1790.21  1320.3 1788.57  1326.3 1788.31  1399.0 1786.77  1420.1 1787.32
  1429.4 1788.44  1465.8 1785.53  1501.6 1785.72  1898.7 1781.03  3252.4 1776.66
  3397.9 1775.11  3652.1 1774.16  3737.0 1774.62  3758.1 1773.38  3781.4 1774.66
  3817.0 1773.68  3835.0 1774.50  3867.2 1773.87  4505.7 1773.72  4766.8 1774.32
  4887.8 1773.57  4988.9 1771.57  4989.4 1771.07  5004.7 1771.57  5239.4 1774.69
  5381.8 1775.31  5671.8 1775.73  6004.2 1775.90  6659.9 1777.46  6736.8 1777.27
#Mann=9,-1,0
  1314.1   0.045       0  3652.1   0.035       0  3835.0   0.045       0
  4988.9   0.045       0  5004.7   0.045       0  5381.8    0.05       0
  5671.8   0.045       0  6004.2    0.07       0  6659.9   0.045       0
Bank Sta=4988.9,5004.7
Exp/Cntr=0.3,0.1

Type RM Length L Ch R = 1,518,0,0,0
BEGIN DESCRIPTION:
Clear Fork Trib12 1.0
END DESCRIPTION:
XS GIS Cut Line= 3
      1466395.74      6928670.63      1463705.00      6927138.00
      1462108.76      6926783.28
#Sta/Elev= 30
  1899.0 1781.62  2033.9 1779.80  2260.1 1778.24  2877.4 1777.08  2964.7 1776.79
  3067.0 1777.69  3262.6 1776.44  3464.7 1776.23  3859.5 1773.75  3933.0 1773.56
  3970.5 1774.57  3992.1 1772.34  4019.4 1774.17  4078.2 1773.47  4834.5 1773.12
  4922.9 1772.76  4997.9 1771.12  4998.4 1770.62  5013.9 1771.12  5046.8 1772.03
  5302.9 1774.25  5521.2 1775.15  5790.5 1775.54  6099.6 1775.62  6273.4 1775.77
  6327.6 1775.89  6448.7 1776.02  6549.5 1776.37  6582.0 1776.41  6630.8 1776.42
#Mann=15,-1,0
  1899.0   0.045       0  2877.4   0.035       0  3262.6   0.045       0
  3859.5   0.035       0  4078.2   0.045       0  4997.9   0.045       0
  5013.9   0.045       0  5521.2    0.05       0  5790.5   0.045       0
  6099.6    0.07       0  6273.4   0.045       0  6327.6    0.07       0
  6448.7   0.045       0  6549.5    0.07       0  6582.0   0.045       0
Bank Sta=4997.9,5013.9
Exp/Cntr=0.3,0.1

Chan Stop Cuts=-1