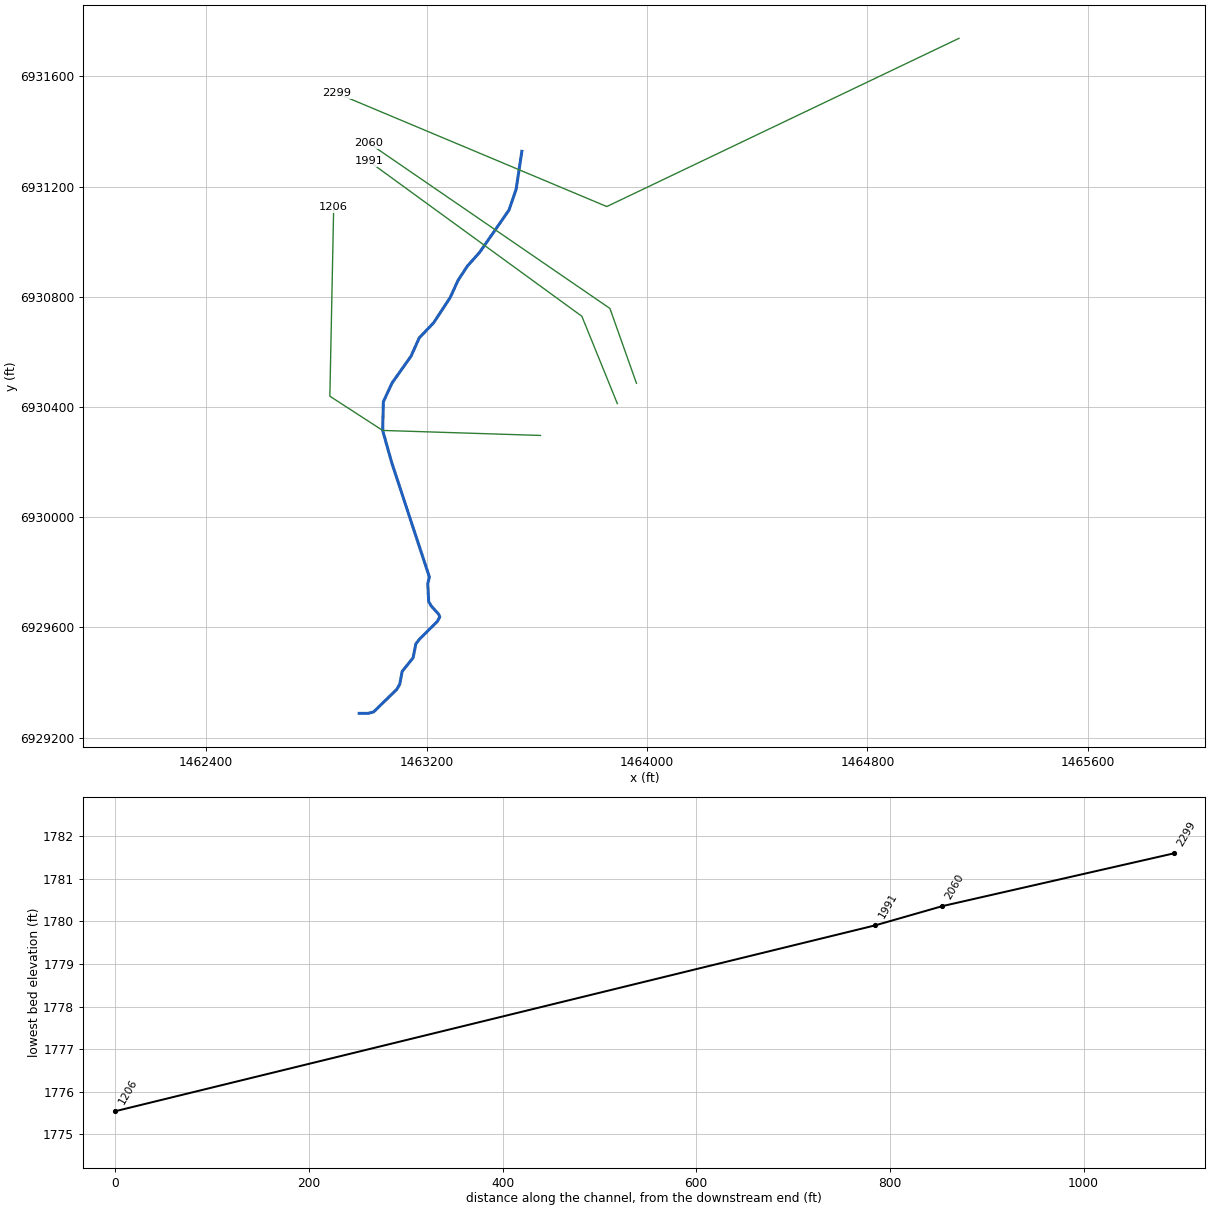
--- Clear Fork Trib12_2.prj (project) ---

Proj Title=Clear Fork Trib12_2 Base Level Engineering
Current Plan=p01
Default Exp/Contr=0.3,0.1
English Units
Geom File=g01
Flow File=f01
Plan File=p01
BEGIN DESCRIPTION:
Clear Fork Trib12_2
END DESCRIPTION:

--- Clear Fork Trib12_2.p01 (plan) ---

Plan Title=Multiple Run
Short Identifier=Multiple
Geom File=g01
Flow File=f01
Subcritical Flow
K Sum by GR= 0
Std Step Tol= 0.01
Critical Tol= 0.01
Num of Std Step Trials= 20
Max Error Tol= 0.3
Flow Tol Ratio= 0.001
Split Flow NTrial= 30
Split Flow Tol= 0.02
Split Flow Ratio= 0.02
Log Output Level= 0
Friction Slope Method= 1
Unsteady Friction Slope Method= 2
Unsteady Bridges Friction Slope Method= 1
Parabolic Critical Depth
Global Vel Dist=  1 , 1 , 1
Global Log Level= 0
CheckData=True
Encroach Param= -1, 0, 0, 0
BEGIN DESCRIPTION:
Multiple Run
END DESCRIPTION:

--- Clear Fork Trib12_2.f01 (steady flow) ---

Flow Title=Multiple
Number of Profiles=7
Profile Names=10-year,25-year,50-year,1pct_min,100-year,1pct_plu,500-year
River Rch & RM= Clear Fork Trib1,Reach-1,2299
      39      47      53      30      60     119      75
Boundary for River Rch & Prof#=Clear Fork Trib1,Reach-1,1
Up Type=0
Dn Type=3
Dn Slope=0.005
Boundary for River Rch & Prof#=Clear Fork Trib1,Reach-1,2
Up Type=0
Dn Type=3
Dn Slope=0.005
Boundary for River Rch & Prof#=Clear Fork Trib1,Reach-1,3
Up Type=0
Dn Type=3
Dn Slope=0.005
Boundary for River Rch & Prof#=Clear Fork Trib1,Reach-1,4
Up Type=0
Dn Type=3
Dn Slope=0.005
Boundary for River Rch & Prof#=Clear Fork Trib1,Reach-1,5
Up Type=0
Dn Type=3
Dn Slope=0.005
Boundary for River Rch & Prof#=Clear Fork Trib1,Reach-1,6
Up Type=0
Dn Type=3
Dn Slope=0.005
Boundary for River Rch & Prof#=Clear Fork Trib1,Reach-1,7
Up Type=0
Dn Type=3
Dn Slope=0.005

--- Clear Fork Trib12_2.g01 (geometry) ---

Geom Title=Existing Conditions

River Reach=Clear Fork Trib1,Reach-1
Reach XY= 30
      1463545.60      6931327.96      1463524.76      6931189.94
      1463498.72      6931114.42      1463391.95      6930960.77
      1463347.68      6930911.30      1463313.83      6930859.21
      1463285.18      6930796.71      1463225.29      6930705.57
      1463173.20      6930650.88      1463143.16      6930584.20
      1463074.24      6930486.82      1463042.99      6930419.11
      1463040.39      6930314.94      1463073.42      6930197.50
      1463209.96      6929782.89      1463204.17      6929758.49
      1463207.33      6929693.99      1463216.17      6929678.26
      1463243.66      6929647.85      1463247.67      6929637.91
      1463238.67      6929621.31      1463174.87      6929558.09
      1463160.86      6929540.30      1463150.81      6929489.74
      1463111.10      6929440.19      1463102.51      6929394.03
      1463091.40      6929374.76      1463007.54      6929293.30
      1462986.89      6929287.92      1462955.00      6929288.00

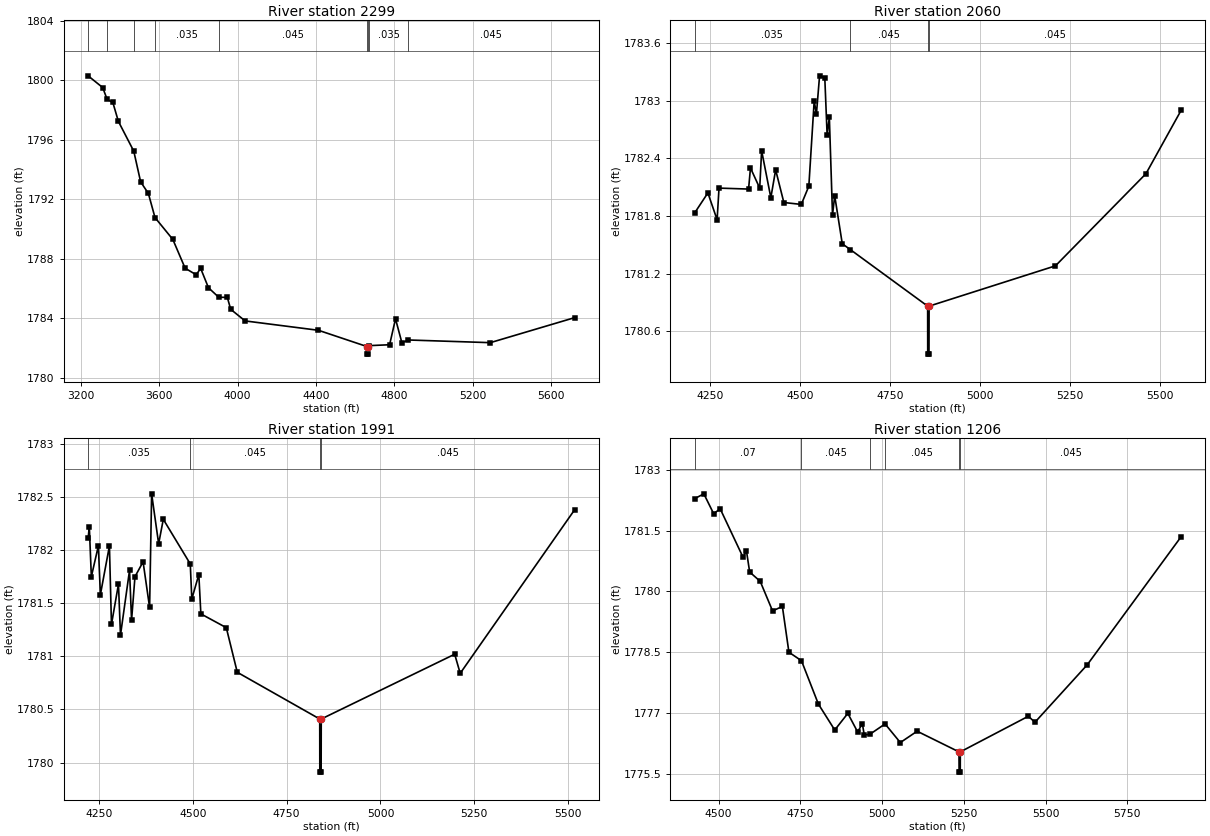
Type RM Length L Ch R = 1,2299,239,239,239
BEGIN DESCRIPTION:
Clear Fork Trib12_2 1.0
END DESCRIPTION:
XS GIS Cut Line= 3
      1465132.19      6931738.10      1463853.88      6931127.54
      1462872.99      6931539.19
#Sta/Elev= 30
  3238.1 1800.29  3312.6 1799.50  3334.9 1798.71  3364.2 1798.50  3392.4 1797.23
  3470.9 1795.23  3505.8 1793.17  3545.3 1792.39  3579.1 1790.77  3670.1 1789.30
  3732.7 1787.37  3789.1 1786.93  3811.8 1787.36  3851.6 1786.06  3903.9 1785.42
  3947.9 1785.41  3965.0 1784.61  4038.6 1783.83  4412.6 1783.20  4661.9 1782.10
  4662.1 1781.60  4665.6 1781.60  4665.9 1782.10  4671.4 1782.17  4775.2 1782.23
  4805.3 1783.97  4837.9 1782.36  4870.1 1782.55  5288.5 1782.37  5718.5 1784.05
#Mann=9,-1,0
  3238.1    0.07       0  3334.9   0.045       0  3470.9    0.07       0
  3579.1   0.035       0  3903.9   0.045       0  4661.9   0.045       0
  4665.9   0.045       0  4671.4   0.035       0  4870.1   0.045       0
Bank Sta=4661.9,4665.9
Exp/Cntr=0.3,0.1

Type RM Length L Ch R = 1,2060,69,69,69
BEGIN DESCRIPTION:
Clear Fork Trib 12_2 5.0
END DESCRIPTION:
XS GIS Cut Line= 3
      1463961.60      6930486.08      1463865.25      6930757.69
      1462989.71      6931358.23
#Sta/Elev= 30
  4207.8 1781.83  4244.7 1782.04  4270.3 1781.76  4275.6 1782.09  4357.6 1782.08
  4362.9 1782.30  4388.5 1782.09  4393.8 1782.48  4419.4 1781.99  4432.7 1782.28
  4455.5 1781.94  4503.9 1781.92  4524.8 1782.11  4539.7 1783.00  4545.8 1782.86
  4554.6 1783.26  4569.1 1783.24  4575.6 1782.64  4581.7 1782.83  4590.5 1781.81
  4596.6 1782.01  4617.6 1781.51  4639.7 1781.45  4854.5 1780.86  4854.7 1780.36
  4858.2 1780.36  4858.5 1780.86  5209.1 1781.28  5460.2 1782.24  5557.7 1782.90
#Mann=4,-1,0
  4207.8   0.035       0  4639.7   0.045       0  4854.5   0.045       0
  4858.5   0.045       0
Bank Sta=4854.5,4858.5
Exp/Cntr=0.3,0.1

Type RM Length L Ch R = 1,1991,785,785,785
BEGIN DESCRIPTION:
Clear Fork Trib 12_2 4.0
END DESCRIPTION:
XS GIS Cut Line= 3
      1463892.16      6930412.30      1463763.42      6930729.28
      1462991.60      6931291.15
#Sta/Elev= 30
  4220.8 1782.11  4224.0 1782.22  4229.4 1781.75  4248.1 1782.04  4253.5 1781.58
  4277.6 1782.04  4283.0 1781.30  4301.7 1781.68  4307.1 1781.20  4331.2 1781.81
  4336.6 1781.34  4345.7 1781.75  4367.3 1781.89  4384.7 1781.46  4390.1 1782.53
  4408.8 1782.06  4421.2 1782.29  4493.1 1781.87  4497.2 1781.54  4515.9 1781.77
  4521.3 1781.40  4589.1 1781.27  4618.4 1780.85  4838.2 1780.41  4838.4 1779.91
  4841.9 1779.91  4842.2 1780.41  5197.9 1781.02  5212.6 1780.84  5517.6 1782.38
#Mann=4,-1,0
  4220.8   0.035       0  4493.1   0.045       0  4838.2   0.045       0
  4842.2   0.045       0
Bank Sta=4838.2,4842.2
Exp/Cntr=0.3,0.1

Type RM Length L Ch R = 1,1206,0,0,0
BEGIN DESCRIPTION:
Clear Fork Trib 12_2 3.0
END DESCRIPTION:
XS GIS Cut Line= 4
      1463613.30      6930296.71      1463040.39      6930314.94
      1462848.74      6930439.14      1462862.59      6931124.82
#Sta/Elev= 30
  4426.8 1782.29  4455.1 1782.41  4485.1 1781.92  4505.1 1782.04  4575.2 1780.84
  4585.2 1781.01  4595.2 1780.48  4627.4 1780.25  4665.2 1779.52  4695.2 1779.63
  4715.2 1778.50  4753.6 1778.29  4805.3 1777.22  4855.3 1776.58  4895.3 1776.99
  4925.4 1776.53  4939.7 1776.74  4945.4 1776.46  4962.0 1776.47  5009.2 1776.73
  5055.8 1776.27  5107.2 1776.55  5235.2 1776.04  5235.5 1775.54  5239.0 1775.54
  5239.2 1776.04  5447.3 1776.92  5467.3 1776.77  5627.3 1778.19  5914.2 1781.35
#Mann=6,-1,0
  4426.8    0.07       0  4753.6   0.045       0  4962.0   0.035       0
  5009.2   0.045       0  5235.2   0.035       0  5239.2   0.045       0
Bank Sta=5235.2,5239.2
Exp/Cntr=0.3,0.1

Chan Stop Cuts=-1