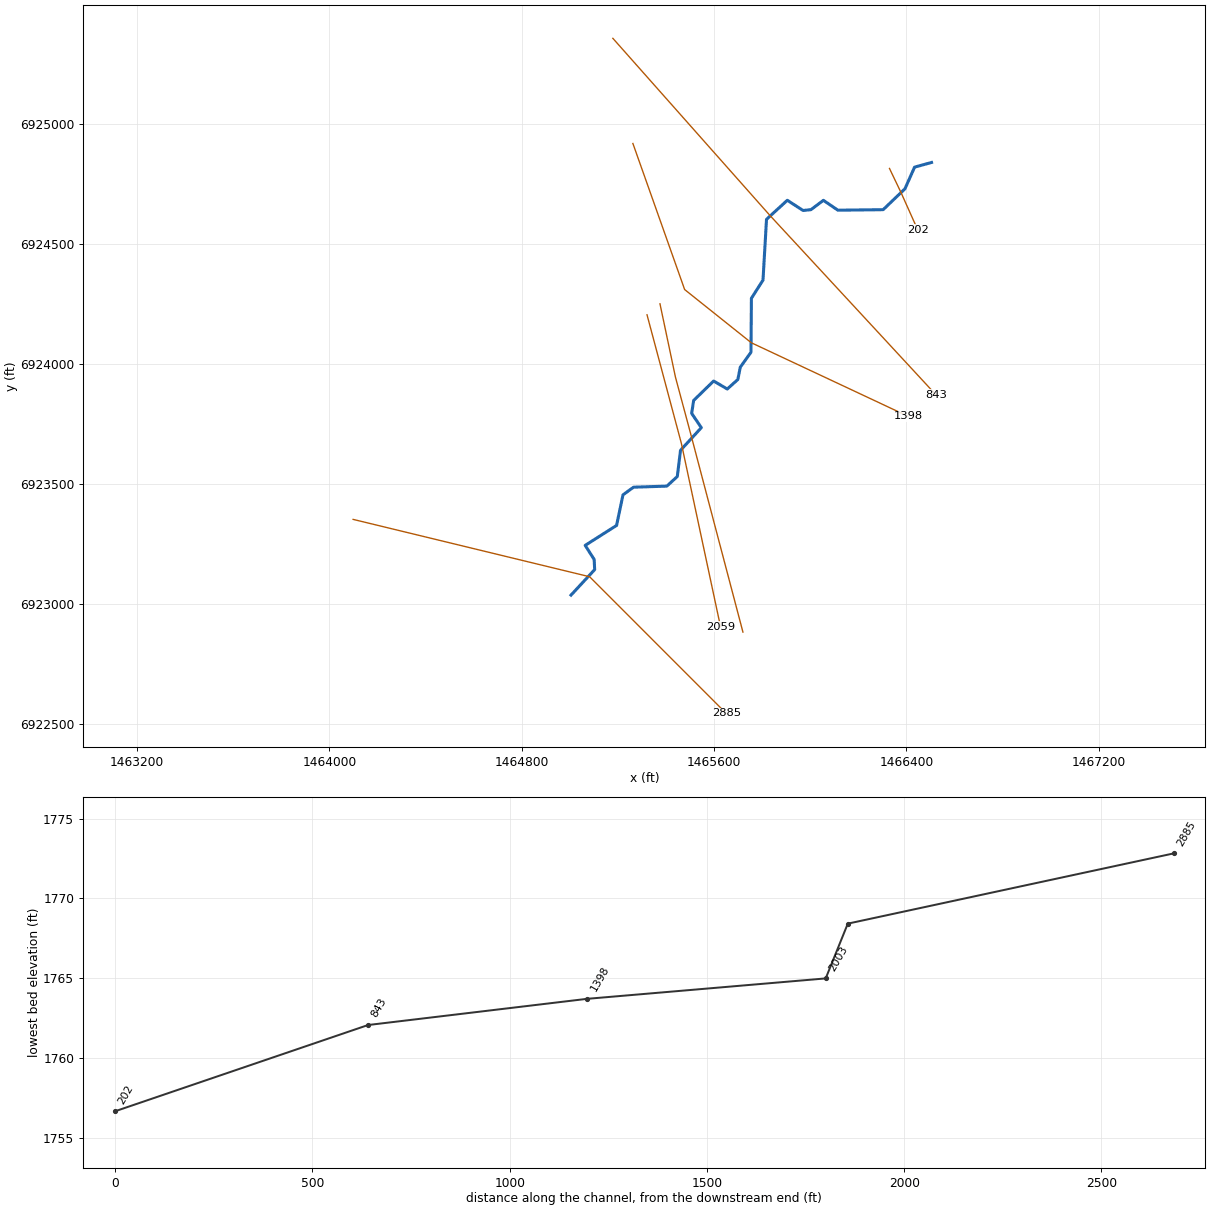
--- Clear Fork Trib13.prj (project) ---

Proj Title=Clear Fork Trib13 Base Level Engineering
Current Plan=p01
Default Exp/Contr=0.3,0.1
English Units
Geom File=g01
Flow File=f01
Plan File=p01
BEGIN DESCRIPTION:
Clear Fork Trib13
END DESCRIPTION:

--- Clear Fork Trib13.p01 (plan) ---

Plan Title=Multiple Run
Short Identifier=Multiple
Geom File=g01
Flow File=f01
Subcritical Flow
K Sum by GR= 0
Std Step Tol= 0.01
Critical Tol= 0.01
Num of Std Step Trials= 20
Max Error Tol= 0.3
Flow Tol Ratio= 0.001
Split Flow NTrial= 30
Split Flow Tol= 0.02
Split Flow Ratio= 0.02
Log Output Level= 0
Friction Slope Method= 1
Unsteady Friction Slope Method= 2
Unsteady Bridges Friction Slope Method= 1
Parabolic Critical Depth
Global Vel Dist=  1 , 1 , 1
Global Log Level= 0
CheckData=True
Encroach Param= -1, 0, 0, 0
BEGIN DESCRIPTION:
Multiple Run
END DESCRIPTION:

--- Clear Fork Trib13.f01 (steady flow) ---

Flow Title=Multiple
Number of Profiles=7
Profile Names=10-year,25-year,50-year,1pct_min,100-year,1pct_plu,500-year
River Rch & RM= Clear Fork Trib1,Reach-1,2885
     255     354     436     267     533    1064     807
River Rch & RM= Clear Fork Trib1,Reach-1,1398
     282     394     487     299     598    1192     911
Boundary for River Rch & Prof#=Clear Fork Trib1,Reach-1,1
Up Type=0
Dn Type=3
Dn Slope=0.005
Boundary for River Rch & Prof#=Clear Fork Trib1,Reach-1,2
Up Type=0
Dn Type=3
Dn Slope=0.005
Boundary for River Rch & Prof#=Clear Fork Trib1,Reach-1,3
Up Type=0
Dn Type=3
Dn Slope=0.005
Boundary for River Rch & Prof#=Clear Fork Trib1,Reach-1,4
Up Type=0
Dn Type=3
Dn Slope=0.005
Boundary for River Rch & Prof#=Clear Fork Trib1,Reach-1,5
Up Type=0
Dn Type=3
Dn Slope=0.005
Boundary for River Rch & Prof#=Clear Fork Trib1,Reach-1,6
Up Type=0
Dn Type=3
Dn Slope=0.005
Boundary for River Rch & Prof#=Clear Fork Trib1,Reach-1,7
Up Type=0
Dn Type=3
Dn Slope=0.005

--- Clear Fork Trib13.g01 (geometry) ---

Geom Title=Existing Conditions

River Reach=Clear Fork Trib1,Reach-1
Reach XY= 30
      1465005.00      6923038.00      1465103.40      6923144.05
      1465101.41      6923186.37      1465064.03      6923245.01
      1465194.61      6923327.90      1465221.27      6923455.22
      1465265.27      6923487.01      1465403.77      6923491.44
      1465447.27      6923531.50      1465460.56      6923640.42
      1465547.16      6923734.60      1465506.99      6923794.05
      1465515.20      6923847.72      1465598.32      6923928.70
      1465655.21      6923895.47      1465699.17      6923935.16
      1465709.22      6923986.19      1465753.80      6924048.50
      1465755.52      6924272.78      1465803.78      6924348.50
      1465818.37      6924601.38      1465904.90      6924680.66
      1465970.36      6924638.29      1466003.35      6924641.64
      1466054.99      6924680.41      1466115.44      6924639.38
      1466303.55      6924641.53      1466394.24      6924728.31
      1466434.36      6924818.45      1466505.00      6924838.00

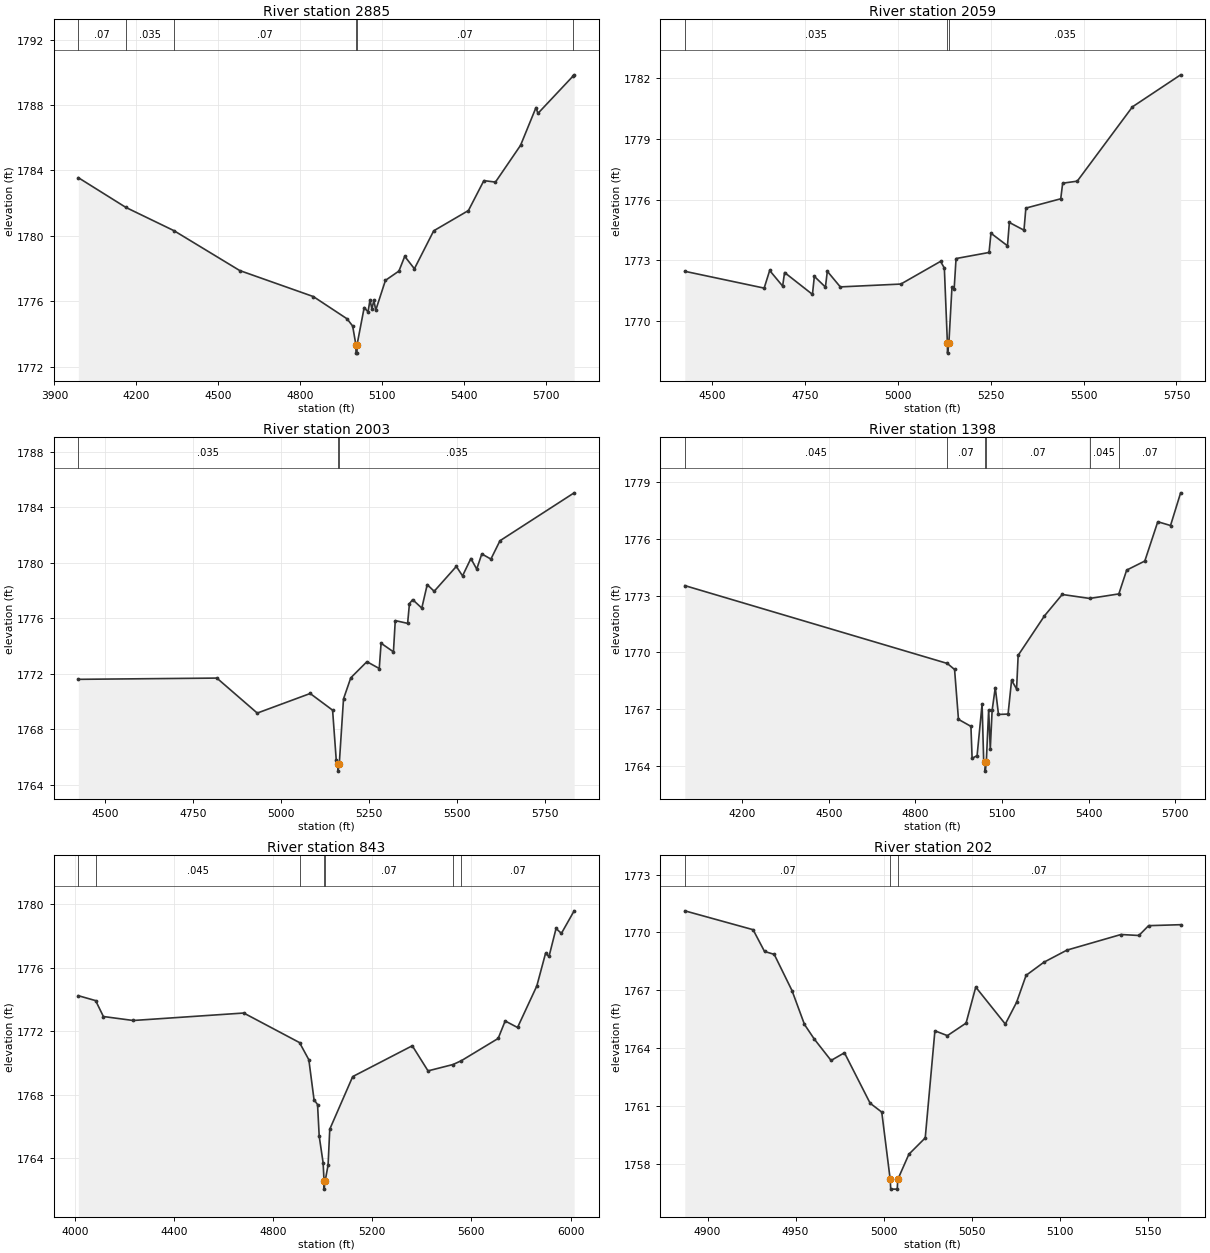
Type RM Length L Ch R = 1,2885,826,826,826
BEGIN DESCRIPTION:
Clear Fork Trib13 5.0
END DESCRIPTION:
XS GIS Cut Line= 3
      1464098.53      6923353.11      1465082.41      6923114.50
      1465650.71      6922546.05
#Sta/Elev= 30
  3987.6 1783.55  4161.9 1781.73  4337.8 1780.31  4578.8 1777.87  4848.3 1776.28
  4971.8 1774.92  4992.4 1774.48  5004.4 1773.32  5004.7 1772.82  5008.2 1772.82
  5008.4 1773.32  5034.7 1775.61  5048.8 1775.34  5055.9 1776.07  5063.0 1775.53
  5070.1 1776.05  5077.1 1775.45  5112.5 1777.27  5162.0 1777.84  5183.2 1778.74
  5218.6 1777.98  5289.3 1780.30  5416.5 1781.54  5473.1 1783.37  5515.5 1783.28
  5607.5 1785.53  5664.0 1787.84  5671.1 1787.48  5798.4 1789.74  5803.8 1789.84
#Mann=6,-1,0
  3987.6    0.07       0  4161.9   0.035       0  4337.8    0.07       0
  5004.4    0.07       0  5008.4    0.07       0  5798.4   0.035       0
Bank Sta=5004.4,5008.4
Exp/Cntr=0.3,0.1

Type RM Length L Ch R = 1,2059,56,56,56
BEGIN DESCRIPTION:
Mapping XS 6a949944
END DESCRIPTION:
XS GIS Cut Line= 3
      1465321.23      6924204.25      1465463.90      6923670.35
      1465627.10      6922906.43
#Sta/Elev= 30
  4427.4 1772.46  4640.9 1771.63  4655.7 1772.50  4690.6 1771.73  4695.8 1772.40
  4770.8 1771.32  4775.9 1772.21  4805.7 1771.68  4810.8 1772.46  4845.7 1771.69
  5008.6 1771.83  5115.4 1772.95  5125.6 1772.62  5133.8 1768.92  5134.1 1768.42
  5137.8 1768.92  5146.1 1771.68  5152.0 1771.59  5157.1 1773.09  5245.9 1773.39
  5251.0 1774.34  5295.4 1773.72  5300.5 1774.87  5339.8 1774.49  5344.9 1775.58
  5438.7 1776.04  5443.9 1776.81  5483.1 1776.91  5631.6 1780.58  5761.2 1782.16
#Mann=3,-1,0
  4427.4   0.035       0  5133.8   0.035       0  5137.8   0.035       0
Bank Sta=5133.8,5137.8
Exp/Cntr=0.3,0.1

Type RM Length L Ch R = 1,2003,605,605,605
BEGIN DESCRIPTION:
Mapping XS f56a5fcc
END DESCRIPTION:
XS GIS Cut Line= 4
      1465375.14      6924250.02      1465439.60      6923944.66
      1465502.10      6923712.02      1465720.31      6922884.18
#Sta/Elev= 30
  4424.8 1771.60  4818.5 1771.69  4933.3 1769.17  5083.7 1770.58  5147.4 1769.38
  5157.7 1765.81  5162.3 1765.49  5162.6 1764.99  5166.3 1765.49  5178.4 1770.19
  5199.1 1771.71  5244.9 1772.87  5280.0 1772.38  5285.2 1774.20  5320.3 1773.58
  5325.5 1775.83  5360.6 1775.63  5365.8 1777.05  5374.9 1777.34  5400.9 1776.73
  5416.3 1778.42  5436.1 1777.94  5499.0 1779.73  5516.7 1779.05  5540.4 1780.30
  5557.0 1779.54  5571.4 1780.63  5597.3 1780.26  5623.1 1781.58  5833.9 1785.03
#Mann=3,-1,0
  4424.8   0.035       0  5162.3   0.035       0  5166.3   0.035       0
Bank Sta=5162.3,5166.3
Exp/Cntr=0.3,0.1

Type RM Length L Ch R = 1,1398,555,555,555
BEGIN DESCRIPTION:
Clear Fork Trib13 2.0
END DESCRIPTION:
XS GIS Cut Line= 4
      1465262.50      6924916.91      1465477.79      6924309.24
      1465755.00      6924088.00      1466406.69      6923782.24
#Sta/Elev= 30
  4000.2 1773.53  4910.3 1769.41  4935.6 1769.09  4949.1 1766.45  4992.3 1766.08
  4996.4 1764.39  5013.7 1764.53  5031.0 1767.25  5036.5 1764.27  5041.7 1764.21
  5042.0 1763.71  5045.7 1764.21  5053.8 1766.96  5059.4 1764.87  5065.8 1766.92
  5076.7 1768.13  5087.9 1766.71  5121.1 1766.73  5133.3 1768.52  5150.6 1768.06
  5156.1 1769.84  5247.4 1771.93  5308.8 1773.06  5404.1 1772.85  5505.2 1773.09
  5532.3 1774.35  5595.2 1774.83  5640.2 1776.91  5684.4 1776.71  5719.4 1778.44
#Mann=6,-1,0
  4000.2   0.045       0  4910.3    0.07       0  5041.7    0.07       0
  5045.7    0.07       0  5404.1   0.045       0  5505.2    0.07       0
Bank Sta=5041.7,5045.7
Exp/Cntr=0.3,0.1

Type RM Length L Ch R = 1,843,641,641,641
BEGIN DESCRIPTION:
Mapping XS 55d5512d
END DESCRIPTION:
XS GIS Cut Line= 3
      1465179.18      6925354.37      1465831.96      6924618.27
      1466522.33      6923872.38
#Sta/Elev= 30
  4014.4 1774.24  4084.2 1773.93  4115.5 1772.93  4235.9 1772.68  4681.7 1773.15
  4906.7 1771.29  4944.3 1770.21  4965.2 1767.70  4979.4 1767.39  4986.1 1765.40
  5001.8 1763.74  5005.7 1762.57  5006.0 1762.07  5009.9 1762.57  5021.9 1763.58
  5028.7 1765.84  5121.2 1769.15  5361.6 1771.09  5425.1 1769.51  5525.9 1769.91
  5559.5 1770.15  5708.0 1771.55  5736.3 1772.65  5786.2 1772.24  5863.9 1774.85
  5899.1 1776.90  5913.2 1776.71  5941.6 1778.47  5963.1 1778.16  6014.6 1779.58
#Mann=7,-1,0
  4014.4    0.07       0  4084.2   0.045       0  4906.7    0.07       0
  5005.7    0.07       0  5009.9    0.07       0  5525.9    0.16       0
  5559.5    0.07       0
Bank Sta=5005.7,5009.9
Exp/Cntr=0.3,0.1

Type RM Length L Ch R = 1,202,0,0,0
BEGIN DESCRIPTION:
Clear Fork Trib13 1.0
END DESCRIPTION:
XS GIS Cut Line= 3
      1466330.02      6924812.96      1466378.73      6924711.12
      1466447.74      6924557.07
#Sta/Elev= 30
  4887.1 1771.12  4925.9 1770.14  4932.4 1769.01  4937.9 1768.86  4948.0 1766.98
  4955.1 1765.22  4960.6 1764.47  4970.2 1763.35  4977.8 1763.75  4992.4 1761.13
  4999.0 1760.67  5003.8 1757.17  5004.1 1756.67  5007.8 1756.67  5008.1 1757.17
  5014.4 1758.48  5023.7 1759.33  5029.2 1764.89  5036.3 1764.64  5046.9 1765.29
  5052.4 1767.16  5069.2 1765.24  5075.6 1766.37  5081.0 1767.77  5091.1 1768.45
  5104.2 1769.08  5134.9 1769.89  5145.1 1769.84  5150.6 1770.35  5168.8 1770.40
#Mann=3,-1,0
  4887.1    0.07       0  5003.8    0.07       0  5008.1    0.07       0
Bank Sta=5003.8,5008.1
Exp/Cntr=0.3,0.1

Chan Stop Cuts=-1