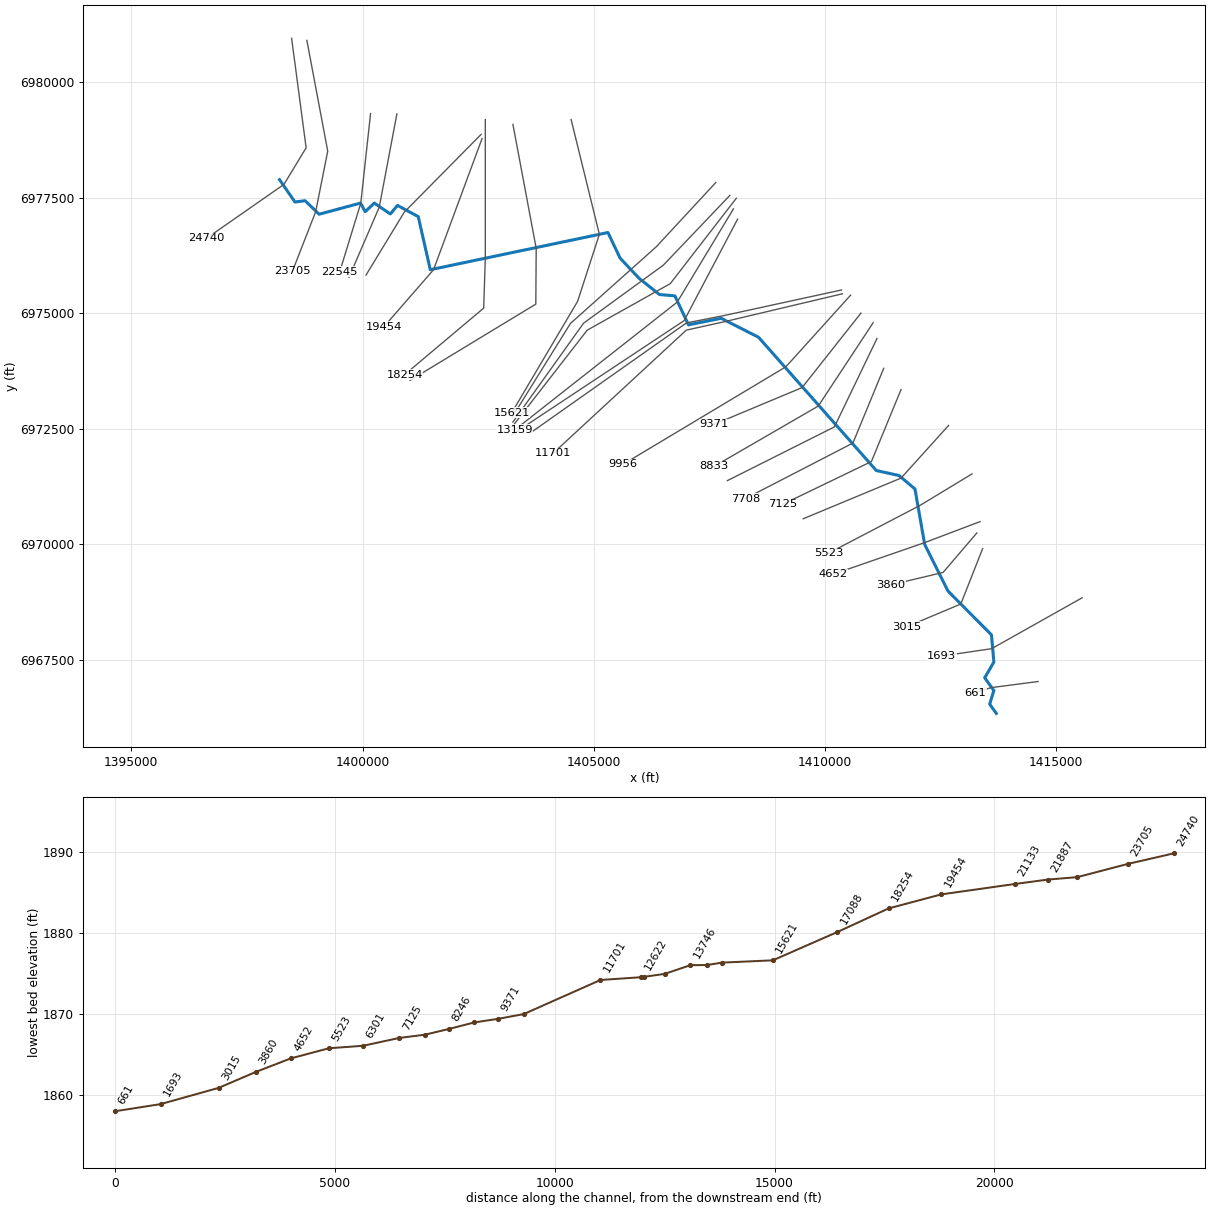
--- Clear Fork Trib2.prj (project) ---

Proj Title=Clear Fork Trib2 Base Level Engineering
Current Plan=p01
Default Exp/Contr=0.3,0.1
English Units
Geom File=g01
Flow File=f01
Plan File=p01
Y Axis Title=Elevation
X Axis Title(PF)=Main Channel Distance
X Axis Title(XS)=Station
BEGIN DESCRIPTION:
Clear Fork Trib2
END DESCRIPTION:
DSS Export Rating Curves= 0
DSS Export Rating Curve Sorted= 0
DSS Export Volume Flow Curves= 0
DXF OffsetX= 0
DXF OffsetY= 0
DXF ScaleX= 1
DXF ScaleY= 10

--- Clear Fork Trib2.p01 (plan) ---

Plan Title=Multiple Run
Short Identifier=Multiple
Geom File=g01
Flow File=f01
Subcritical Flow
K Sum by GR= 0
Std Step Tol= 0.01
Critical Tol= 0.01
Num of Std Step Trials= 20
Max Error Tol= 0.3
Flow Tol Ratio= 0.001
Split Flow NTrial= 30
Split Flow Tol= 0.02
Split Flow Ratio= 0.02
Log Output Level= 0
Friction Slope Method= 1
Unsteady Friction Slope Method= 2
Unsteady Bridges Friction Slope Method= 1
Parabolic Critical Depth
Global Vel Dist=  1 , 1 , 1
Global Log Level= 0
CheckData=True
Encroach Param= -1, 0, 0, 0
BEGIN DESCRIPTION:
Multiple Run
END DESCRIPTION:

--- Clear Fork Trib2.f01 (steady flow) ---

Flow Title=Multiple
Program Version=4.10
Number of Profiles= 7
Profile Names=10-year,25-year,50-year,1pct_min,100-year,1pct_plu,500-year
River Rch & RM=Clear Fork Trib2,Reach-1         ,24740
     263     368     455     280     558    1114     852
River Rch & RM=Clear Fork Trib2,Reach-1         ,23705
     491     710     899     565    1126    2247    1792
River Rch & RM=Clear Fork Trib2,Reach-1         ,22545
     485     700     885     555    1107    2208    1755
River Rch & RM=Clear Fork Trib2,Reach-1         ,19454
     826    1220    1564     993    1982    3955    3226
River Rch & RM=Clear Fork Trib2,Reach-1         ,14468
     854    1260    1614    1023    2042    4074    3314
River Rch & RM=Clear Fork Trib2,Reach-1         ,12622
    1398    2102    2727    1750    3491    6965    5800
River Rch & RM=Clear Fork Trib2,Reach-1         ,8833
    1449    2179    2827    1814    3620    7222    6013
River Rch & RM=Clear Fork Trib2,Reach-1         ,6301
    1684    2541    3304    2124    4237    8454    7062
River Rch & RM=Clear Fork Trib2,Reach-1         ,1693
    1798    2718    3538    2277    4542    9063    7587
Boundary for River Rch & Prof#=Clear Fork Trib2,Reach-1         , 1
Up Type= 0
Dn Type= 3
Dn Slope=0.00107
Boundary for River Rch & Prof#=Clear Fork Trib2,Reach-1         , 2
Up Type= 0
Dn Type= 3
Dn Slope=0.00107
Boundary for River Rch & Prof#=Clear Fork Trib2,Reach-1         , 3
Up Type= 0
Dn Type= 3
Dn Slope=0.00107
Boundary for River Rch & Prof#=Clear Fork Trib2,Reach-1         , 4
Up Type= 0
Dn Type= 3
Dn Slope=0.00107
Boundary for River Rch & Prof#=Clear Fork Trib2,Reach-1         , 5
Up Type= 0
Dn Type= 3
Dn Slope=0.00107
Boundary for River Rch & Prof#=Clear Fork Trib2,Reach-1         , 6
Up Type= 0
Dn Type= 3
Dn Slope=0.00107
Boundary for River Rch & Prof#=Clear Fork Trib2,Reach-1         , 7
Up Type= 0
Dn Type= 3
Dn Slope=0.00107
DSS Import GetInterval= 0
DSS Import GetPeak= 0
DSS Import FillOption= 0

--- Clear Fork Trib2.g01 (geometry) ---

Geom Title=Existing Conditions

River Reach=Clear Fork Trib2,Reach-1
Reach XY= 30
      1398205.00      6977888.00      1398538.29      6977404.29
      1398757.45      6977432.55      1399060.85      6977140.06
      1399955.24      6977381.01      1400058.03      6977195.75
      1400254.78      6977381.01      1400601.68      6977145.60
      1400754.79      6977331.02      1401205.00      6977088.00
      1401465.26      6975938.98      1405307.33      6976743.75
      1405569.17      6976190.60      1405981.50      6975752.23
      1406419.87      6975402.84      1406754.84      6975372.94
      1407048.81      6974745.75      1407755.00      6974888.00
      1408564.68      6974477.24      1411110.61      6971593.59
      1411603.64      6971484.71      1411946.86      6971194.06
      1412157.24      6969993.93      1412660.47      6968985.55
      1413601.46      6968036.54      1413653.78      6967448.50
      1413454.78      6967108.06      1413652.86      6966832.03
      1413562.31      6966537.90      1413705.00      6966338.00

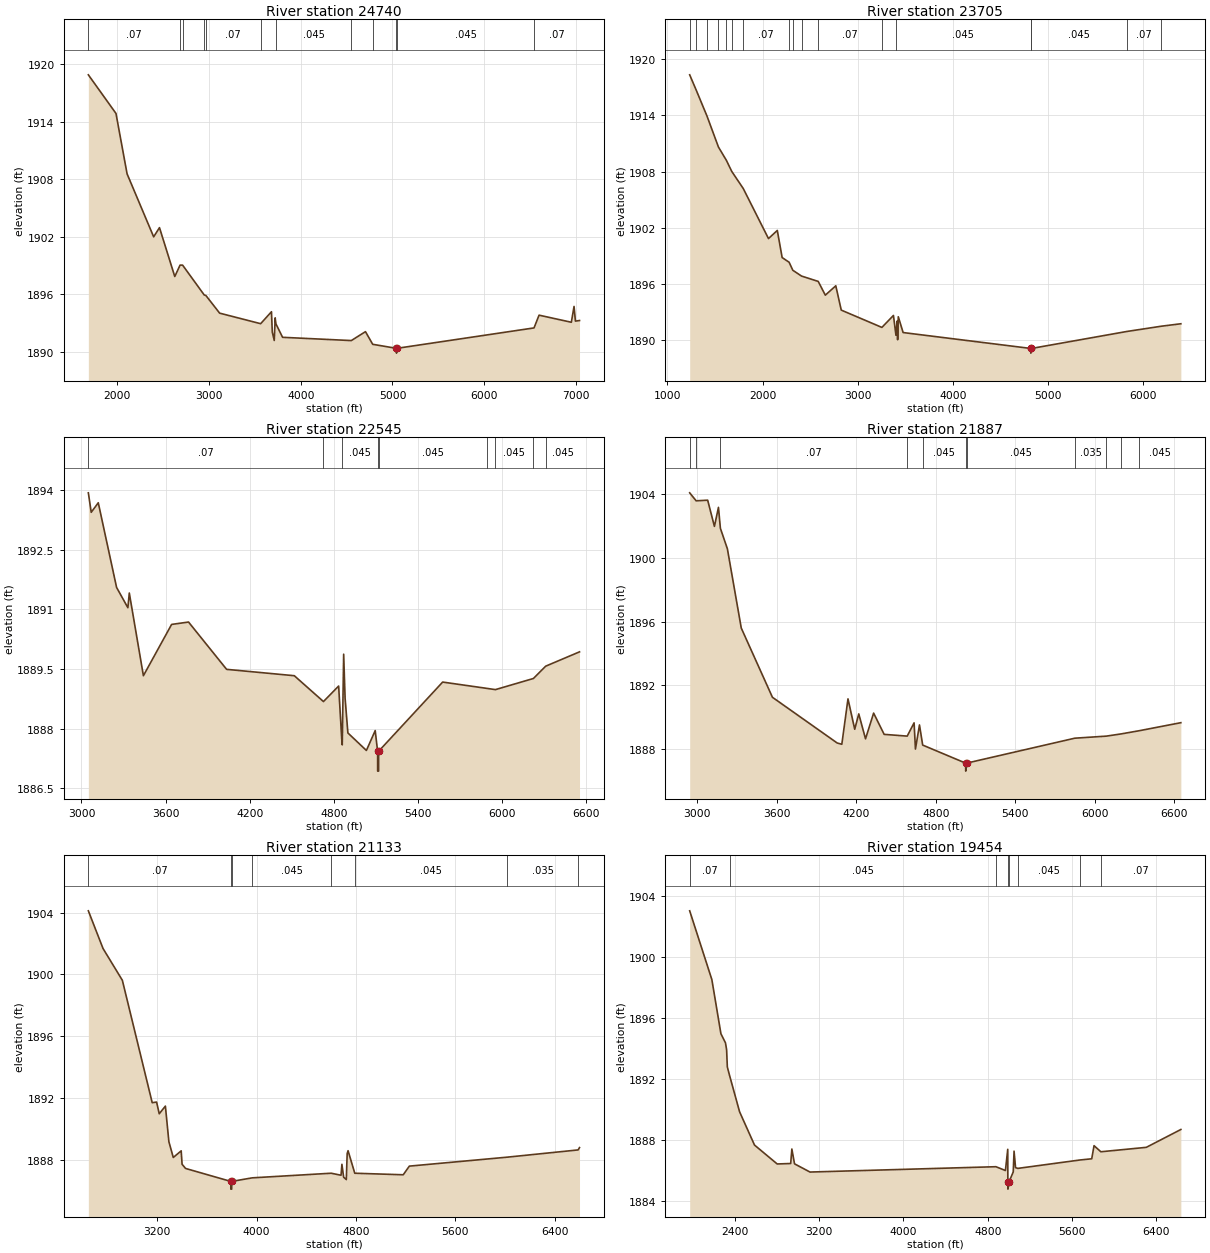
Type RM Length L Ch R = 1,24740,1035,1035,1035
BEGIN DESCRIPTION:
Clear Fork Trib2 28.0
END DESCRIPTION:
XS GIS Cut Line= 4
      1398466.28      6980946.58      1398780.09      6978577.30
      1398301.47      6977786.54      1396629.06      6976620.45
#Sta/Elev= 30
  1685.7 1918.90  1986.9 1914.87  2107.9 1908.57  2397.5 1902.00  2461.0 1902.96
  2627.7 1897.86  2685.4 1899.05  2712.9 1899.05  2948.4 1895.94  2966.9 1895.88
  3116.7 1894.04  3563.7 1892.94  3681.6 1894.19  3690.4 1892.07  3711.8 1891.19
  3721.9 1893.55  3729.7 1892.93  3802.6 1891.52  4551.5 1891.18  4706.1 1892.11
  4784.9 1890.79  5043.8 1890.37  5044.0 1889.87  5048.0 1890.37  6543.1 1892.50
  6598.0 1893.83  6949.6 1893.09  6979.3 1894.74  6994.1 1893.21  7038.8 1893.27
#Mann=12,-1,0
  1685.7    0.07       0  2685.4   0.035       0  2712.9    0.07       0
  2948.4   0.035       0  2966.9    0.07       0  3563.7   0.035       0
  3729.7   0.045       0  4551.5   0.035       0  4784.9   0.045       0
  5043.8   0.045       0  5048.0   0.045       0  6543.1    0.07       0
Bank Sta=5043.8,5048
Exp/Cntr=0.3,0.1

Type RM Length L Ch R = 1,23705,1160,1160,1160
BEGIN DESCRIPTION:
Mapping XS 4395d83d
END DESCRIPTION:
XS GIS Cut Line= 4
      1398796.13      6980903.21      1399247.28      6978505.61
      1398986.10      6977193.31      1398482.72      6975902.08
#Sta/Elev= 30
  1233.7 1918.34  1303.4 1916.68  1416.4 1913.91  1536.0 1910.62  1619.8 1909.19
  1676.0 1908.01  1797.0 1906.18  2062.0 1900.83  2154.8 1901.70  2205.7 1898.80
  2278.9 1898.30  2318.0 1897.44  2409.5 1896.82  2584.8 1896.25  2659.6 1894.78
  2769.6 1895.78  2827.2 1893.18  3254.2 1891.33  3375.9 1892.61  3402.0 1890.49
  3414.6 1892.01  3419.7 1890.01  3426.7 1892.47  3477.6 1890.78  4819.5 1889.08
  4820.0 1888.58  4826.8 1889.08  5826.5 1890.89  6193.4 1891.46  6397.3 1891.72
#Mann=17,-1,0
  1233.7    0.07       0  1303.4   0.035       0  1416.4    0.07       0
  1536.0   0.035       0  1619.8    0.07       0  1676.0   0.035       0
  1797.0    0.07       0  2278.9   0.035       0  2318.0    0.07       0
  2409.5   0.035       0  2584.8    0.07       0  3254.2   0.035       0
  3402.0   0.045       0  4819.5   0.045       0  4826.8   0.045       0
  5826.5    0.07       0  6193.4   0.045       0
Bank Sta=4819.5,4826.8
Exp/Cntr=0.3,0.1

Type RM Length L Ch R = 1,22545,658,658,658
BEGIN DESCRIPTION:
Clear Fork Trib2 27.0
END DESCRIPTION:
XS GIS Cut Line= 3
      1400173.60      6979318.35      1399961.99      6977379.17
      1399506.92      6975894.65
#Sta/Elev= 30
  3049.3 1893.93  3069.8 1893.44  3120.1 1893.68  3250.8 1891.55  3331.3 1891.04
  3341.4 1891.41  3442.0 1889.33  3643.2 1890.62  3763.9 1890.68  4035.5 1889.49
  4518.3 1889.33  4726.3 1888.68  4834.6 1889.07  4856.6 1887.74  4860.3 1887.59
  4870.4 1889.87  4880.5 1888.77  4900.6 1887.89  5032.6 1887.45  5095.4 1887.95
  5112.5 1887.43  5113.0 1886.93  5119.5 1886.93  5120.0 1887.43  5576.5 1889.17
  5894.5 1889.01  5952.6 1888.98  6223.8 1889.26  6311.5 1889.57  6552.7 1889.93
#Mann=9,-1,0
  3049.3    0.07       0  4726.3   0.035       0  4856.6   0.045       0
  5112.5   0.045       0  5120.0   0.045       0  5894.5   0.035       0
  5952.6   0.045       0  6223.8   0.035       0  6311.5   0.045       0
Bank Sta=5112.5,5120
Exp/Cntr=0.3,0.1

Type RM Length L Ch R = 1,21887,754,754,754
BEGIN DESCRIPTION:
Clear Fork Trib2 26.0
END DESCRIPTION:
XS GIS Cut Line= 3
      1400743.03      6979311.33      1400361.03      6977290.52
      1399708.32      6975776.64
#Sta/Elev= 30
  2943.4 1904.05  2992.2 1903.55  3079.1 1903.59  3130.0 1901.95  3160.5 1903.14
  3175.0 1901.83  3227.8 1900.55  3332.5 1895.59  3567.6 1891.26  4056.1 1888.40
  4091.0 1888.32  4137.5 1891.16  4188.4 1889.26  4218.9 1890.22  4269.8 1888.66
  4330.9 1890.27  4410.3 1888.94  4584.2 1888.83  4636.2 1889.66  4646.4 1888.02
  4676.9 1889.53  4701.0 1888.27  5025.2 1887.14  5025.7 1886.64  5032.7 1887.14
  5848.5 1888.70  6086.8 1888.83  6199.5 1888.97  6336.1 1889.17  6648.6 1889.67
#Mann=11,-1,0
  2943.4    0.07       0  2992.2   0.035       0  3175.0    0.07       0
  4584.2   0.035       0  4701.0   0.045       0  5025.2   0.045       0
  5032.7   0.045       0  5848.5   0.035       0  6086.8   0.045       0
  6199.5   0.035       0  6336.1   0.045       0
Bank Sta=5025.2,5032.7
Exp/Cntr=0.3,0.1

Type RM Length L Ch R = 1,21133,1679,1679,1679
BEGIN DESCRIPTION:
Clear Fork Trib2 25.0
END DESCRIPTION:
XS GIS Cut Line= 3
      1402563.49      6978866.70      1400905.00      6977188.00
      1400076.37      6975825.25
#Sta/Elev= 30
  2645.0 1904.12  2763.2 1901.68  2918.8 1899.62  3159.2 1891.69  3194.5 1891.73
  3215.8 1890.97  3265.3 1891.47  3293.5 1889.16  3328.9 1888.14  3392.5 1888.57
  3399.7 1887.70  3427.9 1887.43  3791.9 1886.59  3792.4 1886.09  3799.0 1886.09
  3799.5 1886.59  3963.8 1886.82  4600.2 1887.12  4679.6 1886.99  4686.6 1887.70
  4700.7 1886.86  4722.0 1886.71  4729.0 1888.39  4736.1 1888.58  4790.2 1887.12
  5180.3 1887.02  5229.6 1887.58  6016.9 1888.16  6588.5 1888.63  6599.7 1888.78
#Mann=8,-1,0
  2645.0    0.07       0  3791.9   0.045       0  3799.5    0.07       0
  3963.8   0.045       0  4600.2   0.035       0  4790.2   0.045       0
  6016.9   0.035       0  6588.5   0.045       0
Bank Sta=3791.9,3799.5
Exp/Cntr=0.3,0.1

Type RM Length L Ch R = 1,19454,1200,1200,1200
BEGIN DESCRIPTION:
Clear Fork Trib2 24.0
END DESCRIPTION:
XS GIS Cut Line= 3
      1402584.33      6978776.43      1401534.93      6975937.79
      1400463.56      6974707.23
#Sta/Elev= 30
  1973.6 1903.05  2183.9 1898.54  2269.8 1894.99  2313.1 1894.39  2323.8 1893.94
  2330.6 1892.81  2353.6 1892.21  2446.9 1889.87  2588.3 1887.69  2803.5 1886.45
  2931.5 1886.48  2942.6 1887.43  2967.7 1886.46  3114.4 1885.92  4878.1 1886.27
  4967.8 1886.02  4989.9 1887.41  4990.9 1885.30  4991.4 1884.80  5003.6 1885.30
  5042.0 1885.93  5049.7 1887.29  5063.9 1886.21  5085.6 1886.16  5674.1 1886.71
  5786.4 1886.79  5808.3 1887.65  5873.0 1887.25  6303.9 1887.54  6631.6 1888.71
#Mann=8,-1,0
  1973.6    0.07       0  2353.6   0.045       0  4878.1   0.035       0
  4990.9   0.035       0  5003.6   0.035       0  5085.6   0.045       0
  5674.1   0.035       0  5873.0    0.07       0
Bank Sta=4990.9,5003.6
Exp/Cntr=0.3,0.1

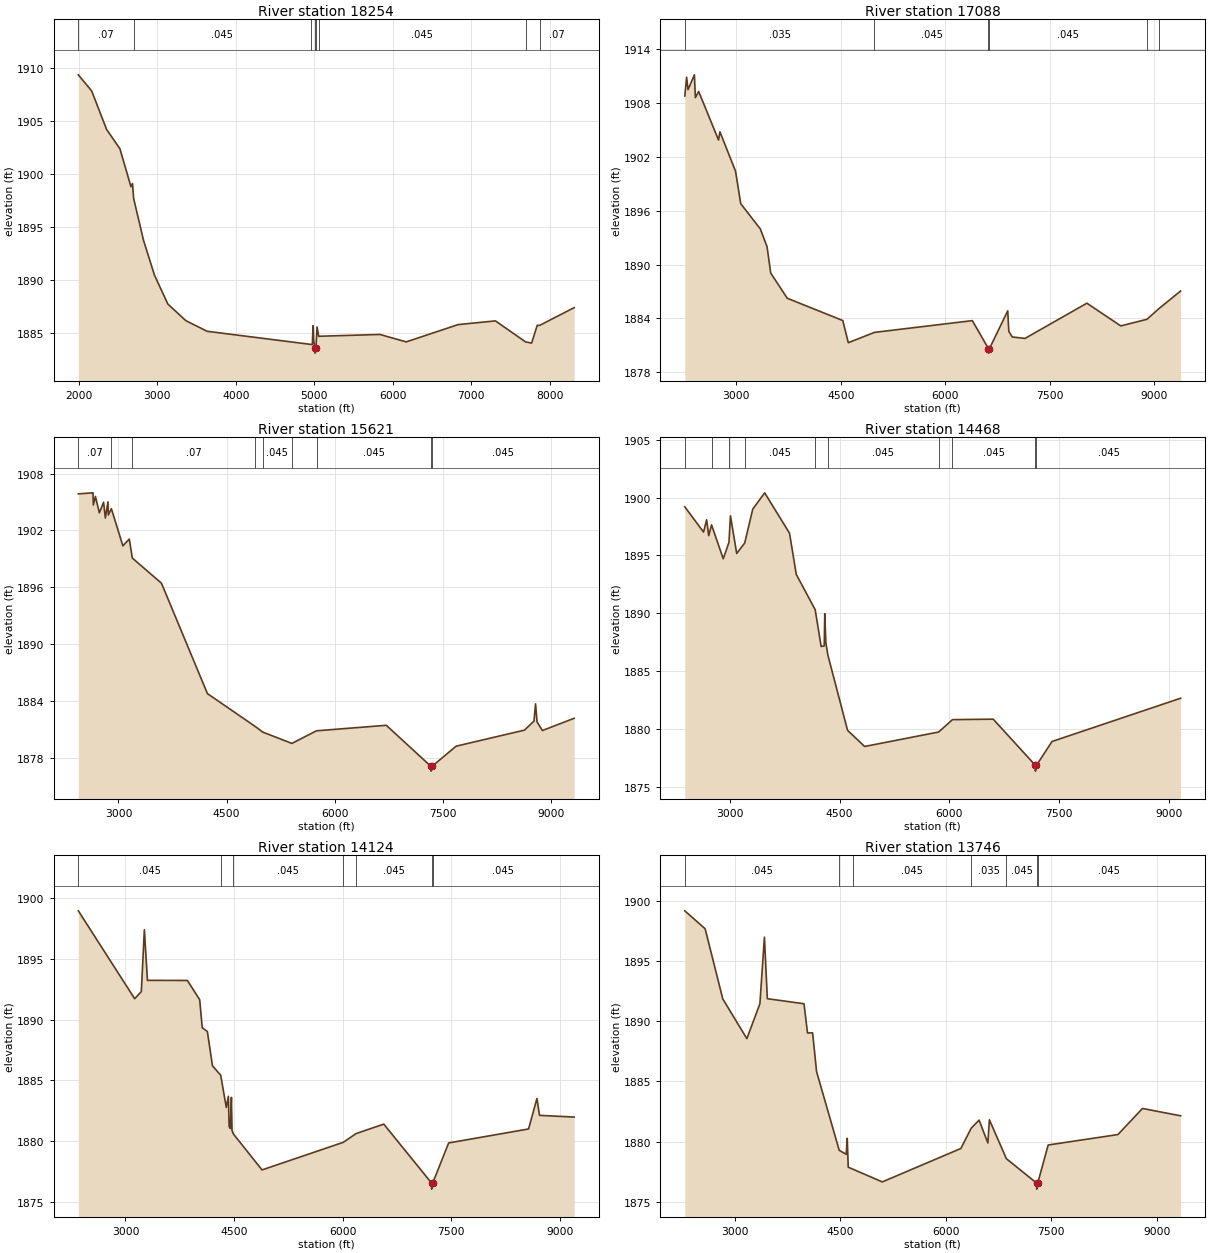
Type RM Length L Ch R = 1,18254,1166,1166,1166
BEGIN DESCRIPTION:
Clear Fork Trib2 23.0
END DESCRIPTION:
XS GIS Cut Line= 4
      1402655.00      6979188.04      1402655.00      6976188.00
      1402620.18      6975108.10      1400910.81      6973669.15
#Sta/Elev= 30
  1995.3 1909.31  2165.3 1907.79  2355.3 1904.16  2525.3 1902.33  2665.3 1898.76
  2685.3 1899.06  2700.1 1897.64  2825.3 1893.71  2965.3 1890.41  3135.3 1887.69
  3365.3 1886.12  3635.3 1885.12  4958.9 1883.88  4975.3 1883.87  4985.3 1885.64
  4992.8 1884.24  5008.9 1883.56  5009.4 1883.06  5021.8 1883.56  5035.4 1885.52
  5056.9 1884.65  5835.8 1884.82  6172.2 1884.12  6831.6 1885.75  7307.6 1886.10
  7691.3 1884.12  7768.8 1884.01  7839.5 1885.68  7871.6 1885.68  8310.2 1887.35
#Mann=8,-1,0
  1995.3    0.07       0  2700.1   0.045       0  4958.9   0.035       0
  5008.9   0.035       0  5021.8   0.035       0  5056.9   0.045       0
  7691.3   0.035       0  7871.6    0.07       0
Bank Sta=5008.9,5021.8
Exp/Cntr=0.3,0.1

Type RM Length L Ch R = 1,17088,1467,1467,1467
BEGIN DESCRIPTION:
Mapping XS ccdd55ea
END DESCRIPTION:
XS GIS Cut Line= 4
      1403252.34      6979083.60      1403755.81      6976401.32
      1403747.13      6975194.72      1401030.09      6973545.41
#Sta/Elev= 30
  2262.5 1908.78  2288.6 1910.88  2309.0 1909.49  2400.5 1911.14  2414.1 1908.60
  2461.5 1909.29  2746.4 1903.88  2766.8 1904.79  2990.6 1900.41  3064.9 1896.79
  3346.7 1893.97  3442.9 1891.99  3495.4 1889.06  3733.3 1886.25  4529.3 1883.77
  4608.4 1881.30  4983.6 1882.45  6387.9 1883.76  6619.9 1880.64  6620.4 1880.14
  6633.3 1880.64  6896.1 1884.85  6911.5 1882.56  6961.1 1881.94  7144.2 1881.78
  8031.9 1885.70  8518.5 1883.17  8894.2 1883.91  9062.7 1885.08  9376.7 1887.06
#Mann=6,-1,0
  2262.5   0.035       0  4983.6   0.045       0  6619.9   0.045       0
  6633.3   0.045       0  8894.2   0.035       0  9062.7    0.07       0
Bank Sta=6619.9,6633.3
Exp/Cntr=0.3,0.1

Type RM Length L Ch R = 1,15621,1153,1153,1153
BEGIN DESCRIPTION:
Clear Fork Trib2 21.0
END DESCRIPTION:
XS GIS Cut Line= 4
      1404510.84      6979188.51      1405121.57      6976704.89
      1404651.48      6975254.98      1403226.50      6972842.64
#Sta/Elev= 30
  2442.4 1905.86  2646.0 1905.97  2651.1 1904.69  2679.8 1905.59  2734.2 1903.86
  2793.0 1904.98  2817.3 1903.31  2853.7 1905.02  2858.8 1903.63  2901.1 1904.30
  3060.8 1900.38  3149.6 1901.10  3192.3 1899.09  3596.3 1896.45  4234.6 1884.81
  4901.4 1881.33  5003.7 1880.75  5407.1 1879.56  5749.4 1880.89  6718.1 1881.47
  7338.2 1877.14  7338.7 1876.64  7352.4 1877.14  7687.6 1879.27  8635.6 1880.96
  8768.3 1881.91  8789.8 1883.73  8811.2 1881.82  8885.4 1880.92  9326.0 1882.21
#Mann=9,-1,0
  2442.4    0.07       0  2901.1   0.035       0  3192.3    0.07       0
  4901.4   0.035       0  5003.7   0.045       0  5407.1   0.035       0
  5749.4   0.045       0  7338.2   0.035       0  7352.4   0.045       0
Bank Sta=7338.2,7352.4
Exp/Cntr=0.3,0.1

Type RM Length L Ch R = 1,14468,344,344,344
BEGIN DESCRIPTION:
Clear Fork Trib2 20.0
END DESCRIPTION:
XS GIS Cut Line= 4
      1407639.22      6977825.82      1406355.00      6976438.00
      1404496.22      6974776.08      1403234.99      6972746.83
#Sta/Elev= 30
  2384.1 1899.20  2640.0 1897.02  2682.6 1898.08  2710.9 1896.71  2749.7 1897.64
  2909.3 1894.71  2987.3 1896.13  3008.0 1898.42  3093.1 1895.17  3202.3 1896.07
  3312.5 1899.00  3475.2 1900.41  3814.8 1896.92  3907.1 1893.36  4165.5 1890.31
  4246.9 1887.13  4288.7 1887.18  4296.3 1889.97  4310.5 1887.50  4338.6 1886.39
  4608.0 1879.88  4841.3 1878.49  5851.9 1879.74  6040.9 1880.81  6597.6 1880.85
  7173.5 1876.86  7174.0 1876.36  7188.5 1876.86  7400.6 1878.92  9157.6 1882.66
#Mann=10,-1,0
  2384.1    0.05       0  2749.7   0.045       0  2987.3    0.07       0
  3202.3   0.045       0  4165.5   0.035       0  4338.6   0.045       0
  5851.9   0.035       0  6040.9   0.045       0  7173.5   0.045       0
  7188.5   0.045       0
Bank Sta=7173.5,7188.5
Exp/Cntr=0.3,0.1

Type RM Length L Ch R = 1,14124,378,378,378
BEGIN DESCRIPTION:
Clear Fork Trib2 19.0
END DESCRIPTION:
XS GIS Cut Line= 4
      1407944.79      6977548.05      1406505.00      6976038.00
      1404780.94      6974783.03      1403252.44      6972642.79
#Sta/Elev= 30
  2349.2 1898.96  3127.1 1891.73  3219.2 1892.31  3261.4 1897.41  3303.8 1893.24
  3855.5 1893.23  4025.3 1891.65  4060.9 1889.34  4131.7 1889.03  4202.1 1886.21
  4315.8 1885.43  4393.3 1882.78  4421.7 1883.70  4432.2 1881.22  4449.2 1881.05
  4463.8 1883.61  4472.3 1880.89  4491.0 1880.60  4886.5 1877.64  6008.4 1879.91
  6186.1 1880.63  6568.1 1881.41  7228.7 1876.56  7229.2 1876.06  7243.7 1876.56
  7464.8 1879.86  8568.4 1881.01  8683.9 1883.52  8719.6 1882.13  9198.1 1881.99
#Mann=7,-1,0
  2349.2   0.045       0  4315.8   0.035       0  4491.0   0.045       0
  6008.4   0.035       0  6186.1   0.045       0  7228.7   0.045       0
  7243.7   0.045       0
Bank Sta=7228.7,7243.7
Exp/Cntr=0.3,0.1

Type RM Length L Ch R = 1,13746,587,587,587
BEGIN DESCRIPTION:
Clear Fork Trib2 18.0
END DESCRIPTION:
XS GIS Cut Line= 4
      1408083.66      6977485.54      1406655.00      6975638.00
      1404858.24      6974630.49      1403234.95      6972538.45
#Sta/Elev= 30
  2293.2 1899.19  2582.1 1897.70  2833.0 1891.86  3175.0 1888.56  3360.0 1891.46
  3424.3 1897.00  3465.9 1891.88  3986.6 1891.46  4036.4 1889.03  4108.9 1889.04
  4165.0 1885.82  4486.8 1879.27  4586.1 1878.94  4600.6 1880.27  4615.1 1877.86
  4676.6 1877.71  5098.7 1876.64  6214.9 1879.42  6361.8 1881.11  6473.9 1881.78
  6598.3 1879.88  6620.0 1881.81  6861.7 1878.57  7291.8 1876.54  7292.3 1876.04
  7306.8 1876.54  7455.0 1879.71  8446.2 1880.58  8794.6 1882.75  9336.6 1882.14
#Mann=7,-1,0
  2293.2   0.045       0  4486.8   0.035       0  4676.6   0.045       0
  6361.8   0.035       0  6861.7   0.045       0  7291.8   0.045       0
  7306.8   0.045       0
Bank Sta=7291.8,7306.8
Exp/Cntr=0.3,0.1

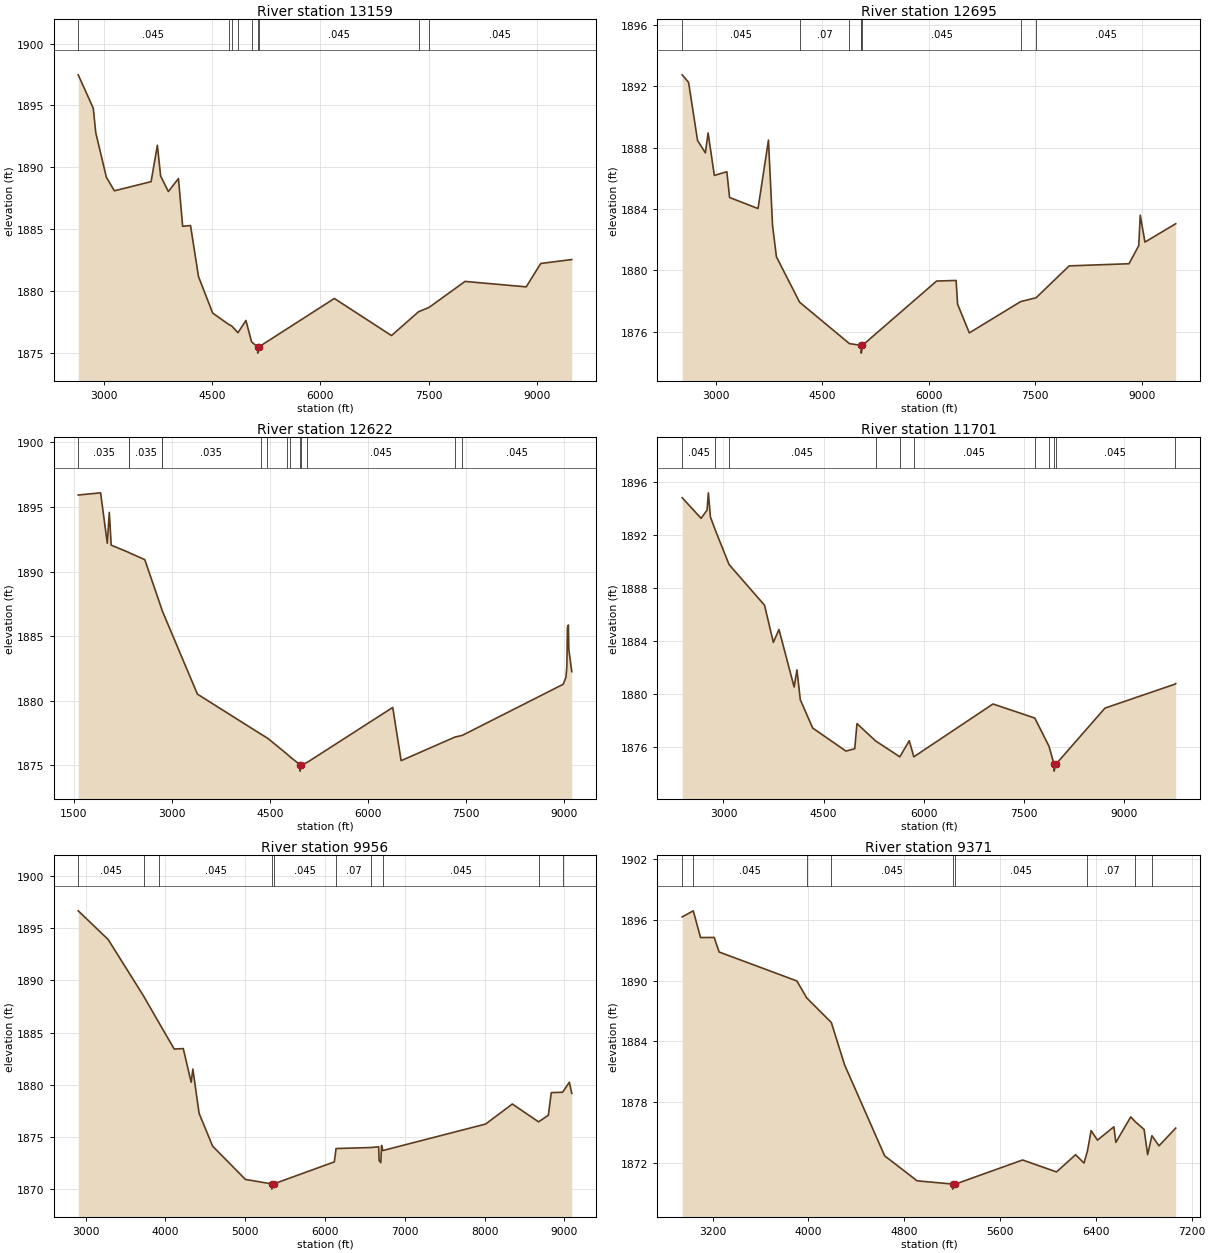
Type RM Length L Ch R = 1,13159,464,464,464
BEGIN DESCRIPTION:
Clear Fork Trib2 17.0
END DESCRIPTION:
XS GIS Cut Line= 3
      1408021.14      6977256.35      1406805.00      6975238.00
      1403288.53      6972470.19
#Sta/Elev= 30
  2649.5 1897.47  2857.7 1894.77  2892.7 1892.78  3039.0 1889.19  3149.6 1888.09
  3658.4 1888.83  3745.0 1891.77  3790.4 1889.28  3897.2 1888.03  4036.9 1889.08
  4095.3 1885.22  4204.0 1885.28  4314.7 1881.15  4510.8 1878.20  4730.1 1877.29
  4775.5 1877.15  4860.6 1876.61  4970.9 1877.60  5049.2 1875.87  5133.9 1875.46
  5134.4 1874.96  5148.9 1875.46  6195.0 1879.38  6985.7 1876.38  7360.9 1878.31
  7505.9 1878.66  8004.0 1880.76  8850.7 1880.32  9051.3 1882.21  9481.0 1882.53
#Mann=9,-1,0
  2649.5   0.045       0  4730.1    0.07       0  4775.5   0.045       0
  4860.6   0.035       0  5049.2   0.045       0  5133.9   0.035       0
  5148.9   0.045       0  7360.9   0.035       0  7505.9   0.045       0
Bank Sta=5133.9,5148.9
Exp/Cntr=0.3,0.1

Type RM Length L Ch R = 1,12695,73,73,73
BEGIN DESCRIPTION:
Clear Fork Trib2 16.0
END DESCRIPTION:
XS GIS Cut Line= 3
      1408111.43      6977034.14      1406955.00      6974838.00
      1403226.33      6972364.89
#Sta/Elev= 30
  2523.9 1892.75  2614.2 1892.26  2740.8 1888.47  2850.9 1887.66  2889.3 1888.96
  2977.5 1886.19  3153.7 1886.43  3192.2 1884.75  3593.2 1884.03  3740.1 1888.49
  3797.8 1882.92  3852.6 1880.88  4179.3 1877.92  4881.3 1875.22  5042.0 1875.11
  5047.8 1875.10  5048.3 1874.60  5063.2 1875.10  6109.9 1879.30  6384.9 1879.34
  6405.9 1877.79  6571.4 1875.92  7294.4 1877.96  7511.6 1878.21  7978.9 1880.29
  8821.8 1880.43  8959.4 1881.61  8980.4 1883.60  9046.6 1881.84  9480.2 1883.04
#Mann=8,-1,0
  2523.9   0.045       0  4179.3    0.07       0  4881.3   0.035       0
  5042.0   0.045       0  5047.8   0.035       0  5063.2   0.045       0
  7294.4   0.035       0  7511.6   0.045       0
Bank Sta=5047.8,5063.2
Exp/Cntr=0.3,0.1

Type RM Length L Ch R = 1,12622,921,921,921
BEGIN DESCRIPTION:
Mapping XS ced7ed9c
END DESCRIPTION:
XS GIS Cut Line= 4
      1410359.24      6975501.04      1407802.44      6974944.06
      1407004.69      6974787.66      1403642.94      6972416.93
#Sta/Elev= 30
  1570.3 1895.92  1912.4 1896.09  2014.7 1892.19  2045.4 1894.58  2074.4 1892.04
  2343.0 1891.48  2346.4 1891.46  2587.9 1890.92  2850.1 1887.04  2852.2 1886.99
  3392.3 1880.51  4360.5 1877.42  4462.2 1877.11  4761.9 1875.87  4814.6 1875.63
  4960.4 1875.05  4960.9 1874.55  4975.8 1875.05  5065.1 1875.21  6377.5 1879.48
  6505.6 1875.36  7325.2 1877.18  7441.3 1877.32  8982.1 1881.27  9025.4 1881.82
  9038.7 1882.64  9047.4 1885.63  9062.1 1885.86  9068.3 1884.00  9113.6 1882.25
#Mann=14,-1,0
  1570.3   0.035       0  2343.0   0.045       0  2346.4   0.035       0
  2850.1    0.05       0  2852.2   0.035       0  4360.5    0.07       0
  4462.2   0.035       0  4761.9    0.07       0  4814.6   0.035       0
  4960.4   0.035       0  4975.8   0.035       0  5065.1   0.045       0
  7325.2   0.035       0  7441.3   0.045       0
Bank Sta=4960.4,4975.8
Exp/Cntr=0.3,0.1

Type RM Length L Ch R = 1,11701,1745,1745,1745
BEGIN DESCRIPTION:
Clear Fork Trib2 15.0
END DESCRIPTION:
XS GIS Cut Line= 4
      1410376.59      6975418.22      1407828.31      6974814.60
      1407001.61      6974631.77      1404120.42      6971965.59
#Sta/Elev= 30
  2381.2 1894.81  2664.8 1893.26  2754.4 1893.88  2773.4 1895.18  2804.2 1893.36
  2879.4 1892.35  3083.1 1889.78  3614.8 1886.71  3746.7 1883.91  3831.1 1884.88
  4057.9 1880.55  4100.0 1881.84  4150.4 1879.59  4335.4 1877.46  4833.6 1875.72
  4965.5 1875.90  4999.1 1877.79  5277.3 1876.49  5640.7 1875.29  5781.8 1876.50
  5850.5 1875.29  7035.8 1879.27  7662.0 1878.21  7875.0 1876.08  7951.3 1874.71
  7951.8 1874.21  7974.4 1874.71  8713.0 1878.96  9759.9 1880.76  9772.2 1880.81
#Mann=11,-1,0
  2381.2   0.045       0  2879.4   0.035       0  3083.1   0.045       0
  5277.3    0.07       0  5640.7   0.035       0  5850.5   0.045       0
  7662.0   0.035       0  7875.0   0.045       0  7951.3   0.045       0
  7974.4   0.045       0  9759.9    0.07       0
Bank Sta=7951.3,7974.4
Exp/Cntr=0.3,0.1

Type RM Length L Ch R = 1,9956,585,585,585
BEGIN DESCRIPTION:
Clear Fork Trib2 14.0
END DESCRIPTION:
XS GIS Cut Line= 3
      1410555.03      6975388.03      1409155.00      6973838.00
      1405639.47      6971731.17
#Sta/Elev= 30
  2906.7 1896.67  3282.2 1893.92  3727.2 1888.49  3922.9 1885.89  4110.2 1883.42
  4223.8 1883.46  4322.5 1880.24  4344.1 1881.50  4421.9 1877.26  4591.5 1874.11
  5003.2 1870.92  5333.5 1870.49  5334.0 1869.99  5356.8 1870.49  6117.2 1872.60
  6139.2 1873.88  6575.1 1873.98  6673.2 1874.05  6679.1 1872.72  6700.5 1872.53
  6709.2 1874.18  6725.9 1873.69  8014.7 1876.23  8349.1 1878.15  8677.9 1876.44
  8800.2 1877.07  8837.1 1879.24  8979.4 1879.28  9064.1 1880.24  9093.9 1879.17
#Mann=10,-1,0
  2906.7   0.045       0  3727.2   0.035       0  3922.9   0.045       0
  5333.5   0.045       0  5356.8   0.045       0  6139.2    0.07       0
  6575.1   0.035       0  6725.9   0.045       0  8677.9    0.07       0
  8979.4   0.035       0
Bank Sta=5333.5,5356.8
Exp/Cntr=0.3,0.1

Type RM Length L Ch R = 1,9371,538,538,538
BEGIN DESCRIPTION:
Clear Fork Trib2 13.0
END DESCRIPTION:
XS GIS Cut Line= 3
      1410778.07      6974999.38      1409505.00      6973388.00
      1407598.81      6972590.22
#Sta/Elev= 30
  2946.4 1896.30  3039.2 1896.90  3099.7 1894.26  3213.5 1894.27  3255.1 1892.83
  3904.0 1889.97  3985.9 1888.30  4191.8 1885.86  4301.9 1881.69  4636.9 1872.69
  4907.8 1870.22  5204.0 1869.90  5204.5 1869.40  5227.5 1869.90  5788.0 1872.28
  6071.3 1871.10  6230.4 1872.80  6300.9 1871.98  6329.4 1873.16  6360.2 1875.18
  6413.2 1874.24  6550.2 1875.56  6566.7 1874.02  6691.1 1876.54  6728.9 1876.06
  6802.6 1875.30  6832.0 1872.81  6867.7 1874.68  6926.9 1873.68  7066.4 1875.43
#Mann=9,-1,0
  2946.4    0.07       0  3039.2   0.045       0  3985.9   0.035       0
  4191.8   0.045       0  5204.0   0.045       0  5227.5   0.045       0
  6329.4    0.07       0  6728.9   0.035       0  6867.7   0.045       0
Bank Sta=5204,5227.5
Exp/Cntr=0.3,0.1

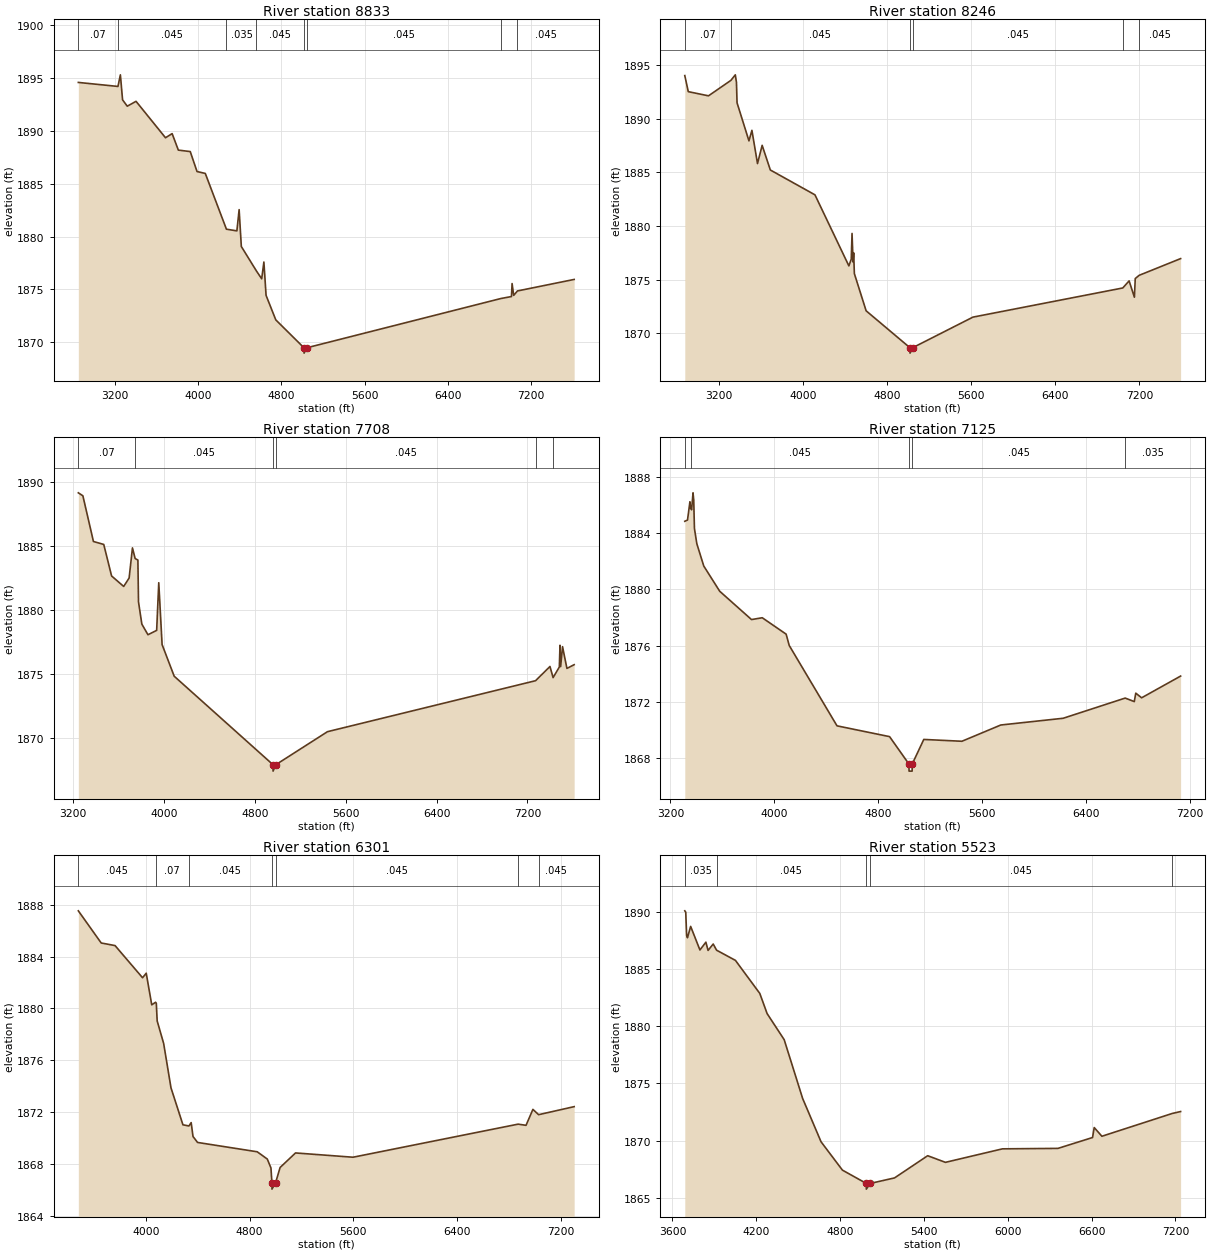
Type RM Length L Ch R = 1,8833,587,587,587
BEGIN DESCRIPTION:
Clear Fork Trib2 12.0
END DESCRIPTION:
XS GIS Cut Line= 3
      1411042.00      6974791.11      1409855.00      6972988.00
      1407598.74      6971680.66
#Sta/Elev= 30
  2847.0 1894.60  3227.9 1894.22  3251.3 1895.32  3272.3 1892.95  3317.6 1892.35
  3401.8 1892.81  3685.0 1889.36  3748.7 1889.75  3808.5 1888.19  3922.9 1888.05
  3988.1 1886.16  4067.5 1885.98  4270.6 1880.70  4371.2 1880.54  4392.8 1882.55
  4413.9 1879.06  4559.3 1876.74  4609.7 1876.00  4630.8 1877.59  4651.8 1874.43
  4745.2 1872.11  5016.7 1869.46  5017.2 1868.96  5041.1 1869.46  6908.2 1874.13
  7010.7 1874.32  7016.7 1875.55  7032.2 1874.43  7068.4 1874.85  7613.4 1875.94
#Mann=8,-1,0
  2847.0    0.07       0  3227.9   0.045       0  4270.6   0.035       0
  4559.3   0.045       0  5016.7   0.045       0  5041.1   0.045       0
  6908.2   0.035       0  7068.4   0.045       0
Bank Sta=5016.7,5041.1
Exp/Cntr=0.3,0.1

Type RM Length L Ch R = 1,8246,538,538,538
BEGIN DESCRIPTION:
Clear Fork Trib2 11.0
END DESCRIPTION:
XS GIS Cut Line= 3
      1411125.32      6974450.81      1410205.00      6972538.00
      1407889.64      6971374.63
#Sta/Elev= 30
  2877.3 1894.04  2910.4 1892.54  3102.5 1892.15  3315.2 1893.59  3357.6 1894.11
  3368.5 1893.40  3374.1 1891.50  3487.2 1887.95  3515.4 1888.93  3568.5 1885.83
  3612.8 1887.53  3690.5 1885.23  4114.9 1882.91  4437.2 1876.28  4459.9 1876.91
  4467.3 1879.31  4477.0 1876.64  4482.5 1877.50  4489.5 1875.56  4601.2 1872.09
  5018.4 1868.64  5018.9 1868.14  5042.9 1868.64  5616.8 1871.50  7041.2 1874.22
  7101.6 1874.88  7151.8 1873.36  7159.9 1875.10  7197.0 1875.40  7591.2 1876.96
#Mann=6,-1,0
  2877.3    0.07       0  3315.2   0.045       0  5018.4   0.045       0
  5042.9   0.045       0  7041.2   0.035       0  7197.0   0.045       0
Bank Sta=5018.4,5042.9
Exp/Cntr=0.3,0.1

Type RM Length L Ch R = 1,7708,583,583,583
BEGIN DESCRIPTION:
Clear Fork Trib2 10.0
END DESCRIPTION:
XS GIS Cut Line= 3
      1411271.13      6973804.94      1410605.00      6972188.00
      1408279.00      6970985.99
#Sta/Elev= 30
  3245.2 1889.17  3285.2 1888.94  3378.3 1885.37  3469.0 1885.14  3538.1 1882.68
  3644.7 1881.86  3692.6 1882.52  3721.9 1884.87  3745.5 1884.04  3769.8 1883.92
  3775.2 1880.65  3804.6 1878.92  3858.4 1878.09  3935.1 1878.43  3953.6 1882.15
  3983.0 1877.32  4089.6 1874.85  4960.0 1867.94  4960.5 1867.44  4984.6 1867.94
  5439.6 1870.52  7272.2 1874.50  7399.1 1875.61  7426.8 1874.74  7481.6 1875.57
  7487.6 1877.27  7493.3 1875.60  7509.8 1877.16  7548.5 1875.46  7612.2 1875.75
#Mann=6,-1,0
  3245.2    0.07       0  3745.5   0.045       0  4960.0   0.045       0
  4984.6   0.045       0  7272.2   0.035       0  7426.8    0.07       0
Bank Sta=4960,4984.6
Exp/Cntr=0.3,0.1

Type RM Length L Ch R = 1,7125,824,824,824
BEGIN DESCRIPTION:
Clear Fork Trib2 9.0
END DESCRIPTION:
XS GIS Cut Line= 3
      1411646.15      6973346.65      1411005.00      6971788.00
      1409083.62      6970860.51
#Sta/Elev= 30
  3310.3 1884.86  3331.2 1884.95  3349.7 1886.25  3355.1 1885.80  3362.9 1885.68
  3373.7 1886.89  3379.1 1886.37  3384.5 1884.35  3403.0 1883.26  3456.4 1881.67
  3579.2 1879.87  3824.2 1877.85  3906.9 1877.98  4090.8 1876.81  4114.7 1876.00
  4482.6 1870.27  4887.5 1869.50  5037.1 1867.54  5037.6 1867.04  5061.2 1867.04
  5061.7 1867.54  5151.1 1869.30  5444.8 1869.17  5744.2 1870.33  6224.5 1870.81
  6702.2 1872.25  6772.3 1872.00  6783.7 1872.60  6828.9 1872.27  7129.2 1873.82
#Mann=5,-1,0
  3310.3    0.07       0  3355.1   0.045       0  5037.1   0.045       0
  5061.7   0.045       0  6702.2   0.035       0
Bank Sta=5037.1,5061.7
Exp/Cntr=0.3,0.1

Type RM Length L Ch R = 1,6301,778,778,778
BEGIN DESCRIPTION:
Mapping XS bbad2d39
END DESCRIPTION:
XS GIS Cut Line= 3
      1412673.94      6972568.87      1411646.14      6971429.96
      1409529.68      6970549.25
#Sta/Elev= 30
  3477.8 1887.53  3654.3 1885.05  3761.2 1884.85  3973.4 1882.37  4001.8 1882.72
  4044.4 1880.28  4073.9 1880.48  4079.6 1880.40  4086.3 1879.04  4136.3 1877.30
  4192.9 1873.88  4285.1 1871.03  4331.3 1870.94  4348.6 1871.20  4362.8 1870.13
  4397.9 1869.67  4858.3 1868.95  4936.0 1868.39  4964.4 1867.70  4971.7 1866.57
  4972.2 1866.07  5000.3 1866.57  5035.1 1867.74  5153.9 1868.86  5597.6 1868.53
  6871.6 1871.08  6932.9 1870.99  6986.0 1872.22  7030.0 1871.81  7304.3 1872.43
#Mann=7,-1,0
  3477.8   0.045       0  4073.9    0.07       0  4331.3   0.045       0
  4971.7   0.045       0  5000.3   0.045       0  6871.6   0.035       0
  7030.0   0.045       0
Bank Sta=4971.7,5000.3
Exp/Cntr=0.3,0.1

Type RM Length L Ch R = 1,5523,871,871,871
BEGIN DESCRIPTION:
Clear Fork Trib2 8.0
END DESCRIPTION:
XS GIS Cut Line= 3
      1413180.86      6971520.23      1412055.00      6970838.00
      1410076.26      6969804.33
#Sta/Elev= 30
  3688.2 1890.08  3695.0 1889.96  3701.5 1887.91  3707.4 1887.73  3730.1 1888.72
  3796.5 1886.66  3839.2 1887.34  3854.7 1886.62  3891.5 1887.18  3915.7 1886.64
  4050.6 1885.75  4225.1 1882.86  4277.4 1881.10  4399.6 1878.82  4531.5 1873.69
  4663.3 1869.90  4816.5 1867.42  4987.1 1866.26  4987.6 1865.76  5016.3 1866.26
  5189.5 1866.74  5426.8 1868.68  5553.6 1868.10  5961.9 1869.28  6359.3 1869.32
  6606.7 1870.27  6618.6 1871.14  6673.6 1870.38  7176.6 1872.37  7237.1 1872.54
#Mann=5,-1,0
  3688.2   0.035       0  3915.7   0.045       0  4987.1   0.045       0
  5016.3   0.045       0  7176.6   0.035       0
Bank Sta=4987.1,5016.3
Exp/Cntr=0.3,0.1

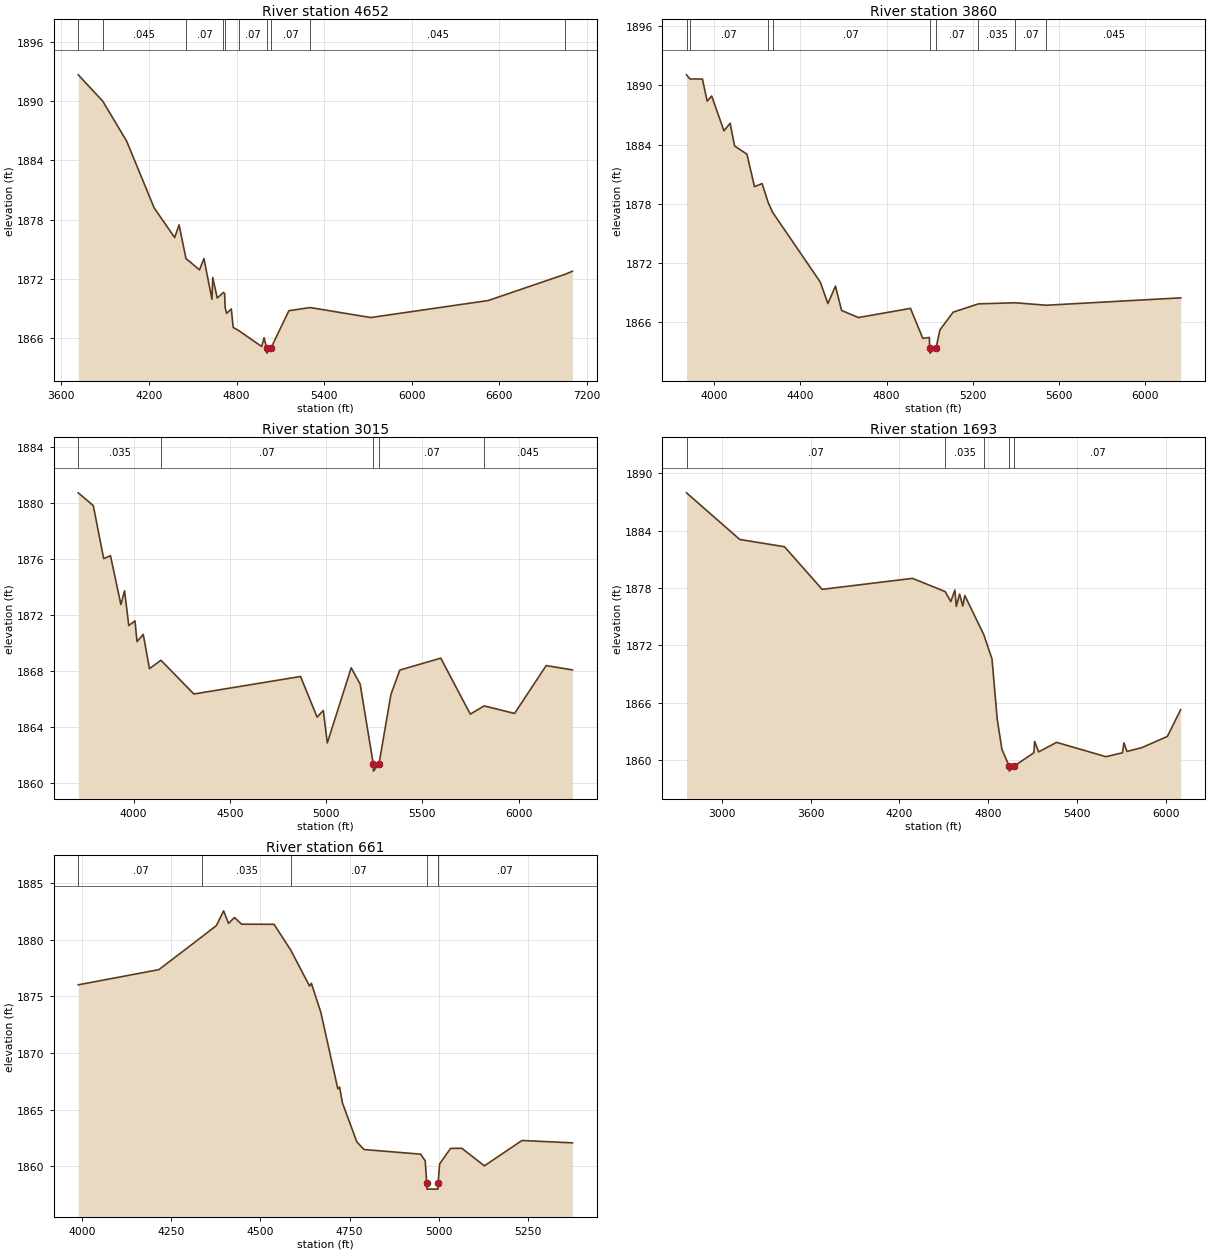
Type RM Length L Ch R = 1,4652,792,792,792
BEGIN DESCRIPTION:
Clear Fork Trib2 6.0
END DESCRIPTION:
XS GIS Cut Line= 3
      1413354.97      6970487.99      1412154.56      6970032.82
      1410170.05      6969346.01
#Sta/Elev= 30
  3716.2 1892.65  3883.9 1889.99  4047.7 1885.94  4236.4 1879.18  4376.4 1876.19
  4406.6 1877.47  4453.8 1874.07  4546.6 1872.92  4576.8 1874.07  4631.7 1869.95
  4637.0 1872.15  4668.0 1870.07  4710.1 1870.64  4718.6 1870.52  4722.1 1869.08
  4732.2 1868.52  4764.2 1868.97  4777.1 1867.10  4816.4 1866.77  4972.0 1865.17
  4988.8 1866.05  5006.1 1865.00  5006.6 1864.50  5035.4 1865.00  5158.3 1868.79
  5304.2 1869.11  5719.1 1868.10  6523.2 1869.82  7047.3 1872.46  7100.0 1872.78
#Mann=10,-1,0
  3716.2   0.035       0  3883.9   0.045       0  4453.8    0.07       0
  4710.1   0.045       0  4718.6   0.035       0  4816.4    0.07       0
  5006.1    0.07       0  5035.4    0.07       0  5304.2   0.045       0
  7047.3   0.035       0
Bank Sta=5006.1,5035.4
Exp/Cntr=0.3,0.1

Type RM Length L Ch R = 1,3860,845,845,845
BEGIN DESCRIPTION:
Clear Fork Trib2 5.0
END DESCRIPTION:
XS GIS Cut Line= 3
      1413285.06      6970242.50      1412555.00      6969388.00
      1411418.48      6969117.82
#Sta/Elev= 30
  3872.1 1891.07  3887.8 1890.65  3945.9 1890.64  3967.9 1888.40  3988.7 1888.92
  4045.8 1885.39  4074.4 1886.16  4095.2 1883.85  4152.3 1883.02  4187.4 1879.72
  4222.6 1880.04  4251.6 1878.07  4271.8 1877.11  4492.6 1870.04  4527.8 1867.86
  4562.9 1869.63  4591.4 1867.16  4669.4 1866.44  4910.9 1867.37  4968.0 1864.33
  4998.6 1864.42  4999.9 1863.33  5000.4 1862.83  5029.2 1863.33  5047.4 1865.19
  5109.1 1866.99  5226.1 1867.83  5396.0 1867.94  5541.3 1867.69  6164.2 1868.44
#Mann=9,-1,0
  3872.1   0.035       0  3887.8    0.07       0  4251.6   0.035       0
  4271.8    0.07       0  4999.9    0.07       0  5029.2    0.07       0
  5226.1   0.035       0  5396.0    0.07       0  5541.3   0.045       0
Bank Sta=4999.9,5029.2
Exp/Cntr=0.3,0.1

Type RM Length L Ch R = 1,3015,1322,1322,1322
BEGIN DESCRIPTION:
Clear Fork Trib2 4.0
END DESCRIPTION:
XS GIS Cut Line= 3
      1413410.02      6969902.14      1412938.02      6968704.60
      1411758.58      6968208.30
#Sta/Elev= 30
  3712.8 1880.74  3790.9 1879.83  3845.0 1876.04  3880.2 1876.25  3934.3 1872.76
  3953.3 1873.74  3975.2 1871.26  4007.5 1871.59  4018.2 1870.11  4050.5 1870.63
  4082.7 1868.18  4142.3 1868.78  4313.3 1866.37  4867.4 1867.62  4953.4 1864.72
  4985.6 1865.19  5006.4 1862.87  5130.5 1868.24  5176.9 1867.08  5245.4 1861.36
  5245.9 1860.86  5274.7 1861.36  5336.7 1866.33  5383.0 1868.08  5595.8 1868.93
  5749.1 1864.93  5820.9 1865.52  5979.1 1864.98  6143.2 1868.40  6279.6 1868.09
#Mann=5,-1,0
  3712.8   0.035       0  4142.3    0.07       0  5245.4    0.07       0
  5274.7    0.07       0  5820.9   0.045       0
Bank Sta=5245.4,5274.7
Exp/Cntr=0.3,0.1

Type RM Length L Ch R = 1,1693,1032,1032,1032
BEGIN DESCRIPTION:
Clear Fork Trib2 3.0
END DESCRIPTION:
XS GIS Cut Line= 3
      1415562.82      6968839.69      1413605.00      6967738.00
      1412525.94      6967578.43
#Sta/Elev= 30
  2762.2 1887.97  3121.8 1883.09  3423.9 1882.33  3678.2 1877.87  4288.2 1879.02
  4508.8 1877.64  4546.9 1876.59  4574.4 1877.80  4584.2 1876.08  4606.2 1877.38
  4627.9 1876.12  4641.5 1877.23  4770.0 1873.12  4825.1 1870.59  4860.5 1864.27
  4892.4 1861.12  4941.6 1859.35  4942.1 1858.85  4973.2 1859.35  5108.0 1860.78
  5113.0 1861.96  5140.1 1860.86  5261.4 1861.86  5595.0 1860.36  5706.2 1860.77
  5716.3 1861.81  5736.5 1860.91  5837.6 1861.31  6009.5 1862.48  6099.5 1865.29
#Mann=5,-1,0
  2762.2    0.07       0  4508.8   0.035       0  4770.0    0.07       0
  4941.6    0.07       0  4973.2    0.07       0
Bank Sta=4941.6,4973.2
Exp/Cntr=0.3,0.1

Type RM Length L Ch R = 1,661,0,0,0
BEGIN DESCRIPTION:
Mapping XS ad957edf
END DESCRIPTION:
XS GIS Cut Line= 3
      1414608.81      6967027.17      1413583.26      6966893.62
      1413250.72      6966784.15
#Sta/Elev= 30
  3989.9 1876.03  4215.6 1877.37  4337.7 1880.31  4376.9 1881.27  4397.1 1882.57
  4410.8 1881.46  4427.4 1881.98  4447.5 1881.39  4538.3 1881.38  4585.1 1879.10
  4637.9 1875.92  4642.9 1876.16  4669.4 1873.60  4717.0 1866.84  4722.0 1866.99
  4729.9 1865.60  4770.2 1862.15  4790.4 1861.47  4949.1 1861.06  4961.8 1860.47
  4966.2 1858.47  4966.7 1857.97  4997.4 1857.97  4997.9 1858.47  5002.2 1860.20
  5032.8 1861.57  5064.4 1861.58  5127.6 1860.03  5232.8 1862.27  5374.2 1862.06
#Mann=5,-1,0
  3989.9    0.07       0  4337.7   0.035       0  4585.1    0.07       0
  4966.2    0.07       0  4997.9    0.07       0
Bank Sta=4966.2,4997.9
Exp/Cntr=0.3,0.1

Chan Stop Cuts=-1