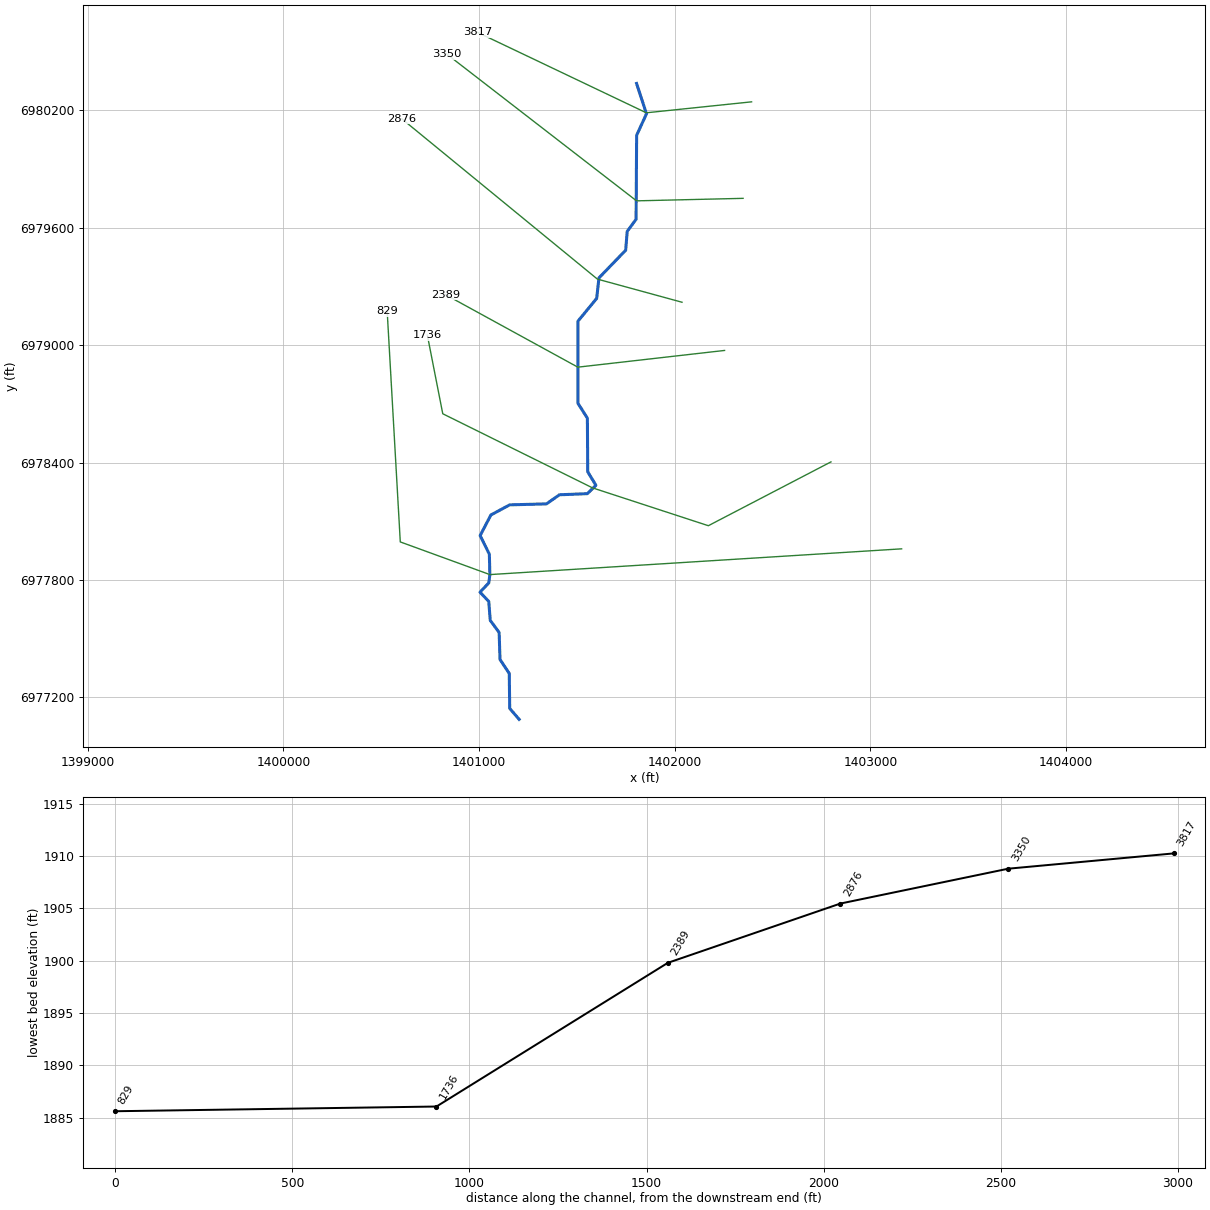
--- Clear Fork Trib2_1.prj (project) ---

Proj Title=Clear Fork Trib2_1 Base Level Engineering
Current Plan=p01
Default Exp/Contr=0.3,0.1
English Units
Geom File=g01
Flow File=f01
Plan File=p01
BEGIN DESCRIPTION:
Clear Fork Trib2_1
END DESCRIPTION:

--- Clear Fork Trib2_1.p01 (plan) ---

Plan Title=Multiple Run
Short Identifier=Multiple
Geom File=g01
Flow File=f01
Subcritical Flow
K Sum by GR= 0
Std Step Tol= 0.01
Critical Tol= 0.01
Num of Std Step Trials= 20
Max Error Tol= 0.3
Flow Tol Ratio= 0.001
Split Flow NTrial= 30
Split Flow Tol= 0.02
Split Flow Ratio= 0.02
Log Output Level= 0
Friction Slope Method= 1
Unsteady Friction Slope Method= 2
Unsteady Bridges Friction Slope Method= 1
Parabolic Critical Depth
Global Vel Dist=  1 , 1 , 1
Global Log Level= 0
CheckData=True
Encroach Param= -1, 0, 0, 0
BEGIN DESCRIPTION:
Multiple Run
END DESCRIPTION:

--- Clear Fork Trib2_1.f01 (steady flow) ---

Flow Title=Multiple
Number of Profiles=7
Profile Names=10-year,25-year,50-year,1pct_min,100-year,1pct_plu,500-year
River Rch & RM= Clear Fork Trib2,Reach-1,3817
     239     332     410     252     502    1002     762
River Rch & RM= Clear Fork Trib2,Reach-1,3350
     284     400     497     307     613    1223     942
Boundary for River Rch & Prof#=Clear Fork Trib2,Reach-1,1
Up Type=0
Dn Type=3
Dn Slope=0.005
Boundary for River Rch & Prof#=Clear Fork Trib2,Reach-1,2
Up Type=0
Dn Type=3
Dn Slope=0.005
Boundary for River Rch & Prof#=Clear Fork Trib2,Reach-1,3
Up Type=0
Dn Type=3
Dn Slope=0.005
Boundary for River Rch & Prof#=Clear Fork Trib2,Reach-1,4
Up Type=0
Dn Type=3
Dn Slope=0.005
Boundary for River Rch & Prof#=Clear Fork Trib2,Reach-1,5
Up Type=0
Dn Type=3
Dn Slope=0.005
Boundary for River Rch & Prof#=Clear Fork Trib2,Reach-1,6
Up Type=0
Dn Type=3
Dn Slope=0.005
Boundary for River Rch & Prof#=Clear Fork Trib2,Reach-1,7
Up Type=0
Dn Type=3
Dn Slope=0.005

--- Clear Fork Trib2_1.g01 (geometry) ---

Geom Title=Existing Conditions

River Reach=Clear Fork Trib2,Reach-1
Reach XY= 30
      1401805.00      6980338.00      1401855.81      6980182.97
      1401805.52      6980072.78      1401802.74      6979643.94
      1401757.36      6979582.02      1401749.48      6979485.57
      1401612.86      6979344.17      1401601.37      6979239.50
      1401505.39      6979122.84      1401505.52      6978703.22
      1401553.78      6978627.50      1401555.67      6978353.15
      1401597.32      6978284.29      1401554.01      6978241.54
      1401410.94      6978235.73      1401344.49      6978189.22
      1401156.52      6978184.26      1401060.57      6978132.42
      1401005.74      6978027.34      1401052.73      6977932.07
      1401055.47      6977827.85      1401049.87      6977785.42
      1401005.00      6977738.00      1401049.78      6977690.55
      1401057.32      6977593.96      1401102.73      6977532.06
      1401107.27      6977393.94      1401154.48      6977322.78
      1401156.89      6977143.78      1401205.00      6977088.00

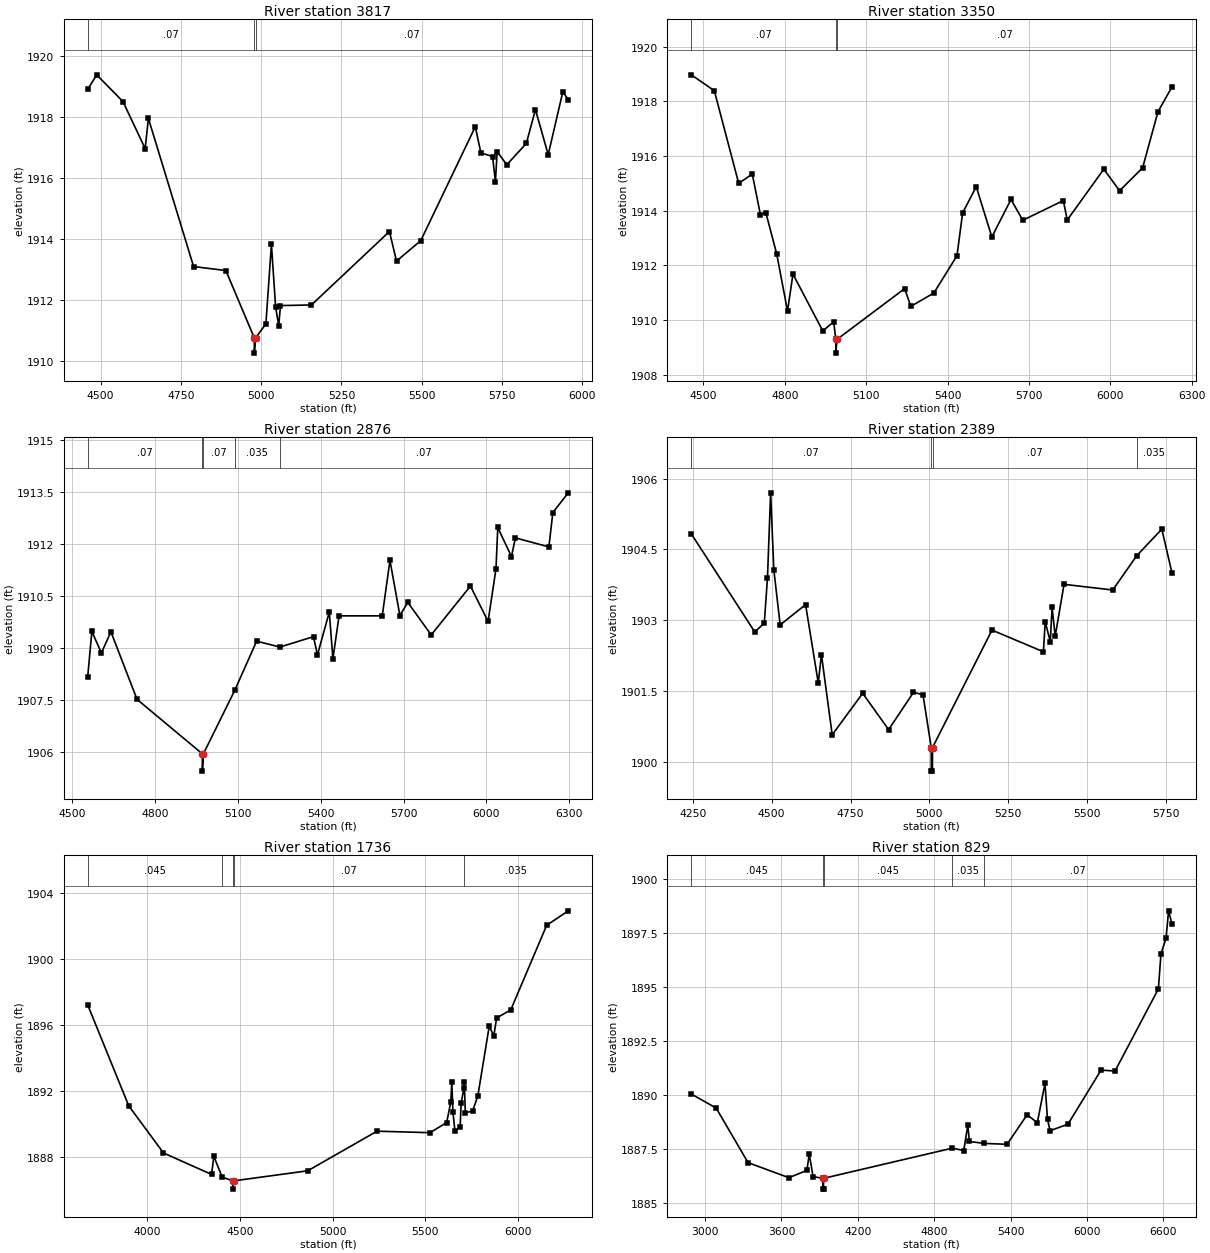
Type RM Length L Ch R = 1,3817,467,467,467
BEGIN DESCRIPTION:
Clear Fork Trib2_1 5.0
END DESCRIPTION:
XS GIS Cut Line= 3
      1402392.99      6980244.01      1401855.00      6980188.00
      1400992.25      6980599.13
#Sta/Elev= 30
  4459.9 1918.90  4488.0 1919.38  4569.9 1918.50  4638.9 1916.96  4648.9 1917.95
  4789.7 1913.09  4890.2 1912.96  4978.7 1910.75  4978.9 1910.25  4982.7 1910.75
  5014.9 1911.21  5032.1 1913.82  5045.1 1911.77  5054.8 1911.15  5060.3 1911.81
  5156.7 1911.83  5399.6 1914.24  5421.7 1913.27  5497.2 1913.94  5667.1 1917.68
  5684.3 1916.82  5720.8 1916.70  5729.7 1915.88  5735.2 1916.86  5765.1 1916.43
  5826.0 1917.13  5854.3 1918.24  5894.1 1916.76  5939.5 1918.82  5956.5 1918.57
#Mann=3,-1,0
  4459.9    0.07       0  4978.7    0.07       0  4982.7    0.07       0
Bank Sta=4978.7,4982.7
Exp/Cntr=0.3,0.1

Type RM Length L Ch R = 1,3350,474,474,474
BEGIN DESCRIPTION:
Clear Fork Trib2_1 4.0
END DESCRIPTION:
XS GIS Cut Line= 3
      1402349.64      6979750.78      1401805.00      6979738.00
      1400834.39      6980488.65
#Sta/Elev= 30
  4455.3 1918.97  4540.0 1918.39  4630.0 1915.00  4680.0 1915.34  4710.0 1913.86
  4730.0 1913.93  4770.0 1912.42  4810.0 1910.33  4830.0 1911.68  4940.1 1909.60
  4980.1 1909.94  4988.1 1909.29  4988.3 1908.79  4992.1 1909.29  5241.9 1911.15
  5264.5 1910.50  5349.6 1910.99  5434.7 1912.35  5455.6 1913.92  5505.8 1914.88
  5563.3 1913.04  5633.9 1914.41  5677.4 1913.65  5826.8 1914.37  5841.3 1913.66
  5976.2 1915.52  6034.2 1914.73  6119.3 1915.57  6175.8 1917.62  6227.1 1918.52
#Mann=3,-1,0
  4455.3    0.07       0  4988.1    0.07       0  4992.1    0.07       0
Bank Sta=4988.1,4992.1
Exp/Cntr=0.3,0.1

Type RM Length L Ch R = 1,2876,487,487,487
BEGIN DESCRIPTION:
Clear Fork Trib2_1 3.0
END DESCRIPTION:
XS GIS Cut Line= 3
      1402037.41      6979219.79      1401605.00      6979338.00
      1400605.50      6980157.21
#Sta/Elev= 30
  4555.7 1908.18  4570.8 1909.49  4605.3 1908.87  4639.8 1909.48  4734.4 1907.53
  4970.9 1905.96  4971.1 1905.46  4974.9 1905.96  5088.3 1907.79  5167.6 1909.21
  5251.8 1909.04  5373.6 1909.34  5387.9 1908.81  5430.7 1910.05  5443.9 1908.70
  5466.2 1909.94  5622.6 1909.94  5650.5 1911.54  5686.5 1909.95  5715.1 1910.33
  5799.9 1909.39  5942.0 1910.80  6005.9 1909.78  6034.6 1911.30  6041.0 1912.49
  6090.6 1911.65  6104.9 1912.19  6226.2 1911.93  6240.5 1912.92  6296.3 1913.49
#Mann=5,-1,0
  4555.7    0.07       0  4970.9    0.07       0  4974.9    0.07       0
  5088.3   0.035       0  5251.8    0.07       0
Bank Sta=4970.9,4974.9
Exp/Cntr=0.3,0.1

Type RM Length L Ch R = 1,2389,653,653,653
BEGIN DESCRIPTION:
Clear Fork Trib2_1 2.0
END DESCRIPTION:
XS GIS Cut Line= 3
      1402254.93      6978973.43      1401505.00      6978888.00
      1400830.46      6979257.52
#Sta/Elev= 30
  4245.2 1904.83  4446.4 1902.75  4476.6 1902.94  4486.7 1903.90  4496.7 1905.70
  4506.8 1904.07  4526.9 1902.90  4607.5 1903.33  4647.7 1901.67  4657.8 1902.27
  4691.9 1900.57  4788.6 1901.45  4870.8 1900.68  4949.7 1901.47  4979.8 1901.42
  5006.0 1900.30  5006.3 1899.80  5009.8 1899.80  5010.0 1900.30  5198.6 1902.79
  5361.7 1902.33  5367.4 1902.97  5383.5 1902.54  5389.2 1903.27  5399.1 1902.66
  5427.1 1903.76  5581.5 1903.64  5658.0 1904.37  5737.2 1904.93  5769.1 1904.01
#Mann=4,-1,0
  4245.2    0.07       0  5006.0    0.07       0  5010.0    0.07       0
  5658.0   0.035       0
Bank Sta=5006,5010
Exp/Cntr=0.3,0.1

Type RM Length L Ch R = 1,1736,907,907,907
BEGIN DESCRIPTION:
Mapping XS 9a550cf4
END DESCRIPTION:
XS GIS Cut Line= 5
      1402798.84      6978403.96      1402172.03      6978077.71
      1401580.14      6978271.06      1400814.64      6978649.87
      1400735.71      6979052.39
#Sta/Elev= 30
  3678.0 1897.24  3899.4 1891.13  4087.1 1888.27  4346.7 1886.97  4358.7 1888.07
  4403.6 1886.81  4461.2 1886.58  4461.5 1886.08  4465.2 1886.58  4865.4 1887.19
  5239.5 1889.59  5525.5 1889.50  5615.2 1890.11  5637.6 1891.35  5643.2 1892.56
  5649.0 1890.78  5660.1 1889.59  5688.1 1889.85  5693.7 1891.30  5708.3 1892.19
  5710.5 1892.55  5716.1 1890.70  5755.4 1890.82  5783.4 1891.71  5845.1 1895.95
  5869.7 1895.36  5885.2 1896.45  5961.4 1896.94  6155.0 1902.06  6271.6 1902.94
#Mann=5,-1,0
  3678.0   0.045       0  4403.6    0.07       0  4461.2    0.07       0
  4465.2    0.07       0  5708.3   0.035       0
Bank Sta=4461.2,4465.2
Exp/Cntr=0.3,0.1

Type RM Length L Ch R = 1,829,0,0,0
BEGIN DESCRIPTION:
Clear Fork Trib2_1 1.0
END DESCRIPTION:
XS GIS Cut Line= 4
      1403159.96      6977959.50      1401055.47      6977827.85
      1400597.61      6977994.84      1400530.58      6979173.87
#Sta/Elev= 30
  2891.4 1890.04  3086.7 1889.39  3337.2 1886.86  3657.9 1886.16  3799.8 1886.50
  3818.2 1887.26  3848.2 1886.21  3926.2 1886.13  3926.5 1885.63  3930.3 1885.63
  3930.6 1886.13  4942.1 1887.53  5032.4 1887.42  5064.4 1888.59  5076.9 1887.84
  5194.5 1887.75  5373.1 1887.71  5530.6 1889.08  5610.7 1888.71  5670.8 1890.53
  5690.8 1888.87  5710.9 1888.34  5851.1 1888.64  6111.5 1891.15  6221.7 1891.11
  6562.3 1894.92  6582.3 1896.54  6622.4 1897.27  6642.4 1898.54  6668.3 1897.94
#Mann=5,-1,0
  2891.4   0.045       0  3926.2   0.035       0  3930.6   0.045       0
  4942.1   0.035       0  5194.5    0.07       0
Bank Sta=3926.2,3930.6
Exp/Cntr=0.3,0.1

Chan Stop Cuts=-1