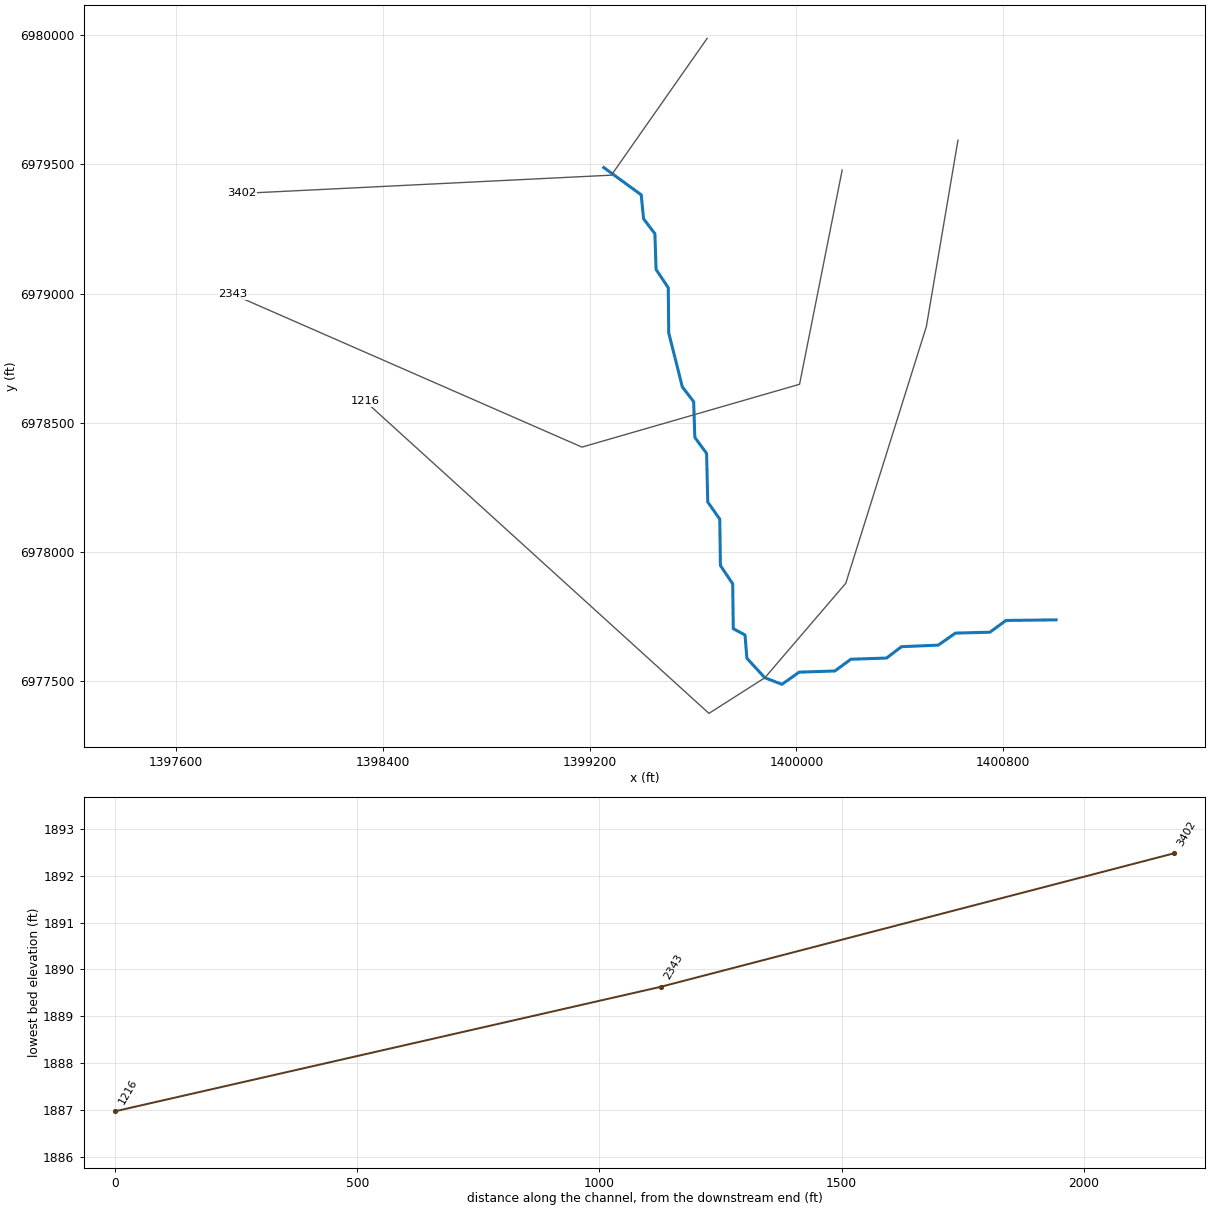
--- Clear Fork Trib2_1_1.prj (project) ---

Proj Title=Clear Fork Trib2_1_1 Base Level Engineering
Current Plan=p01
Default Exp/Contr=0.3,0.1
English Units
Geom File=g01
Flow File=f01
Plan File=p01
BEGIN DESCRIPTION:
Clear Fork Trib2_1_1
END DESCRIPTION:

--- Clear Fork Trib2_1_1.p01 (plan) ---

Plan Title=Multiple Run
Short Identifier=Multiple
Geom File=g01
Flow File=f01
Subcritical Flow
K Sum by GR= 0
Std Step Tol= 0.01
Critical Tol= 0.01
Num of Std Step Trials= 20
Max Error Tol= 0.3
Flow Tol Ratio= 0.001
Split Flow NTrial= 30
Split Flow Tol= 0.02
Split Flow Ratio= 0.02
Log Output Level= 0
Friction Slope Method= 1
Unsteady Friction Slope Method= 2
Unsteady Bridges Friction Slope Method= 1
Parabolic Critical Depth
Global Vel Dist=  1 , 1 , 1
Global Log Level= 0
CheckData=True
Encroach Param= -1, 0, 0, 0
BEGIN DESCRIPTION:
Multiple Run
END DESCRIPTION:

--- Clear Fork Trib2_1_1.f01 (steady flow) ---

Flow Title=Multiple
Number of Profiles=7
Profile Names=10-year,25-year,50-year,1pct_min,100-year,1pct_plu,500-year
River Rch & RM= Clear Fork Trib2,Reach-1,3402
     242     337     416     256     511    1019     777
River Rch & RM= Clear Fork Trib2,Reach-1,2343
     260     364     450     276     552    1101     841
Boundary for River Rch & Prof#=Clear Fork Trib2,Reach-1,1
Up Type=0
Dn Type=3
Dn Slope=0.005
Boundary for River Rch & Prof#=Clear Fork Trib2,Reach-1,2
Up Type=0
Dn Type=3
Dn Slope=0.005
Boundary for River Rch & Prof#=Clear Fork Trib2,Reach-1,3
Up Type=0
Dn Type=3
Dn Slope=0.005
Boundary for River Rch & Prof#=Clear Fork Trib2,Reach-1,4
Up Type=0
Dn Type=3
Dn Slope=0.005
Boundary for River Rch & Prof#=Clear Fork Trib2,Reach-1,5
Up Type=0
Dn Type=3
Dn Slope=0.005
Boundary for River Rch & Prof#=Clear Fork Trib2,Reach-1,6
Up Type=0
Dn Type=3
Dn Slope=0.005
Boundary for River Rch & Prof#=Clear Fork Trib2,Reach-1,7
Up Type=0
Dn Type=3
Dn Slope=0.005

--- Clear Fork Trib2_1_1.g01 (geometry) ---

Geom Title=Existing Conditions

River Reach=Clear Fork Trib2,Reach-1
Reach XY= 30
      1399255.00      6979488.00      1399399.76      6979382.54
      1399408.89      6979289.67      1399452.73      6979232.06
      1399457.27      6979093.94      1399504.48      6979022.78
      1399506.22      6978848.51      1399558.79      6978639.57
      1399602.73      6978582.06      1399607.27      6978443.94
      1399652.74      6978382.06      1399657.26      6978193.94
      1399703.78      6978127.49      1399706.22      6977948.51
      1399753.78      6977877.49      1399755.95      6977703.96
      1399801.44      6977679.50      1399808.63      6977589.55
      1399878.11      6977514.01      1399944.29      6977488.72
      1400010.93      6977535.70      1400149.06      6977540.27
      1400210.94      6977585.73      1400349.06      6977590.27
      1400406.57      6977634.21      1400549.06      6977640.27
      1400615.51      6977686.77      1400749.06      6977690.27
      1400810.93      6977735.75      1401005.00      6977738.00

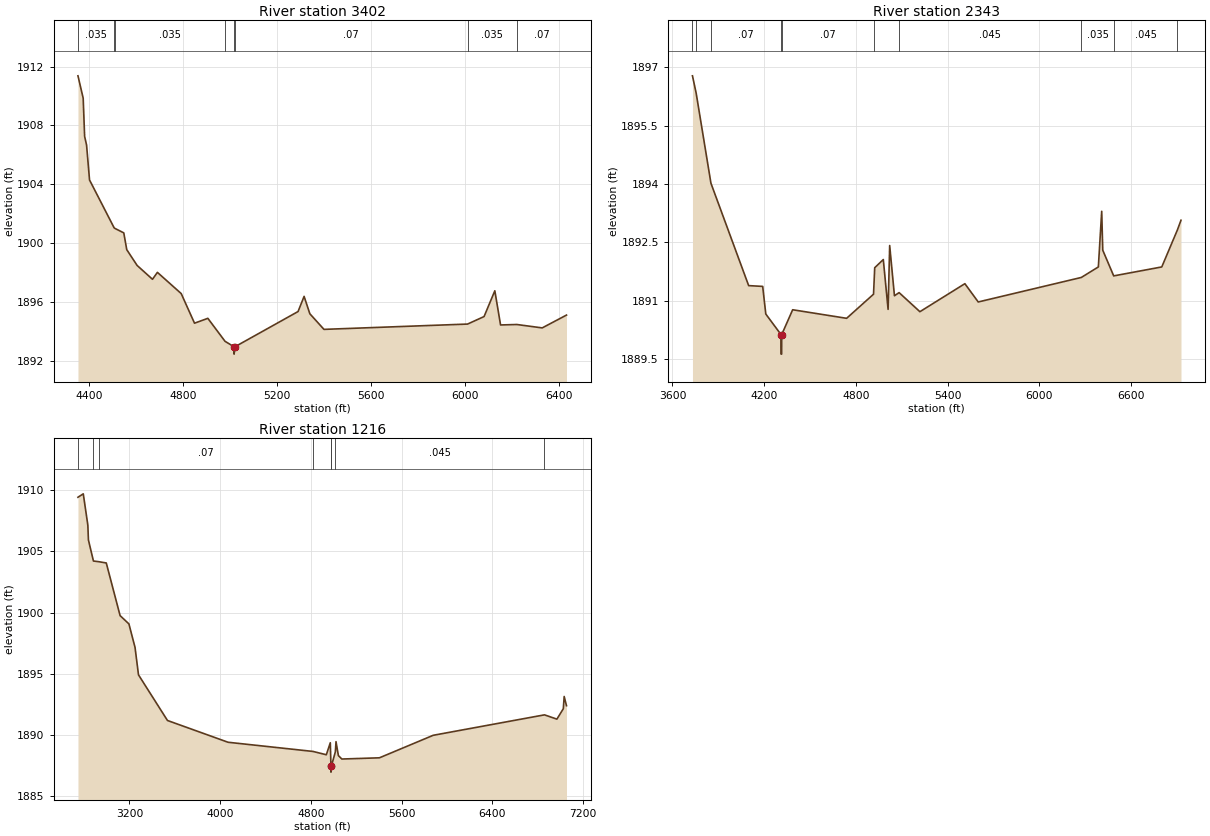
Type RM Length L Ch R = 1,3402,1059,1059,1059
BEGIN DESCRIPTION:
Clear Fork Trib2_1_1 1.0
END DESCRIPTION:
XS GIS Cut Line= 3
      1399654.99      6979987.99      1399284.28      6979458.58
      1397855.02      6979388.00
#Sta/Elev= 30
  4353.7 1911.37  4375.9 1909.85  4382.0 1907.26  4390.3 1906.67  4402.9 1904.30
  4507.6 1901.05  4512.5 1901.00  4548.5 1900.71  4561.2 1899.57  4605.2 1898.50
  4670.6 1897.56  4691.5 1898.03  4792.7 1896.59  4849.3 1894.58  4906.0 1894.91
  4979.1 1893.35  5017.3 1892.98  5017.6 1892.48  5021.3 1892.98  5289.6 1895.37
  5315.3 1896.40  5339.7 1895.22  5399.8 1894.16  6010.3 1894.52  6080.6 1895.03
  6126.3 1896.78  6150.7 1894.46  6220.1 1894.49  6327.8 1894.26  6431.0 1895.13
#Mann=8,-1,0
  4353.7   0.035       0  4507.6    0.07       0  4512.5   0.035       0
  4979.1    0.07       0  5017.3    0.07       0  5021.3    0.07       0
  6010.3   0.035       0  6220.1    0.07       0
Bank Sta=5017.3,5021.3
Exp/Cntr=0.3,0.1

Type RM Length L Ch R = 1,2343,1127,1127,1127
BEGIN DESCRIPTION:
Dry Creek Trib2 4.0
END DESCRIPTION:
XS GIS Cut Line= 4
      1400177.38      6979478.54      1400012.44      6978649.50
      1399170.42      6978406.44      1397819.83      6978997.63
#Sta/Elev= 30
  3730.9 1896.78  3755.3 1896.33  3851.8 1894.02  4098.5 1891.39  4190.3 1891.37
  4210.7 1890.66  4310.6 1890.13  4310.9 1889.63  4314.4 1889.63  4314.6 1890.13
  4386.4 1890.77  4739.4 1890.55  4915.5 1891.17  4923.2 1891.85  4979.4 1892.06
  5010.7 1890.78  5021.1 1892.42  5052.3 1891.13  5082.8 1891.21  5218.8 1890.72
  5513.1 1891.44  5600.4 1890.97  6274.9 1891.60  6386.3 1891.87  6408.2 1893.30
  6415.1 1892.30  6486.7 1891.64  6801.2 1891.87  6903.4 1892.82  6926.9 1893.07
#Mann=10,-1,0
  3730.9    0.07       0  3755.3   0.035       0  3851.8    0.07       0
  4310.6   0.035       0  4314.6    0.07       0  4915.5   0.035       0
  5082.8   0.045       0  6274.9   0.035       0  6486.7   0.045       0
  6903.4   0.035       0
Bank Sta=4310.6,4314.6
Exp/Cntr=0.3,0.1

Type RM Length L Ch R = 1,1216,0,0,0
BEGIN DESCRIPTION:
Dry Creek Trib2 5.0
END DESCRIPTION:
XS GIS Cut Line= 6
      1400625.37      6979594.14      1400503.16      6978873.30
      1400191.33      6977879.69      1399878.11      6977514.01
      1399661.82      6977376.22      1398331.79      6978583.94
#Sta/Elev= 30
  2746.0 1909.43  2792.8 1909.71  2833.1 1907.15  2838.2 1905.94  2882.4 1904.22
  2931.8 1904.16  2995.6 1904.06  3117.4 1899.76  3195.2 1899.08  3249.2 1897.16
  3279.6 1894.92  3535.1 1891.19  4069.6 1889.41  4818.6 1888.66  4935.6 1888.39
  4970.7 1889.37  4976.4 1887.47  4976.6 1886.97  4980.4 1887.47  5015.4 1888.63
  5021.0 1889.46  5042.1 1888.32  5072.6 1888.04  5404.0 1888.14  5878.3 1889.98
  6859.1 1891.65  6968.4 1891.30  7025.1 1892.15  7032.6 1893.15  7053.0 1892.40
#Mann=8,-1,0
  2746.0    0.07       0  2882.4   0.035       0  2931.8    0.07       0
  4818.6   0.035       0  4976.4   0.035       0  4980.4   0.035       0
  5015.4   0.045       0  6859.1   0.035       0
Bank Sta=4976.4,4980.4
Exp/Cntr=0.3,0.1

Chan Stop Cuts=-1