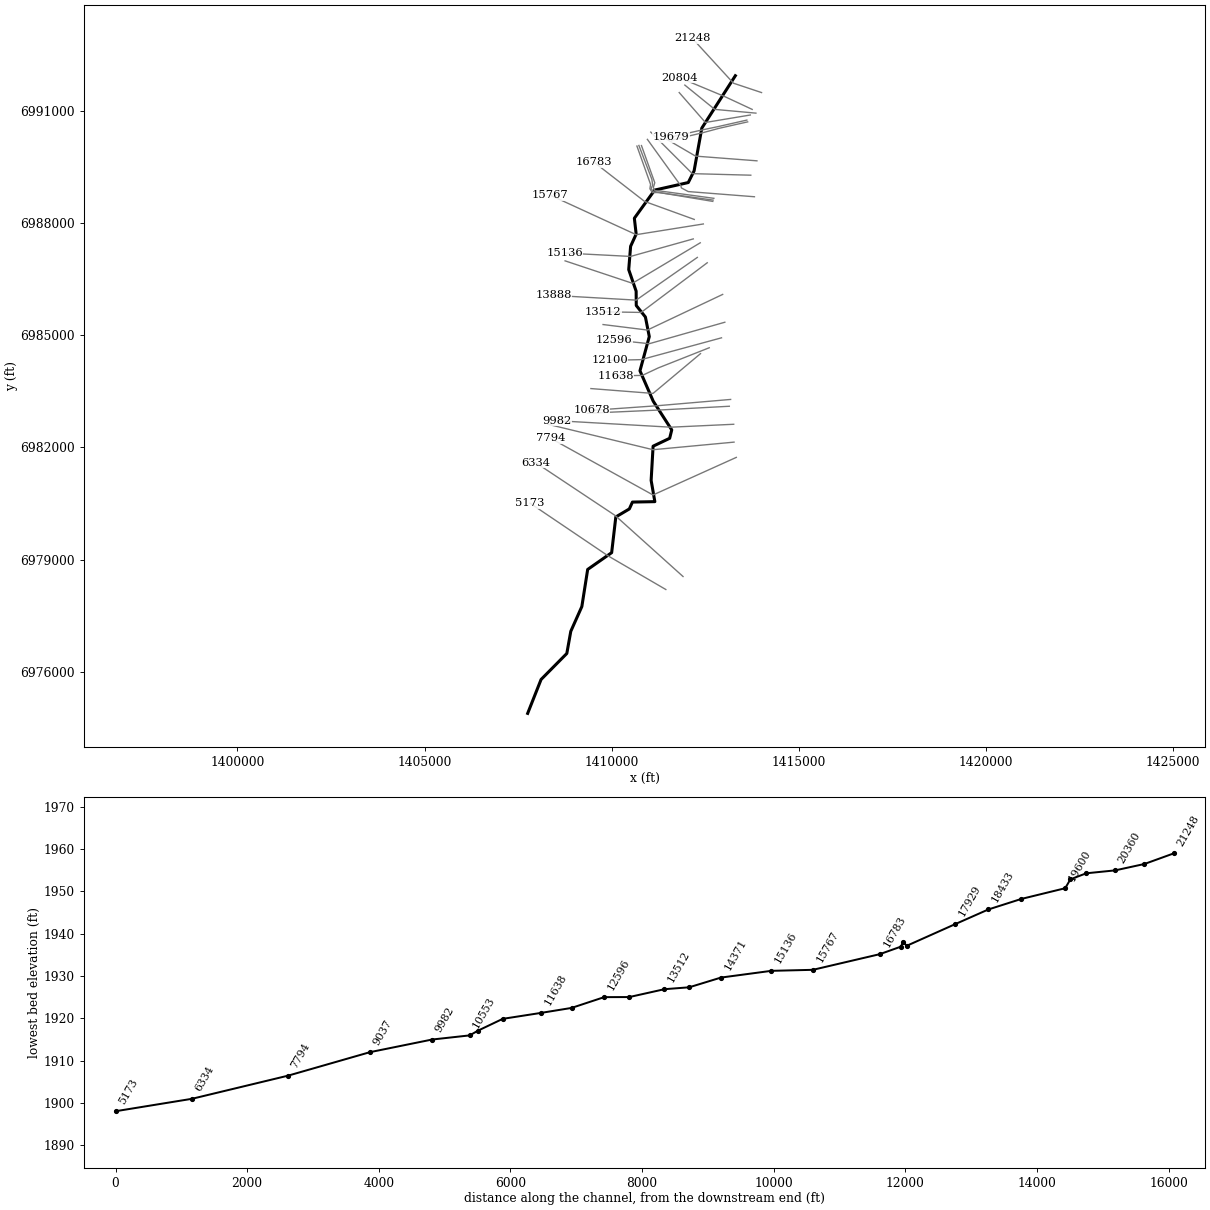
--- Clear Fork Trib2_2.prj (project) ---

Proj Title=Clear Fork Trib2_2 Base Level Engineering
Current Plan=p01
Default Exp/Contr=0.3,0.1
English Units
Geom File=g01
Flow File=f01
Plan File=p01
BEGIN DESCRIPTION:
Clear Fork Trib2_2
END DESCRIPTION:

--- Clear Fork Trib2_2.p01 (plan) ---

Plan Title=Multiple Run
Short Identifier=Multiple
Geom File=g01
Flow File=f01
Subcritical Flow
K Sum by GR= 0
Std Step Tol= 0.01
Critical Tol= 0.01
Num of Std Step Trials= 20
Max Error Tol= 0.3
Flow Tol Ratio= 0.001
Split Flow NTrial= 30
Split Flow Tol= 0.02
Split Flow Ratio= 0.02
Log Output Level= 0
Friction Slope Method= 1
Unsteady Friction Slope Method= 2
Unsteady Bridges Friction Slope Method= 1
Parabolic Critical Depth
Global Vel Dist=  1 , 1 , 1
Global Log Level= 0
CheckData=True
Encroach Param= -1, 0, 0, 0
BEGIN DESCRIPTION:
Multiple Run
END DESCRIPTION:

--- Clear Fork Trib2_2.f01 (steady flow) ---

Flow Title=Multiple
Number of Profiles=7
Profile Names=10-year,25-year,50-year,1pct_min,100-year,1pct_plu,500-year
River Rch & RM= Clear Fork Trib2,Reach-1,21248
     336     474     589     364     726    1448    1114
River Rch & RM= Clear Fork Trib2,Reach-1,14371
     460     659     827     515    1028    2052    1610
River Rch & RM= Clear Fork Trib2,Reach-1,13512
     467     668     839     522    1042    2080    1630
River Rch & RM= Clear Fork Trib2,Reach-1,9982
     584     845    1067     668    1333    2660    2109
River Rch & RM= Clear Fork Trib2,Reach-1,6334
     685     998    1268     797    1591    3175    2541
River Rch & RM= Clear Fork Trib2,Reach-1,5173
     776    1136    1448     913    1822    3636    2928
Boundary for River Rch & Prof#=Clear Fork Trib2,Reach-1,1
Up Type=0
Dn Type=3
Dn Slope=0.005
Boundary for River Rch & Prof#=Clear Fork Trib2,Reach-1,2
Up Type=0
Dn Type=3
Dn Slope=0.005
Boundary for River Rch & Prof#=Clear Fork Trib2,Reach-1,3
Up Type=0
Dn Type=3
Dn Slope=0.005
Boundary for River Rch & Prof#=Clear Fork Trib2,Reach-1,4
Up Type=0
Dn Type=3
Dn Slope=0.005
Boundary for River Rch & Prof#=Clear Fork Trib2,Reach-1,5
Up Type=0
Dn Type=3
Dn Slope=0.005
Boundary for River Rch & Prof#=Clear Fork Trib2,Reach-1,6
Up Type=0
Dn Type=3
Dn Slope=0.005
Boundary for River Rch & Prof#=Clear Fork Trib2,Reach-1,7
Up Type=0
Dn Type=3
Dn Slope=0.005

--- Clear Fork Trib2_2.g01 (geometry) ---

Geom Title=Existing Conditions

River Reach=Clear Fork Trib2,Reach-1
Reach XY= 30
      1413305.00      6991938.00      1412408.55      6990536.53
      1412202.76      6989393.93      1412046.87      6989081.93
      1411148.81      6988880.19      1410606.09      6988127.46
      1410654.49      6987703.21      1410506.22      6987377.50
      1410455.52      6986753.22      1410653.78      6986177.50
      1410657.06      6985793.86      1410901.46      6985486.53
      1411005.20      6984963.08      1410756.20      6984048.50
      1411110.46      6983235.55      1411605.11      6982467.91
      1411549.75      6982243.44      1411107.05      6982032.16
      1411054.64      6981117.85      1411153.63      6980549.53
      1410555.00      6980538.00      1410472.05      6980354.49
      1410110.73      6980140.55      1409999.54      6979185.55
      1409358.61      6978736.50      1409202.74      6977743.94
      1408907.26      6977082.06      1408801.24      6976489.56
      1408113.14      6975794.06      1407755.00      6974888.00

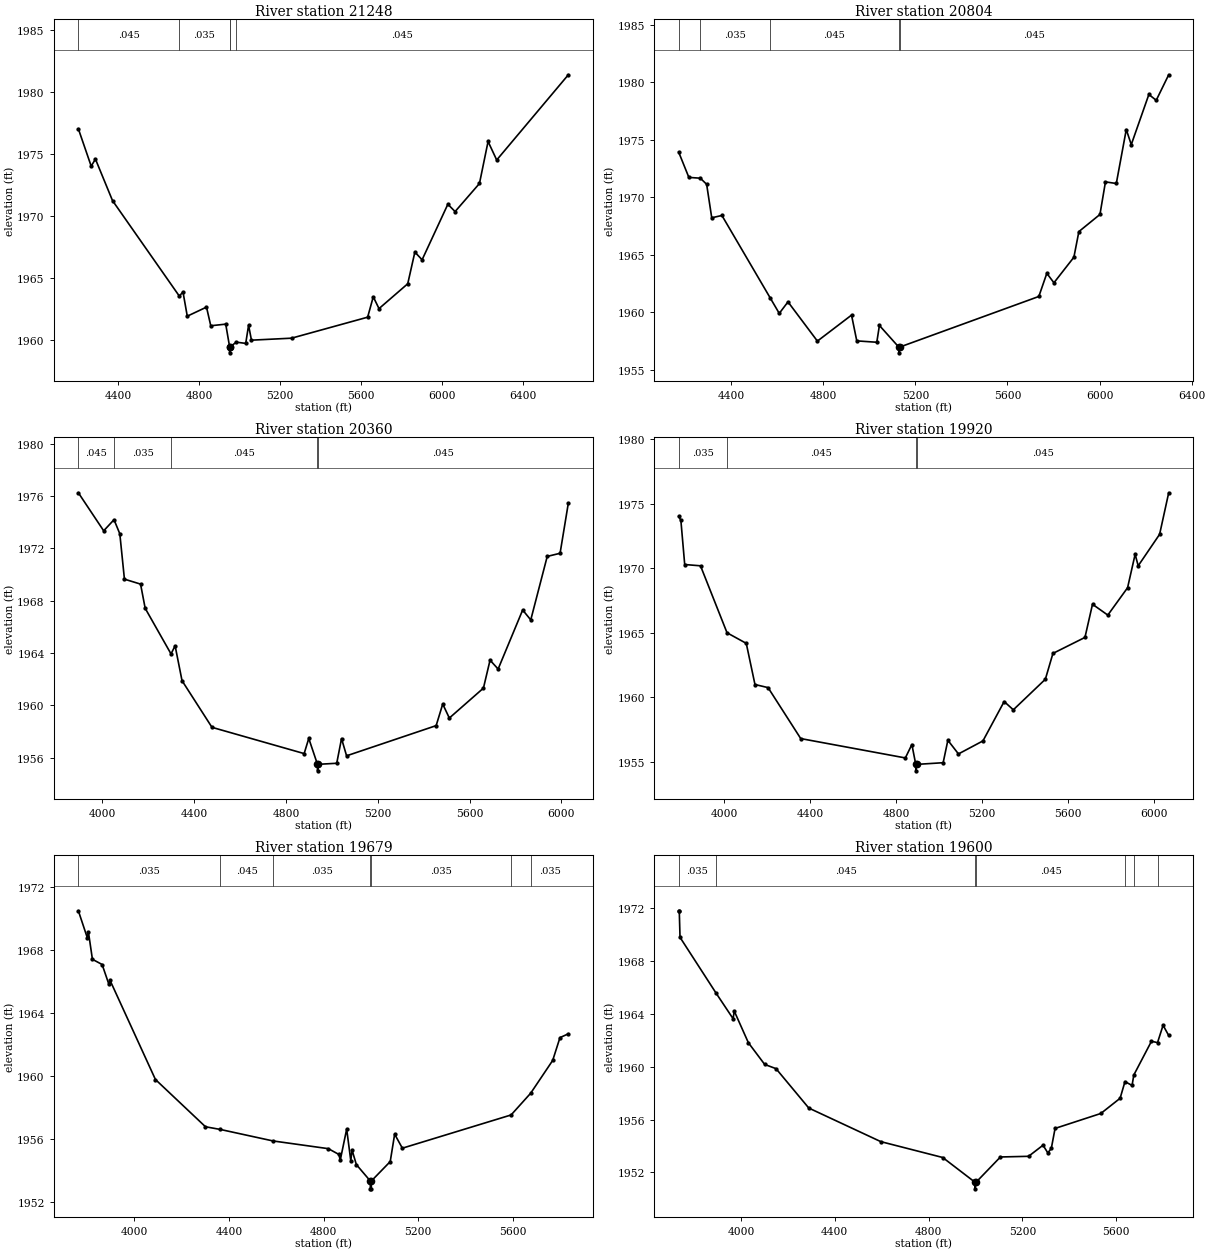
Type RM Length L Ch R = 1,21248,444,444,444
BEGIN DESCRIPTION:
Clear Fork Trib2_2 27.0
END DESCRIPTION:
XS GIS Cut Line= 3
      1414005.04      6991487.99      1413255.00      6991738.00
      1412155.00      6992938.01
#Sta/Elev= 30
  4204.5 1977.02  4267.8 1974.02  4288.9 1974.58  4373.2 1971.24  4702.7 1963.56
  4721.0 1963.89  4742.1 1961.94  4837.0 1962.67  4858.1 1961.17  4931.9 1961.30
  4950.9 1959.49  4951.2 1958.99  4954.9 1959.49  4984.0 1959.85  5030.6 1959.75
  5044.7 1961.21  5058.9 1960.01  5256.9 1960.17  5632.4 1961.86  5660.1 1963.50
  5688.5 1962.55  5830.3 1964.55  5865.5 1967.10  5901.2 1966.48  6028.3 1970.95
  6064.0 1970.36  6184.3 1972.62  6226.8 1976.00  6269.4 1974.51  6623.0 1981.37
#Mann=5,-1,0
  4204.5   0.045       0  4702.7   0.035       0  4950.9   0.045       0
  4954.9   0.035       0  4984.0   0.045       0
Bank Sta=4950.9,4954.9
Exp/Cntr=0.3,0.1

Type RM Length L Ch R = 1,20804,444,444,444
BEGIN DESCRIPTION:
Clear Fork Trib2_2 26.0
END DESCRIPTION:
XS GIS Cut Line= 3
      1413754.96      6991038.02      1413005.00      6991388.00
      1411805.00      6991888.00
#Sta/Elev= 30
  4172.4 1973.93  4216.5 1971.74  4266.4 1971.67  4293.7 1971.14  4315.8 1968.23
  4360.0 1968.43  4568.6 1961.30  4609.0 1959.92  4646.9 1960.92  4774.6 1957.51
  4922.8 1959.77  4945.6 1957.53  5032.5 1957.41  5043.9 1958.87  5128.0 1956.99
  5128.3 1956.49  5132.0 1956.99  5736.1 1961.39  5770.8 1963.40  5801.7 1962.58
  5888.3 1964.80  5910.0 1967.03  6001.5 1968.52  6025.4 1971.35  6072.5 1971.21
  6115.8 1975.90  6137.5 1974.59  6213.9 1978.95  6245.8 1978.44  6300.0 1980.66
#Mann=5,-1,0
  4172.4   0.045       0  4266.4   0.035       0  4568.6   0.045       0
  5128.0   0.045       0  5132.0   0.045       0
Bank Sta=5128,5132
Exp/Cntr=0.3,0.1

Type RM Length L Ch R = 1,20360,440,440,440
BEGIN DESCRIPTION:
Clear Fork Trib2_2 25.0
END DESCRIPTION:
XS GIS Cut Line= 3
      1413854.96      6990938.00      1412755.00      6991038.00
      1411954.97      6991688.02
#Sta/Elev= 30
  3895.3 1976.26  4005.7 1973.35  4050.7 1974.20  4076.0 1973.12  4096.1 1969.65
  4166.4 1969.27  4186.5 1967.42  4299.1 1963.93  4317.0 1964.55  4347.1 1961.88
  4477.6 1958.31  4879.3 1956.30  4899.4 1957.46  4937.3 1955.48  4937.6 1954.98
  4941.7 1955.48  5021.3 1955.56  5042.2 1957.45  5064.2 1956.13  5454.5 1958.44
  5483.2 1960.09  5512.0 1959.02  5660.6 1961.31  5689.4 1963.45  5724.6 1962.77
  5831.6 1967.29  5866.8 1966.53  5938.6 1971.39  5994.6 1971.63  6030.6 1975.47
#Mann=5,-1,0
  3895.3   0.045       0  4050.7   0.035       0  4299.1   0.045       0
  4937.3   0.045       0  4941.7   0.045       0
Bank Sta=4937.3,4941.7
Exp/Cntr=0.3,0.1

Type RM Length L Ch R = 1,19920,241,241,241
BEGIN DESCRIPTION:
Clear Fork Trib2_2 24.0
END DESCRIPTION:
XS GIS Cut Line= 3
      1413705.01      6990888.00      1412505.00      6990688.00
      1411804.98      6991488.02
#Sta/Elev= 30
  3788.7 1974.01  3798.8 1973.70  3816.6 1970.28  3890.1 1970.18  4013.5 1964.99
  4103.0 1964.17  4143.5 1960.98  4204.4 1960.74  4356.4 1956.79  4843.1 1955.29
  4873.5 1956.33  4891.5 1954.79  4891.8 1954.29  4896.0 1954.79  5019.0 1954.92
  5040.9 1956.66  5090.2 1955.60  5204.1 1956.61  5302.8 1959.66  5345.5 1959.02
  5494.5 1961.39  5529.7 1963.39  5678.7 1964.63  5713.8 1967.20  5785.0 1966.36
  5877.0 1968.48  5912.1 1971.07  5926.4 1970.18  6026.0 1972.62  6068.3 1975.84
#Mann=4,-1,0
  3788.7   0.035       0  4013.5   0.045       0  4891.5   0.045       0
  4896.0   0.045       0
Bank Sta=4891.5,4896
Exp/Cntr=0.3,0.1

Type RM Length L Ch R = 1,19679,79,79,79
BEGIN DESCRIPTION:
Mapping XS 4d8a2fa4
END DESCRIPTION:
XS GIS Cut Line= 4
      1413612.98      6990752.13      1412827.44      6990574.19
      1412410.77      6990487.38      1411590.49      6990300.76
#Sta/Elev= 30
  3762.6 1970.51  3800.2 1968.81  3805.3 1969.15  3822.1 1967.43  3863.1 1967.10
  3891.6 1965.85  3896.7 1966.09  4088.6 1959.80  4300.3 1956.80  4362.9 1956.63
  4585.8 1955.90  4819.9 1955.41  4864.9 1955.04  4870.0 1954.66  4897.4 1956.65
  4914.9 1954.64  4920.0 1955.33  4938.3 1954.40  4997.3 1953.36  4997.6 1952.86
  5001.5 1952.86  5001.9 1953.36  5081.6 1954.59  5100.3 1956.33  5132.9 1955.44
  5592.8 1957.55  5675.6 1958.93  5768.7 1961.01  5799.5 1962.46  5834.9 1962.70
#Mann=7,-1,0
  3762.6   0.035       0  4362.9   0.045       0  4585.8   0.035       0
  4997.3   0.035       0  5001.9   0.035       0  5592.8   0.045       0
  5675.6   0.035       0
Bank Sta=4997.3,5001.9
Exp/Cntr=0.3,0.1

Type RM Length L Ch R = 1,19600,668,668,668
BEGIN DESCRIPTION:
Mapping XS 679a9716
END DESCRIPTION:
XS GIS Cut Line= 4
      1413634.73      6990704.40      1412866.50      6990530.79
      1412415.11      6990409.26      1411603.44      6990218.28
#Sta/Elev= 30
  3734.8 1971.79  3737.2 1971.79  3740.4 1969.78  3894.9 1965.54  3966.6 1963.63
  3971.7 1964.20  4031.8 1961.81  4101.3 1960.17  4149.6 1959.85  4289.4 1956.87
  4596.4 1954.33  4860.3 1953.13  4997.9 1951.26  4998.3 1950.76  5002.5 1951.26
  5106.3 1953.17  5226.3 1953.22  5287.9 1954.06  5308.4 1953.48  5323.3 1953.82
  5339.3 1955.33  5534.4 1956.46  5616.6 1957.61  5637.3 1958.87  5667.5 1958.58
  5675.0 1959.37  5750.2 1961.92  5776.1 1961.82  5799.7 1963.13  5823.7 1962.36
#Mann=7,-1,0
  3734.8   0.035       0  3894.9   0.045       0  4997.9   0.045       0
  5002.5   0.045       0  5637.3    0.07       0  5675.0   0.045       0
  5776.1   0.035       0
Bank Sta=4997.9,5002.5
Exp/Cntr=0.3,0.1

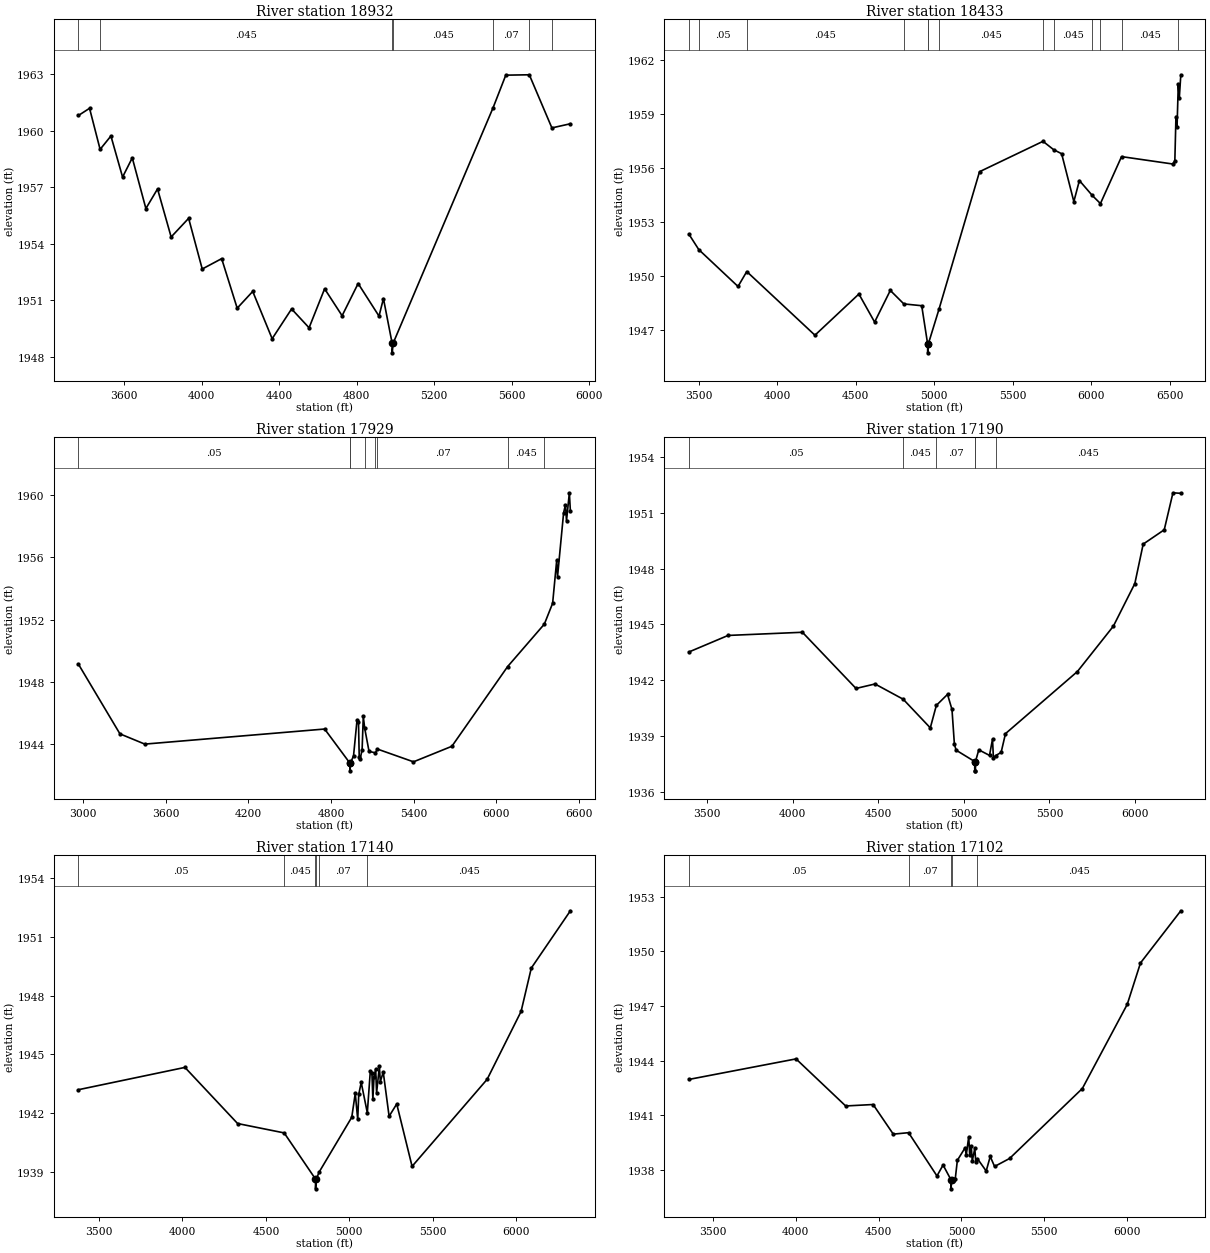
Type RM Length L Ch R = 1,18932,499,499,499
BEGIN DESCRIPTION:
Mapping XS 69d3b370
END DESCRIPTION:
XS GIS Cut Line= 3
      1413882.08      6989662.73      1412241.50      6989788.60
      1411469.43      6990239.70
#Sta/Elev= 30
  3363.5 1960.82  3420.8 1961.20  3475.3 1959.02  3531.1 1959.73  3591.3 1957.55
  3641.4 1958.57  3711.6 1955.88  3771.8 1956.92  3842.0 1954.37  3932.3 1955.36
  4002.5 1952.67  4102.8 1953.22  4183.0 1950.59  4263.2 1951.48  4363.5 1948.97
  4463.8 1950.55  4554.1 1949.55  4634.3 1951.62  4724.6 1950.19  4807.4 1951.90
  4915.1 1950.17  4938.0 1951.10  4983.0 1948.72  4983.3 1948.22  4987.6 1948.72
  5504.4 1961.24  5569.6 1962.96  5691.0 1962.98  5807.6 1960.16  5903.1 1960.38
#Mann=7,-1,0
  3363.5   0.035       0  3475.3   0.045       0  4983.0   0.045       0
  4987.6   0.045       0  5504.4    0.07       0  5691.0   0.035       0
  5807.6   0.045       0
Bank Sta=4983,4987.6
Exp/Cntr=0.3,0.1

Type RM Length L Ch R = 1,18433,504,504,504
BEGIN DESCRIPTION:
Mapping XS c57a145c
END DESCRIPTION:
XS GIS Cut Line= 3
      1413717.96      6989278.45      1412155.49      6989320.11
      1411044.36      6990431.24
#Sta/Elev= 30
  3437.2 1952.34  3500.3 1951.48  3750.3 1949.43  3806.0 1950.26  4240.4 1946.72
  4520.5 1949.01  4620.6 1947.45  4720.6 1949.21  4806.8 1948.46  4920.7 1948.36
  4958.3 1946.24  4958.7 1945.74  4963.0 1946.24  5030.6 1948.16  5289.0 1955.81
  5693.5 1957.50  5760.6 1957.04  5812.2 1956.81  5890.0 1954.15  5925.4 1955.32
  6007.4 1954.49  6059.4 1954.04  6194.0 1956.65  6519.4 1956.24  6533.5 1956.41
  6540.6 1958.88  6547.6 1958.31  6555.5 1960.67  6561.8 1959.89  6571.6 1961.20
#Mann=13,-1,0
  3437.2   0.045       0  3500.3    0.05       0  3806.0   0.045       0
  4806.8    0.07       0  4958.3    0.07       0  4963.0    0.07       0
  5030.6   0.045       0  5693.5    0.07       0  5760.6   0.045       0
  6007.4    0.07       0  6059.4   0.035       0  6194.0   0.045       0
  6555.5    0.07       0
Bank Sta=4958.3,4963
Exp/Cntr=0.3,0.1

Type RM Length L Ch R = 1,17929,739,739,739
BEGIN DESCRIPTION:
Mapping XS 1a6e4416
END DESCRIPTION:
XS GIS Cut Line= 5
      1413815.19      6988702.06      1412044.38      6988840.95
      1411863.82      6988938.17      1411849.93      6988993.72
      1410954.10      6990236.77
#Sta/Elev= 30
  2967.3 1949.13  3268.4 1944.65  3449.0 1943.99  4754.2 1944.96  4937.3 1942.77
  4937.7 1942.27  4942.0 1942.77  4964.1 1943.24  4989.7 1945.56  5000.0 1945.41
  5005.4 1943.13  5011.6 1943.02  5026.3 1943.62  5034.8 1945.77  5045.1 1945.01
  5076.6 1943.52  5122.8 1943.43  5137.5 1943.67  5399.3 1942.85  5677.9 1943.85
  6082.7 1948.98  6349.1 1951.71  6409.2 1953.05  6438.7 1955.81  6444.8 1954.77
  6489.0 1958.88  6502.6 1959.39  6509.9 1958.36  6530.7 1960.16  6538.1 1958.97
#Mann=8,-1,0
  2967.3    0.05       0  4937.3    0.05       0  4942.0    0.05       0
  5045.1    0.07       0  5122.8   0.045       0  5137.5    0.07       0
  6082.7   0.045       0  6349.1   0.035       0
Bank Sta=4937.3,4942
Exp/Cntr=0.3,0.1

Type RM Length L Ch R = 1,17190,50,50,50
BEGIN DESCRIPTION:
Mapping XS b0002d55
END DESCRIPTION:
XS GIS Cut Line= 6
      1412731.94      6988660.13      1411330.04      6988851.10
      1411152.09      6988868.46      1411113.03      6988946.58
      1411152.09      6989076.79      1410796.17      6990070.76
#Sta/Elev= 30
  3394.8 1943.52  3623.8 1944.41  4057.8 1944.58  4370.7 1941.56  4481.7 1941.80
  4646.3 1940.98  4804.6 1939.44  4839.9 1940.65  4905.1 1941.24  4931.2 1940.43
  4945.3 1938.56  4955.4 1938.24  5063.8 1937.63  5064.2 1937.13  5068.2 1937.13
  5068.5 1937.63  5087.7 1938.26  5150.3 1937.96  5167.8 1938.83  5173.1 1937.84
  5186.2 1937.95  5218.1 1938.12  5243.6 1939.13  5663.7 1942.47  5873.7 1944.91
  5999.0 1947.20  6047.7 1949.32  6170.7 1950.09  6221.6 1952.08  6267.5 1952.05
#Mann=6,-1,0
  3394.8    0.05       0  4646.3   0.045       0  4839.9    0.07       0
  5063.8    0.07       0  5068.5    0.07       0  5186.2   0.045       0
Bank Sta=5063.8,5068.5
Exp/Cntr=0.3,0.1

Type RM Length L Ch R = 1,17140,38,38,38
BEGIN DESCRIPTION:
Mapping XS f391cb67
END DESCRIPTION:
XS GIS Cut Line= 6
      1412710.23      6988612.39      1411117.37      6988833.74
      1411052.26      6988924.88      1411095.66      6989011.69
      1411073.96      6989167.94      1410727.12      6990074.06
#Sta/Elev= 30
  3376.4 1943.19  4014.6 1944.33  4330.2 1941.46  4609.5 1940.98  4797.1 1938.62
  4797.4 1938.12  4801.8 1938.62  4819.8 1938.99  5014.5 1941.78  5035.4 1943.00
  5050.2 1941.67  5056.3 1942.95  5071.1 1943.56  5107.7 1942.01  5125.6 1944.13
  5135.3 1944.06  5140.9 1942.69  5148.0 1943.86  5157.7 1944.24  5163.3 1943.03
  5180.0 1944.38  5185.6 1943.60  5203.2 1944.09  5238.3 1941.83  5284.0 1942.46
  5376.0 1939.27  5825.8 1943.72  6029.2 1947.19  6090.5 1949.41  6324.8 1952.34
#Mann=6,-1,0
  3376.4    0.05       0  4609.5   0.045       0  4797.1    0.07       0
  4801.8   0.045       0  4819.8    0.07       0  5107.7   0.045       0
Bank Sta=4797.1,4801.8
Exp/Cntr=0.3,0.1

Type RM Length L Ch R = 1,17102,319,319,319
BEGIN DESCRIPTION:
Mapping XS 8dfcb0e6
END DESCRIPTION:
XS GIS Cut Line= 6
      1412701.61      6988577.65      1411264.94      6988816.38
      1411086.98      6988812.04      1411021.88      6988916.20
      1411039.24      6989033.39      1410674.66      6990057.67
#Sta/Elev= 30
  3355.1 1942.96  4001.6 1944.09  4301.2 1941.50  4466.7 1941.58  4588.4 1939.95
  4680.7 1940.03  4852.0 1937.65  4888.9 1938.25  4936.4 1937.44  4936.7 1936.94
  4941.1 1937.44  4962.4 1937.49  4975.1 1938.51  5022.5 1939.21  5028.4 1938.78
  5043.7 1939.81  5049.6 1938.81  5059.0 1939.28  5064.9 1938.47  5080.3 1939.16
  5086.2 1938.42  5096.1 1938.60  5149.1 1937.92  5173.4 1938.72  5199.6 1938.17
  5290.1 1938.61  5729.2 1942.46  6000.1 1947.09  6080.1 1949.37  6323.4 1952.24
#Mann=5,-1,0
  3355.1    0.05       0  4680.7    0.07       0  4936.4    0.07       0
  4941.1    0.07       0  5096.1   0.045       0
Bank Sta=4936.4,4941.1
Exp/Cntr=0.3,0.1

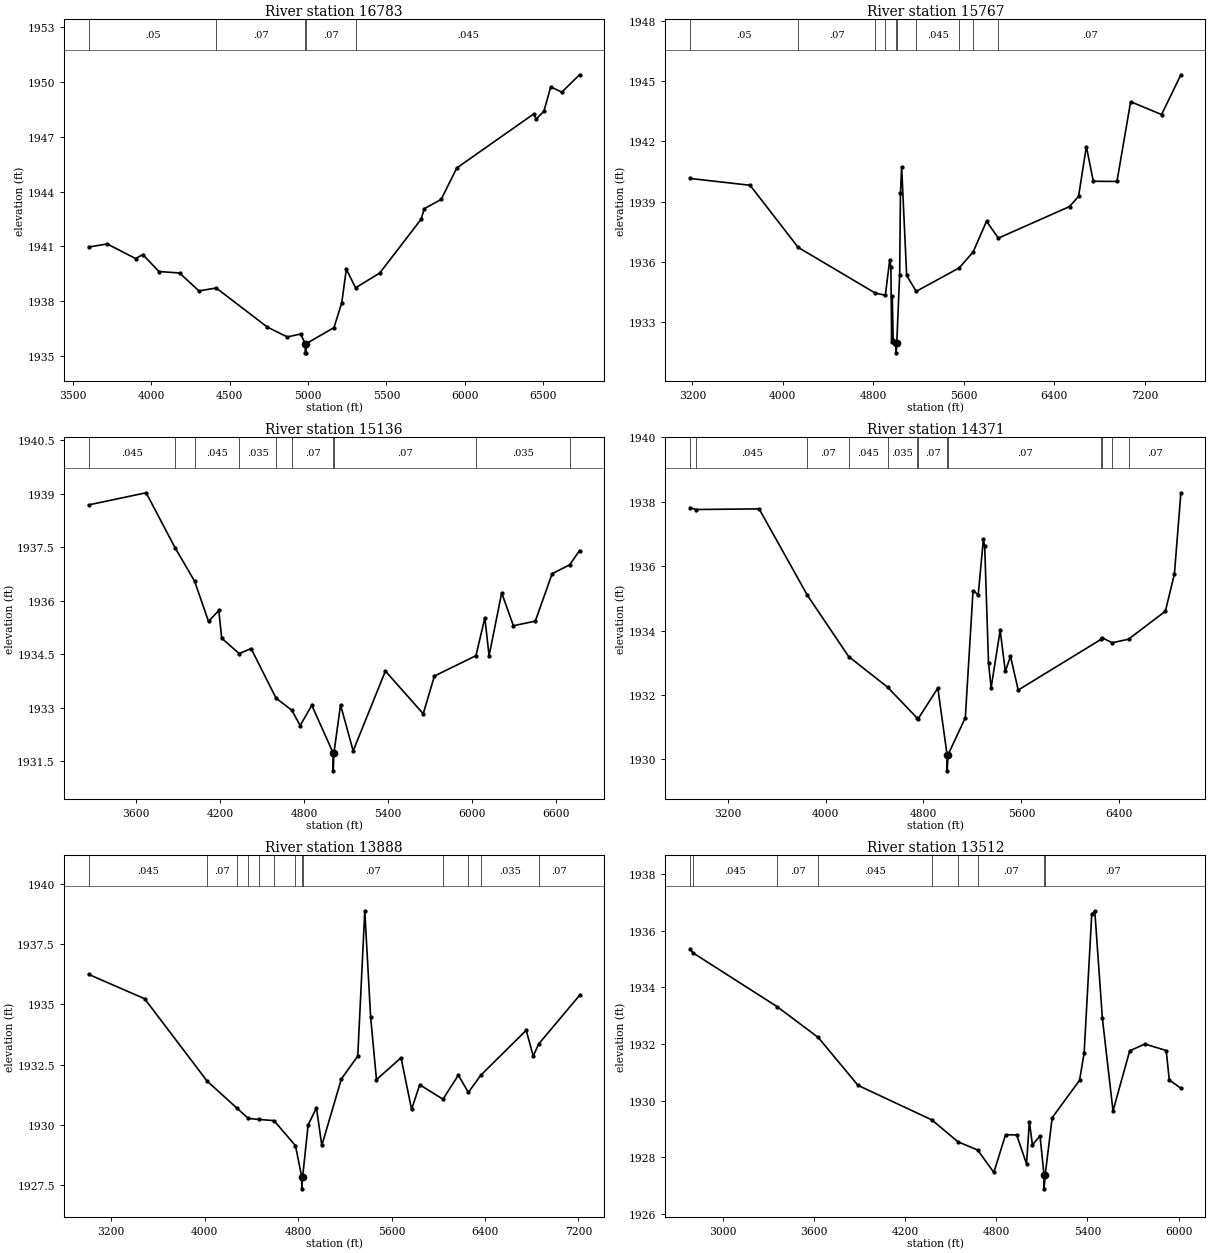
Type RM Length L Ch R = 1,16783,1016,1016,1016
BEGIN DESCRIPTION:
Mapping XS 32af1237
END DESCRIPTION:
XS GIS Cut Line= 3
      1412206.80      6988095.88      1410878.65      6988577.66
      1409520.13      6989632.36
#Sta/Elev= 30
  3599.3 1940.96  3718.2 1941.13  3899.1 1940.33  3944.8 1940.55  4048.0 1939.62
  4179.2 1939.54  4303.3 1938.56  4413.3 1938.72  4739.6 1936.58  4867.1 1936.04
  4952.2 1936.20  4981.4 1935.67  4981.8 1935.17  4986.4 1935.17  4986.8 1935.67
  5165.0 1936.55  5214.8 1937.92  5243.7 1939.75  5302.6 1938.73  5457.3 1939.54
  5720.7 1942.48  5741.5 1943.06  5849.2 1943.57  5948.8 1945.29  6440.3 1948.25
  6454.7 1947.96  6504.5 1948.39  6548.0 1949.73  6618.6 1949.44  6732.0 1950.39
#Mann=5,-1,0
  3599.3    0.05       0  4413.3    0.07       0  4981.4    0.07       0
  4986.8    0.07       0  5302.6   0.045       0
Bank Sta=4981.4,4986.8
Exp/Cntr=0.3,0.1

Type RM Length L Ch R = 1,15767,631,631,631
BEGIN DESCRIPTION:
Clear Fork Trib2_2 20.0
END DESCRIPTION:
XS GIS Cut Line= 3
      1412449.83      6987974.36      1410655.00      6987688.00
      1408361.26      6988742.61
#Sta/Elev= 30
  3178.4 1940.15  3709.9 1939.81  4135.2 1936.72  4818.2 1934.44  4906.6 1934.34
  4945.3 1936.11  4955.4 1935.76  4962.3 1932.03  4967.4 1934.30  4975.7 1932.12
  5001.9 1931.97  5002.3 1931.47  5007.5 1931.97  5033.1 1935.36  5040.0 1939.43
  5050.6 1940.71  5095.0 1935.32  5179.4 1934.53  5560.2 1935.70  5683.1 1936.49
  5801.4 1938.02  5906.2 1937.18  6535.6 1938.75  6615.6 1939.26  6684.5 1941.74
  6745.9 1940.01  6955.1 1940.00  7076.1 1943.97  7349.8 1943.33  7520.5 1945.31
#Mann=10,-1,0
  3178.4    0.05       0  4135.2    0.07       0  4818.2   0.045       0
  4906.6    0.07       0  5001.9    0.07       0  5007.5    0.07       0
  5179.4   0.045       0  5560.2    0.07       0  5683.1   0.035       0
  5906.2    0.07       0
Bank Sta=5001.9,5007.5
Exp/Cntr=0.3,0.1

Type RM Length L Ch R = 1,15136,765,765,765
BEGIN DESCRIPTION:
Mapping XS 3f9b72fd
END DESCRIPTION:
XS GIS Cut Line= 3
      1412180.73      6987575.06      1410505.39      6987106.31
      1408739.42      6987197.43
#Sta/Elev= 30
  3259.7 1938.69  3670.5 1939.03  3876.9 1937.49  4016.8 1936.55  4116.4 1935.42
  4189.8 1935.73  4210.6 1934.95  4335.5 1934.52  4420.7 1934.66  4598.9 1933.27
  4711.4 1932.93  4771.3 1932.50  4854.4 1933.07  5006.9 1931.73  5007.4 1931.23
  5012.6 1931.73  5059.8 1933.08  5150.0 1931.79  5380.3 1934.03  5650.6 1932.83
  5730.7 1933.89  6027.2 1934.46  6091.2 1935.52  6121.3 1934.46  6211.4 1936.22
  6295.1 1935.30  6451.7 1935.43  6571.9 1936.76  6697.5 1937.01  6767.7 1937.41
#Mann=10,-1,0
  3259.7   0.045       0  3876.9    0.07       0  4016.8   0.045       0
  4335.5   0.035       0  4598.9   0.045       0  4711.4    0.07       0
  5006.9    0.07       0  5012.6    0.07       0  6027.2   0.035       0
  6697.5    0.07       0
Bank Sta=5006.9,5012.6
Exp/Cntr=0.3,0.1

Type RM Length L Ch R = 1,14371,483,483,483
BEGIN DESCRIPTION:
Clear Fork Trib2_2 19.0
END DESCRIPTION:
XS GIS Cut Line= 3
      1412367.36      6987470.88      1410555.00      6986388.00
      1408754.99      6986988.00
#Sta/Elev= 30
  2893.4 1937.82  2940.5 1937.76  3457.9 1937.78  3851.4 1935.10  4189.3 1933.19
  4506.9 1932.24  4745.7 1931.29  4757.0 1931.26  4917.1 1932.21  4992.8 1930.14
  4993.3 1929.64  5000.9 1930.14  5141.7 1931.29  5204.9 1935.24  5247.1 1935.11
  5289.2 1936.83  5299.8 1936.64  5331.4 1932.98  5352.5 1932.22  5426.3 1934.01
  5468.4 1932.73  5510.6 1933.20  5573.8 1932.15  6252.1 1933.73  6255.0 1933.78
  6341.6 1933.62  6474.4 1933.73  6775.5 1934.60  6849.3 1935.76  6902.0 1938.28
#Mann=13,-1,0
  2893.4    0.07       0  2940.5   0.045       0  3851.4    0.07       0
  4189.3   0.045       0  4506.9   0.035       0  4745.7   0.045       0
  4757.0    0.07       0  4992.8    0.07       0  5000.9    0.07       0
  6252.1   0.035       0  6255.0    0.07       0  6341.6   0.035       0
  6474.4    0.07       0
Bank Sta=4992.8,5000.9
Exp/Cntr=0.3,0.1

Type RM Length L Ch R = 1,13888,376,376,376
BEGIN DESCRIPTION:
Clear Fork Trib2_2 18.0
END DESCRIPTION:
XS GIS Cut Line= 3
      1412289.24      6987080.26      1410655.00      6985938.00
      1408449.09      6986064.58
#Sta/Elev= 30
  3006.1 1936.24  3485.5 1935.23  4020.8 1931.81  4278.0 1930.68  4373.7 1930.26
  4466.2 1930.22  4593.8 1930.17  4777.2 1929.13  4830.6 1927.84  4831.1 1927.34
  4838.7 1927.84  4885.3 1929.99  4956.8 1930.70  5002.5 1929.14  5170.2 1931.90
  5310.5 1932.85  5370.6 1938.88  5420.7 1934.47  5470.7 1931.87  5681.1 1932.78
  5771.2 1930.64  5841.3 1931.66  6039.9 1931.06  6171.9 1932.06  6257.6 1931.34
  6362.7 1932.05  6752.8 1933.92  6812.9 1932.85  6859.5 1933.35  7209.5 1935.37
#Mann=13,-1,0
  3006.1   0.045       0  4020.8    0.07       0  4278.0   0.045       0
  4373.7    0.07       0  4466.2   0.035       0  4593.8   0.045       0
  4777.2    0.07       0  4830.6    0.07       0  4838.7    0.07       0
  6039.9   0.035       0  6257.6    0.07       0  6362.7   0.035       0
  6859.5    0.07       0
Bank Sta=4830.6,4838.7
Exp/Cntr=0.3,0.1

Type RM Length L Ch R = 1,13512,535,535,535
BEGIN DESCRIPTION:
Mapping XS c51c6178
END DESCRIPTION:
XS GIS Cut Line= 3
      1412554.02      6986937.05      1410787.50      6985608.91
      1409768.64      6985625.79
#Sta/Elev= 30
  2785.9 1935.35  2807.2 1935.21  3358.5 1933.32  3629.6 1932.23  3891.4 1930.54
  4377.7 1929.32  4548.4 1928.55  4678.0 1928.26  4784.8 1927.47  4861.9 1928.80
  4934.8 1928.79  4999.7 1927.77  5018.5 1929.26  5038.5 1928.44  5088.5 1928.76
  5114.5 1927.39  5115.0 1926.89  5122.6 1927.39  5168.5 1929.40  5348.5 1930.72
  5378.6 1931.68  5428.6 1936.57  5448.6 1936.70  5498.6 1932.91  5568.6 1929.64
  5678.6 1931.76  5778.6 1932.00  5918.6 1931.77  5938.6 1930.73  6015.0 1930.44
#Mann=9,-1,0
  2785.9    0.07       0  2807.2   0.045       0  3358.5    0.07       0
  3629.6   0.045       0  4377.7   0.035       0  4548.4   0.045       0
  4678.0    0.07       0  5114.5    0.07       0  5122.6    0.07       0
Bank Sta=5114.5,5122.6
Exp/Cntr=0.3,0.1

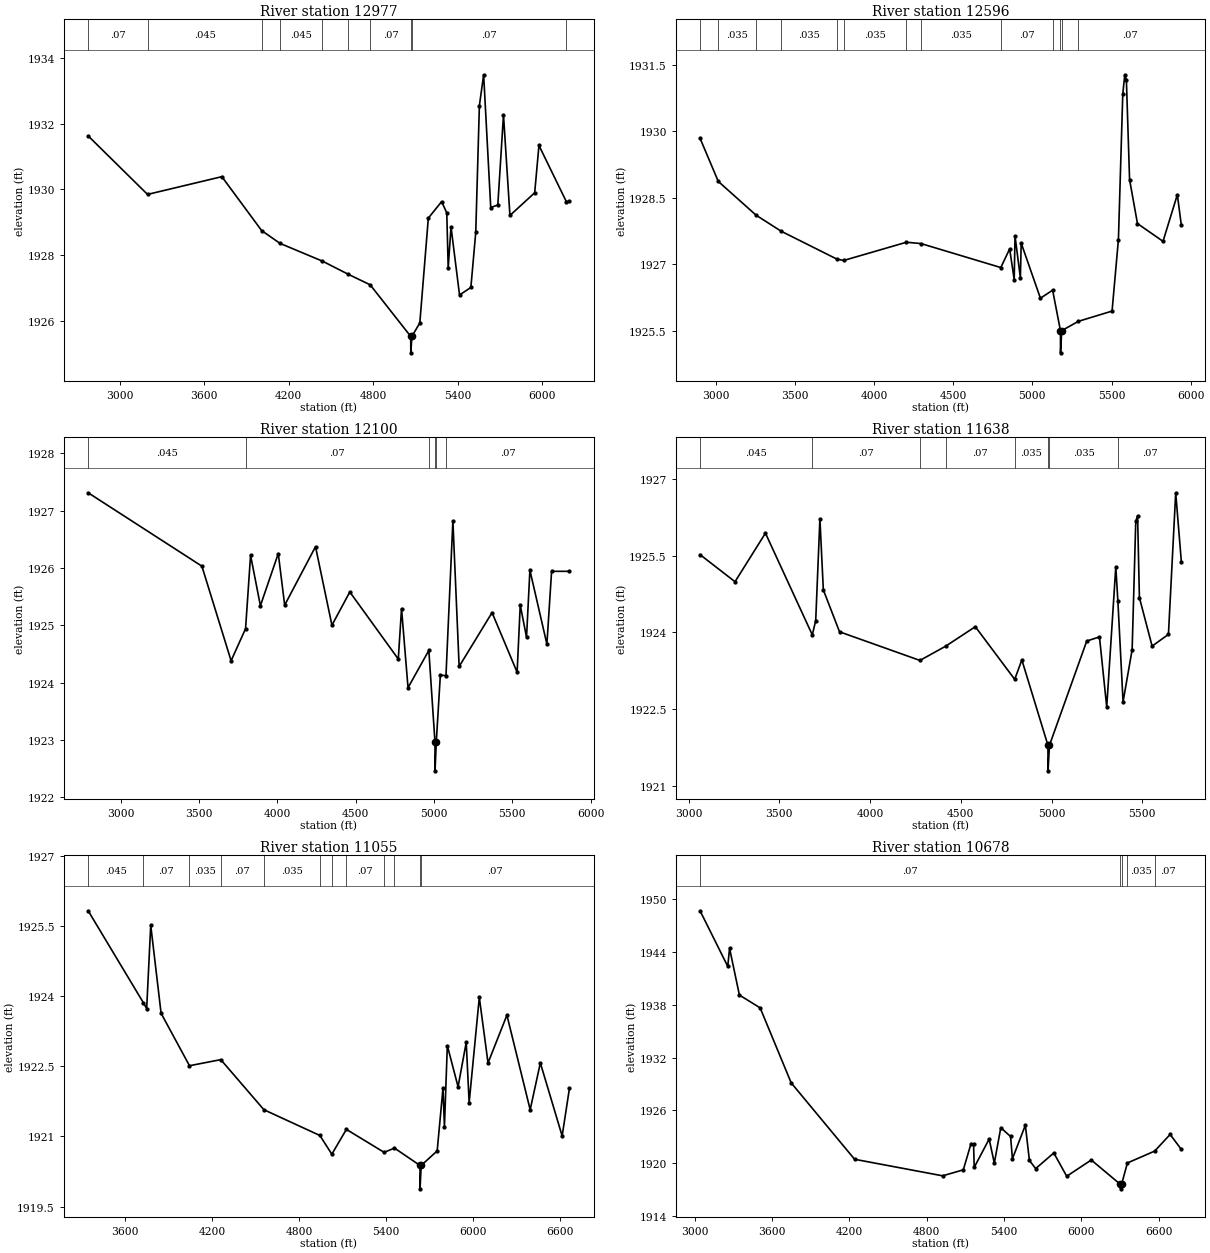
Type RM Length L Ch R = 1,12977,381,381,381
BEGIN DESCRIPTION:
Clear Fork Trib2_2 17.0
END DESCRIPTION:
XS GIS Cut Line= 3
      1412966.31      6986090.68      1410955.00      6985138.00
      1409769.81      6985285.03
#Sta/Elev= 30
  2774.4 1931.63  3196.2 1929.85  3724.3 1930.39  4007.0 1928.75  4137.6 1928.36
  4438.9 1927.82  4622.6 1927.42  4778.1 1927.10  5066.3 1925.53  5066.8 1925.03
  5074.6 1925.53  5130.9 1925.94  5191.4 1929.13  5285.7 1929.63  5322.4 1929.29
  5332.5 1927.62  5352.6 1928.86  5413.1 1926.79  5493.7 1927.02  5528.4 1928.70
  5554.1 1932.55  5584.4 1933.49  5634.8 1929.45  5685.1 1929.53  5725.4 1932.27
  5771.2 1929.21  5947.1 1929.90  5977.4 1931.34  6171.9 1929.63  6194.2 1929.64
#Mann=10,-1,0
  2774.4    0.07       0  3196.2   0.045       0  4007.0    0.07       0
  4137.6   0.045       0  4438.9   0.035       0  4622.6   0.045       0
  4778.1    0.07       0  5066.3    0.07       0  5074.6    0.07       0
  6171.9   0.035       0
Bank Sta=5066.3,5074.6
Exp/Cntr=0.3,0.1

Type RM Length L Ch R = 1,12596,496,496,496
BEGIN DESCRIPTION:
Clear Fork Trib2_2 16.0
END DESCRIPTION:
XS GIS Cut Line= 3
      1413024.05      6985346.84      1411005.49      6984772.80
      1410069.79      6984871.60
#Sta/Elev= 30
  2901.4 1929.84  3016.4 1928.87  3254.9 1928.11  3412.6 1927.75  3765.6 1927.12
  3808.8 1927.09  4205.0 1927.50  4296.7 1927.47  4800.7 1926.93  4856.6 1927.35
  4885.3 1926.66  4890.5 1927.64  4924.3 1926.70  4929.5 1927.48  5050.8 1926.24
  5128.0 1926.42  5177.3 1925.51  5177.8 1925.01  5185.6 1925.51  5291.2 1925.72
  5503.3 1925.95  5543.5 1927.56  5571.0 1930.84  5583.7 1931.27  5593.8 1931.15
  5613.9 1928.91  5663.8 1927.92  5825.1 1927.52  5915.6 1928.57  5940.9 1927.88
#Mann=13,-1,0
  2901.4   0.045       0  3016.4   0.035       0  3254.9   0.045       0
  3412.6   0.035       0  3765.6    0.07       0  3808.8   0.035       0
  4205.0    0.07       0  4296.7   0.035       0  4800.7    0.07       0
  5128.0   0.035       0  5177.3    0.07       0  5185.6   0.035       0
  5291.2    0.07       0
Bank Sta=5177.3,5185.6
Exp/Cntr=0.3,0.1

Type RM Length L Ch R = 1,12100,462,462,462
BEGIN DESCRIPTION:
Mapping XS 5bbbd495
END DESCRIPTION:
XS GIS Cut Line= 3
      1412935.53      6984930.18      1410789.72      6984346.86
      1409940.94      6984327.01
#Sta/Elev= 30
  2792.3 1927.31  3518.3 1926.03  3704.8 1924.38  3797.2 1924.94  3829.1 1926.22
  3891.8 1925.34  4006.0 1926.25  4046.8 1925.35  4243.7 1926.37  4348.5 1925.00
  4462.7 1925.58  4772.2 1924.41  4792.9 1925.29  4834.3 1923.91  4967.2 1924.56
  5006.4 1922.96  5006.9 1922.46  5014.7 1922.96  5040.7 1924.13  5076.6 1924.12
  5120.7 1926.82  5160.7 1924.28  5370.8 1925.22  5530.8 1924.18  5550.8 1925.35
  5590.9 1924.79  5612.4 1925.96  5720.9 1924.67  5750.9 1925.94  5865.0 1925.94
#Mann=6,-1,0
  2792.3   0.045       0  3797.2    0.07       0  4967.2   0.035       0
  5006.4   0.035       0  5014.7   0.035       0  5076.6    0.07       0
Bank Sta=5006.4,5014.7
Exp/Cntr=0.3,0.1

Type RM Length L Ch R = 1,11638,583,583,583
BEGIN DESCRIPTION:
Clear Fork Trib2_2 15.0
END DESCRIPTION:
XS GIS Cut Line= 4
      1412607.41      6984664.56      1411245.87      6984125.61
      1410818.64      6983924.80      1410103.93      6983913.48
#Sta/Elev= 30
  3063.6 1925.52  3256.2 1924.99  3423.8 1925.94  3681.9 1923.95  3700.7 1924.23
  3723.8 1926.22  3742.7 1924.83  3831.9 1924.01  4274.8 1923.45  4417.2 1923.73
  4579.9 1924.11  4796.8 1923.08  4836.2 1923.46  4979.9 1921.79  4980.4 1921.29
  4988.3 1921.79  5193.7 1923.83  5263.7 1923.91  5303.7 1922.54  5353.7 1925.28
  5365.2 1924.61  5393.7 1922.64  5443.7 1923.66  5463.7 1926.17  5473.7 1926.28
  5483.7 1924.68  5553.7 1923.73  5643.7 1923.96  5683.7 1926.73  5714.8 1925.38
#Mann=8,-1,0
  3063.6   0.045       0  3681.9    0.07       0  4274.8   0.035       0
  4417.2    0.07       0  4796.8   0.035       0  4979.9   0.035       0
  4988.3   0.035       0  5365.2    0.07       0
Bank Sta=4979.9,4988.3
Exp/Cntr=0.3,0.1

Type RM Length L Ch R = 1,11055,377,377,377
BEGIN DESCRIPTION:
Clear Fork Trib2_2 14.0
END DESCRIPTION:
XS GIS Cut Line= 3
      1412374.34      6984507.56      1411105.44      6983443.18
      1409444.61      6983573.01
#Sta/Elev= 30
  3343.8 1925.82  3724.0 1923.86  3747.6 1923.73  3775.6 1925.51  3847.1 1923.63
  4043.1 1922.51  4259.1 1922.64  4556.8 1921.57  4943.0 1921.02  5025.7 1920.62
  5126.1 1921.15  5386.4 1920.66  5458.2 1920.75  5634.1 1920.38  5634.6 1919.88
  5642.5 1920.38  5752.7 1920.69  5792.9 1922.03  5802.9 1921.21  5822.9 1922.94
  5897.0 1922.06  5953.3 1923.01  5973.4 1921.72  6043.6 1923.97  6103.8 1922.57
  6234.2 1923.59  6394.7 1921.57  6464.9 1922.57  6615.4 1921.01  6665.9 1922.03
#Mann=12,-1,0
  3343.8   0.045       0  3724.0    0.07       0  4043.1   0.035       0
  4259.1    0.07       0  4556.8   0.035       0  4943.0    0.07       0
  5025.7   0.035       0  5126.1    0.07       0  5386.4   0.035       0
  5458.2    0.07       0  5634.1    0.07       0  5642.5    0.07       0
Bank Sta=5634.1,5642.5
Exp/Cntr=0.3,0.1

Type RM Length L Ch R = 1,10678,125,125,125
BEGIN DESCRIPTION:
Clear Fork Trib2_2 13.0
END DESCRIPTION:
XS GIS Cut Line= 3
      1413179.03      6983282.52      1411228.82      6983114.87
      1409458.25      6982989.58
#Sta/Elev= 30
  3042.6 1948.69  3257.4 1942.37  3271.5 1944.42  3347.7 1939.11  3508.7 1937.65
  3749.2 1929.13  4241.0 1920.44  4923.5 1918.56  5084.0 1919.24  5144.2 1922.23
  5163.7 1922.16  5168.7 1919.52  5284.5 1922.74  5324.6 1920.01  5374.8 1924.03
  5450.7 1923.03  5465.0 1920.50  5565.2 1924.31  5596.7 1920.31  5645.4 1919.38
  5785.8 1921.16  5886.0 1918.51  6076.5 1920.36  6302.9 1917.58  6303.4 1917.08
  6311.3 1917.58  6356.5 1920.02  6567.9 1921.37  6688.0 1923.26  6775.0 1921.56
#Mann=5,-1,0
  3042.6    0.07       0  6302.9    0.07       0  6311.3    0.07       0
  6356.5   0.035       0  6567.9    0.07       0
Bank Sta=6302.9,6311.3
Exp/Cntr=0.3,0.1

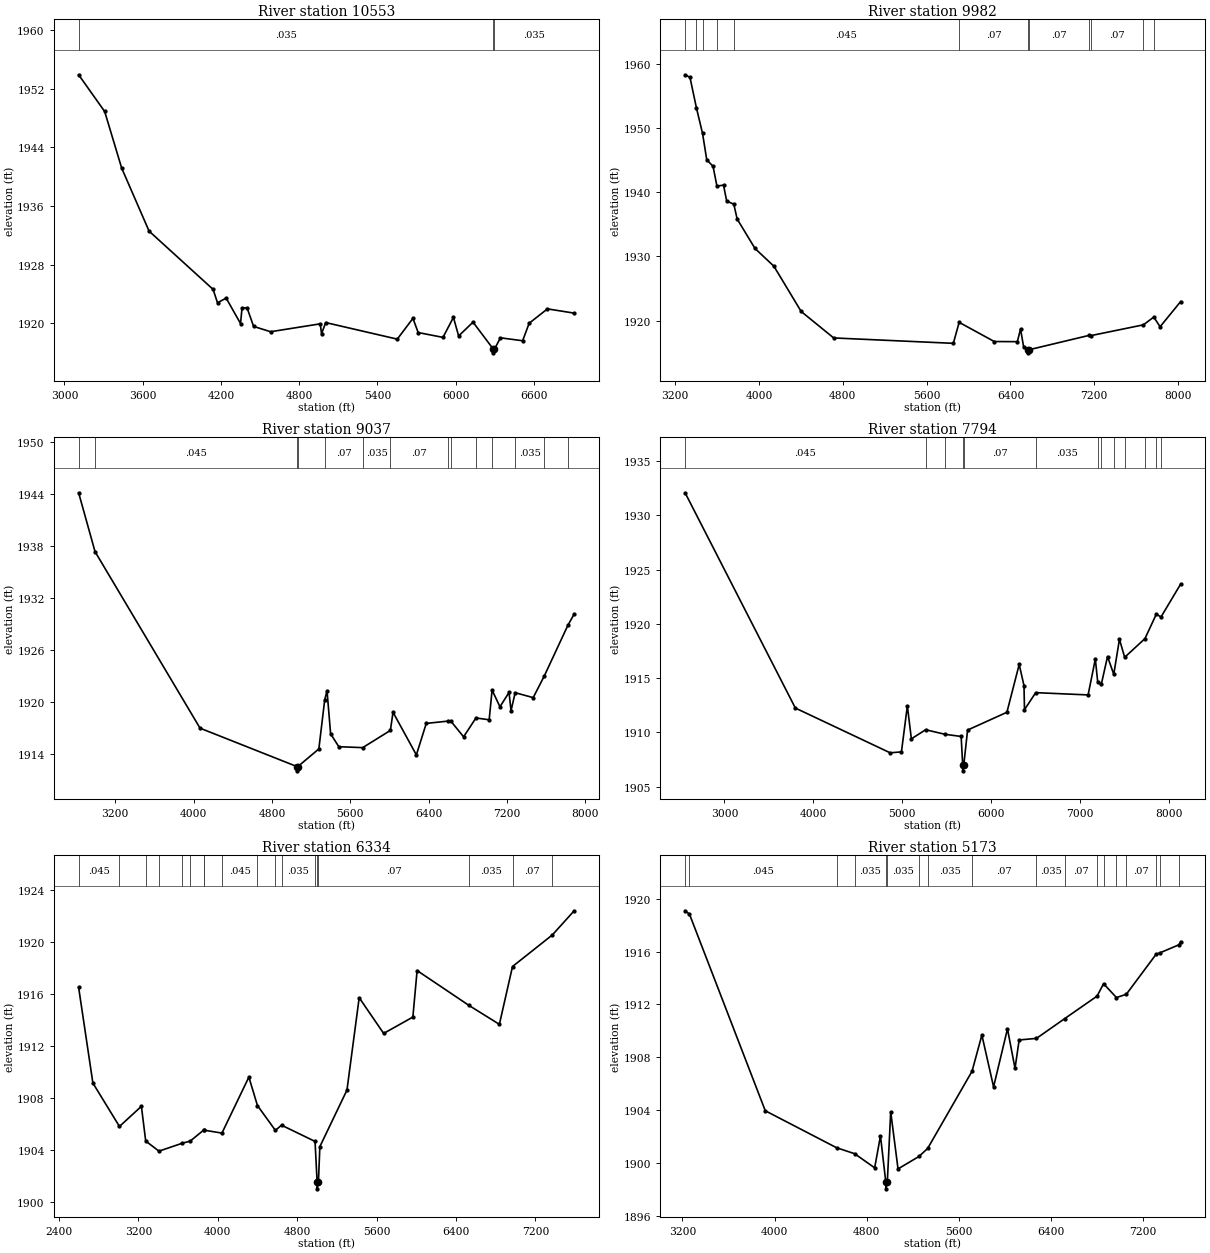
Type RM Length L Ch R = 1,10553,571,571,571
BEGIN DESCRIPTION:
Mapping XS 3666ac64
END DESCRIPTION:
XS GIS Cut Line= 3
      1413144.27      6983100.23      1411256.11      6982998.46
      1409350.33      6982913.02
#Sta/Elev= 30
  3109.1 1953.92  3308.7 1948.91  3438.9 1941.19  3649.2 1932.58  4139.9 1924.63
  4173.7 1922.80  4240.0 1923.44  4350.2 1919.97  4361.7 1922.10  4400.2 1922.11
  4450.3 1919.58  4580.5 1918.85  4961.1 1919.93  4971.1 1918.58  5003.1 1920.10
  5551.7 1917.84  5671.8 1920.68  5711.8 1918.74  5902.0 1918.08  5982.1 1920.81
  6022.1 1918.27  6132.3 1920.16  6288.2 1916.47  6288.7 1915.97  6296.6 1916.47
  6342.5 1918.02  6512.6 1917.62  6562.7 1920.01  6702.8 1921.97  6907.7 1921.39
#Mann=3,-1,0
  3109.1   0.035       0  6288.2   0.035       0  6296.6   0.035       0
Bank Sta=6288.2,6296.6
Exp/Cntr=0.3,0.1

Type RM Length L Ch R = 1,9982,945,945,945
BEGIN DESCRIPTION:
Mapping XS be85417a
END DESCRIPTION:
XS GIS Cut Line= 3
      1413261.42      6982618.46      1411577.44      6982540.33
      1408539.59      6982713.93
#Sta/Elev= 30
  3295.4 1958.29  3341.9 1957.89  3403.6 1953.13  3462.0 1949.15  3502.0 1945.05
  3562.1 1944.04  3599.1 1940.95  3662.2 1941.11  3692.2 1938.62  3760.2 1938.14
  3792.4 1935.82  3962.5 1931.24  4142.7 1928.48  4403.0 1921.43  4713.3 1917.31
  5855.1 1916.47  5910.5 1919.74  6245.7 1916.75  6466.1 1916.73  6496.1 1918.70
  6526.1 1915.89  6570.7 1915.49  6571.2 1914.99  6581.7 1915.49  7150.9 1917.71
  7170.2 1917.68  7668.4 1919.35  7767.8 1920.56  7827.9 1919.05  8024.0 1922.97
#Mann=12,-1,0
  3295.4    0.07       0  3403.6   0.035       0  3462.0    0.07       0
  3599.1   0.035       0  3760.2   0.045       0  5910.5    0.07       0
  6570.7   0.045       0  6581.7    0.07       0  7150.9   0.035       0
  7170.2    0.07       0  7668.4   0.035       0  7767.8    0.07       0
Bank Sta=6570.7,6581.7
Exp/Cntr=0.3,0.1

Type RM Length L Ch R = 1,9037,1243,1243,1243
BEGIN DESCRIPTION:
Clear Fork Trib2_2 11.0
END DESCRIPTION:
XS GIS Cut Line= 3
      1413270.13      6982141.03      1411104.92      6981938.03
      1408298.11      6982617.99
#Sta/Elev= 30
  2825.3 1944.13  2992.8 1937.33  4065.8 1916.93  5054.5 1912.50  5055.0 1912.00
  5065.6 1912.50  5279.4 1914.53  5339.5 1920.22  5363.0 1921.25  5399.7 1916.28
  5483.3 1914.79  5727.3 1914.68  6010.4 1916.67  6037.2 1918.77  6275.8 1913.84
  6376.9 1917.48  6601.2 1917.75  6626.7 1917.76  6758.4 1915.93  6884.4 1918.11
  7019.5 1917.90  7049.5 1921.33  7129.8 1919.40  7222.4 1921.06  7243.0 1918.95
  7285.3 1921.03  7469.3 1920.46  7581.8 1922.94  7823.1 1928.80  7888.0 1930.12
#Mann=14,-1,0
  2825.3    0.07       0  2992.8   0.045       0  5054.5   0.045       0
  5065.6   0.045       0  5339.5    0.07       0  5727.3   0.035       0
  6010.4    0.07       0  6601.2   0.035       0  6626.7    0.07       0
  6884.4   0.035       0  7049.5    0.07       0  7285.3   0.035       0
  7581.8    0.07       0  7823.1   0.035       0
Bank Sta=5054.5,5065.6
Exp/Cntr=0.3,0.1

Type RM Length L Ch R = 1,7794,1460,1460,1460
BEGIN DESCRIPTION:
Clear Fork Trib2_2 9.0
END DESCRIPTION:
XS GIS Cut Line= 3
      1413330.93      6981733.05      1411104.55      6980727.81
      1408365.59      6982245.22
#Sta/Elev= 30
  2557.2 1932.09  3797.4 1912.24  4864.1 1908.11  4990.7 1908.20  5057.2 1912.44
  5102.4 1909.40  5263.1 1910.24  5480.1 1909.82  5662.5 1909.62  5679.8 1906.95
  5680.3 1906.45  5691.0 1906.95  5734.9 1910.21  6177.0 1911.85  6315.3 1916.26
  6369.1 1914.31  6374.8 1912.09  6501.0 1913.66  7090.4 1913.45  7171.6 1916.76
  7198.7 1914.62  7238.9 1914.43  7308.8 1916.99  7379.0 1915.35  7442.9 1918.58
  7501.7 1916.92  7729.6 1918.64  7857.3 1920.89  7910.6 1920.64  8131.2 1923.67
#Mann=13,-1,0
  2557.2   0.045       0  5263.1   0.035       0  5480.1    0.07       0
  5679.8   0.045       0  5691.0    0.07       0  6501.0   0.035       0
  7198.7    0.07       0  7238.9   0.035       0  7379.0    0.07       0
  7501.7   0.035       0  7729.6    0.07       0  7857.3   0.035       0
  7910.6    0.07       0
Bank Sta=5679.8,5691
Exp/Cntr=0.3,0.1

Type RM Length L Ch R = 1,6334,1161,1161,1161
BEGIN DESCRIPTION:
Mapping XS ee881e5b
END DESCRIPTION:
XS GIS Cut Line= 3
      1411907.29      6978547.28      1410093.06      6980179.22
      1407967.18      6981593.58
#Sta/Elev= 30
  2597.1 1916.48  2740.8 1909.12  3008.5 1905.78  3229.6 1907.33  3273.0 1904.66
  3406.7 1903.88  3640.9 1904.49  3720.7 1904.65  3857.2 1905.50  3857.4 1905.50
  4041.2 1905.27  4312.7 1909.58  4399.0 1907.39  4579.9 1905.48  4641.6 1905.88
  4979.4 1904.63  5000.6 1901.48  5001.1 1900.98  5013.5 1901.48  5028.0 1904.23
  5301.1 1908.58  5424.3 1915.69  5670.8 1912.94  5965.3 1914.20  6007.9 1917.78
  6529.8 1915.10  6837.0 1913.64  6969.3 1918.09  7370.7 1920.52  7590.7 1922.38
#Mann=18,-1,0
  2597.1   0.045       0  3008.5   0.035       0  3273.0   0.045       0
  3406.7    0.07       0  3640.9   0.045       0  3720.7    0.07       0
  3857.2   0.045       0  3857.4    0.07       0  4041.2   0.045       0
  4399.0   0.035       0  4579.9   0.045       0  4641.6   0.035       0
  4979.4    0.07       0  5000.6    0.07       0  5013.5    0.07       0
  6529.8   0.035       0  6969.3    0.07       0  7370.7   0.035       0
Bank Sta=5000.6,5013.5
Exp/Cntr=0.3,0.1

Type RM Length L Ch R = 1,5173,1155,1155,1155
BEGIN DESCRIPTION:
Clear Fork Trib2_2 6.0
END DESCRIPTION:
XS GIS Cut Line= 3
      1411447.24      6978200.05      1409911.76      6979094.49
      1407819.35      6980508.69
#Sta/Elev= 30
  3223.0 1919.09  3261.2 1918.83  3919.2 1903.95  4538.7 1901.15  4695.0 1900.70
  4868.9 1899.63  4919.3 1902.05  4965.7 1898.54  4966.2 1898.04  4978.7 1898.54
  5008.2 1903.87  5071.7 1899.55  5253.5 1900.49  5329.1 1901.10  5714.3 1906.94
  5799.8 1909.68  5901.3 1905.76  6022.0 1910.15  6087.5 1907.16  6123.5 1909.31
  6273.8 1909.43  6519.5 1910.93  6800.1 1912.63  6856.3 1913.57  6968.1 1912.52
  7054.0 1912.77  7312.6 1915.80  7343.9 1915.90  7512.0 1916.52  7525.5 1916.75
#Mann=18,-1,0
  3223.0   0.035       0  3261.2   0.045       0  4538.7    0.07       0
  4695.0   0.035       0  4965.7   0.035       0  4978.7   0.035       0
  5253.5    0.07       0  5329.1   0.035       0  5714.3    0.07       0
  6273.8   0.035       0  6519.5    0.07       0  6800.1   0.035       0
  6856.3    0.07       0  6968.1   0.035       0  7054.0    0.07       0
  7312.6   0.035       0  7343.9    0.07       0  7512.0   0.035       0
Bank Sta=4965.7,4978.7
Exp/Cntr=0.3,0.1