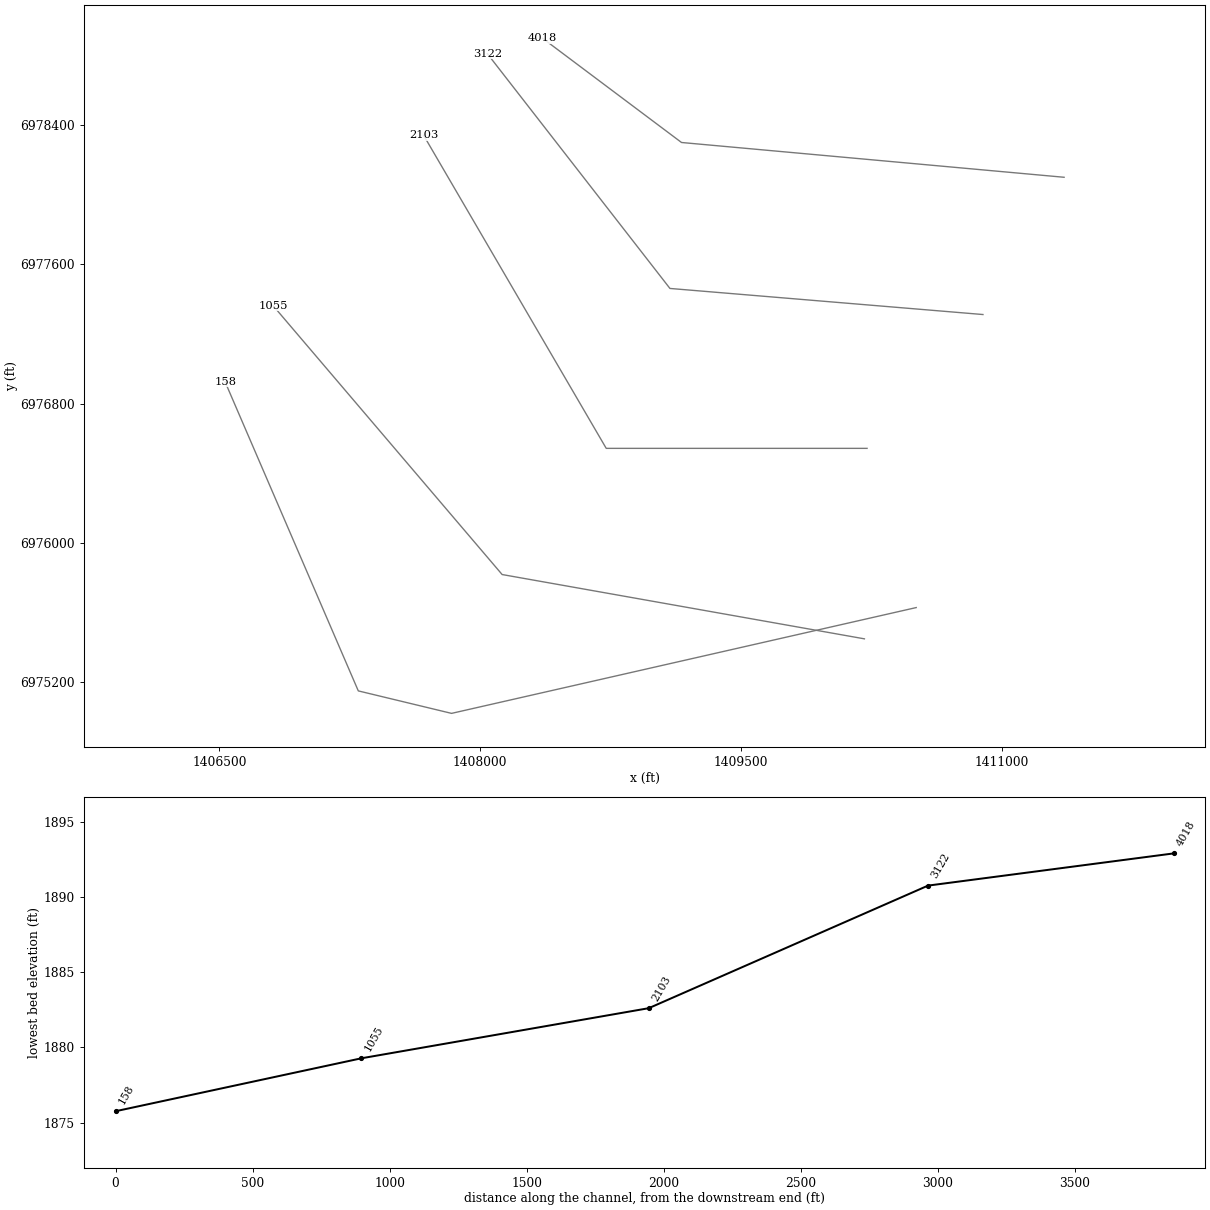
HEC-RAS study Clear Fork Trib2_2.prj: Clear Fork Trib2_2 Base Level Engineering

--- Clear Fork Trib2_2.g01 (geometry) --- (continued)

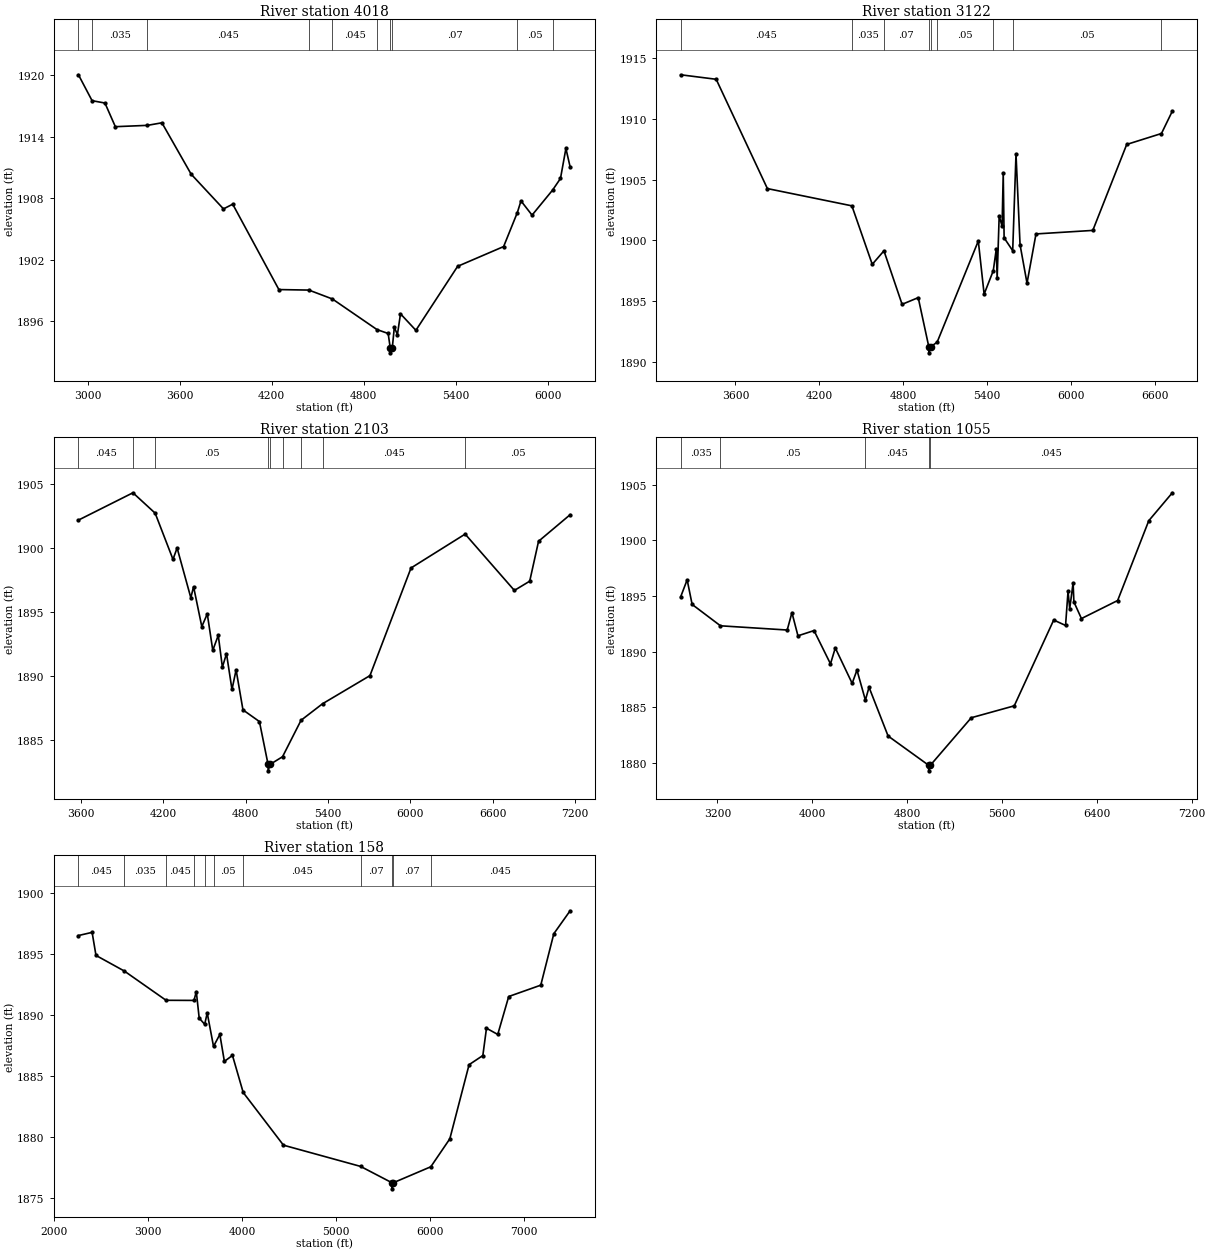
Type RM Length L Ch R = 1,4018,896,896,896
BEGIN DESCRIPTION:
Clear Fork Trib2_2 5.0
END DESCRIPTION:
XS GIS Cut Line= 3
      1411357.23      6978100.97      1409157.19      6978300.97
      1408358.56      6978899.94
#Sta/Elev= 30
  2939.4 1920.06  3028.4 1917.53  3112.3 1917.30  3180.2 1914.99  3389.7 1915.12
  3483.9 1915.37  3674.7 1910.35  3885.5 1906.96  3945.8 1907.42  4247.0 1899.08
  4442.9 1899.03  4596.2 1898.16  4887.1 1895.17  4959.9 1894.79  4973.2 1893.40
  4973.7 1892.90  4986.9 1893.40  5000.1 1895.40  5020.2 1894.68  5040.3 1896.71
  5140.7 1895.10  5413.0 1901.35  5713.0 1903.28  5802.5 1906.60  5826.3 1907.74
  5898.5 1906.35  6032.1 1908.79  6083.9 1909.93  6119.3 1912.86  6146.8 1911.07
#Mann=10,-1,0
  2939.4   0.045       0  3028.4   0.035       0  3389.7   0.045       0
  4442.9   0.035       0  4596.2   0.045       0  4887.1    0.07       0
  4973.2    0.07       0  4986.9    0.07       0  5802.5    0.05       0
  6032.1   0.035       0
Bank Sta=4973.2,4986.9
Exp/Cntr=0.3,0.1

Type RM Length L Ch R = 1,3122,1019,1019,1019
BEGIN DESCRIPTION:
Clear Fork Trib2_2 3.0
END DESCRIPTION:
XS GIS Cut Line= 3
      1410890.57      6977311.68      1409090.53      6977461.68
      1408040.56      6978811.65
#Sta/Elev= 30
  3208.0 1913.63  3462.1 1913.26  3828.3 1904.27  4432.7 1902.85  4578.3 1898.04
  4661.9 1899.15  4791.7 1894.75  4907.1 1895.30  4982.8 1891.26  4983.3 1890.76
  4996.7 1891.26  5042.5 1891.64  5336.8 1899.96  5378.4 1895.59  5443.8 1897.51
  5465.3 1899.29  5471.6 1896.89  5486.1 1902.02  5506.9 1901.18  5515.1 1905.53
  5521.4 1900.22  5582.8 1899.16  5606.4 1907.11  5635.4 1899.65  5685.2 1896.49
  5749.4 1900.54  6155.7 1900.83  6398.2 1907.90  6646.7 1908.80  6724.5 1910.64
#Mann=9,-1,0
  3208.0   0.045       0  4432.7   0.035       0  4661.9    0.07       0
  4982.8    0.07       0  4996.7    0.07       0  5042.5    0.05       0
  5443.8   0.045       0  5582.8    0.05       0  6646.7   0.035       0
Bank Sta=4982.8,4996.7
Exp/Cntr=0.3,0.1

Type RM Length L Ch R = 1,2103,1048,1048,1048
BEGIN DESCRIPTION:
Clear Fork Trib2_2 2.0
END DESCRIPTION:
XS GIS Cut Line= 3
      1410224.16      6976542.11      1408724.18      6976542.11
      1407674.20      6978342.06
#Sta/Elev= 30
  3581.1 1902.15  3978.4 1904.28  4140.3 1902.69  4270.3 1899.09  4300.3 1899.98
  4400.3 1896.10  4420.3 1896.96  4480.3 1893.85  4520.3 1894.84  4560.3 1892.00
  4600.3 1893.17  4630.3 1890.69  4660.3 1891.74  4700.3 1888.95  4730.3 1890.48
  4780.3 1887.36  4900.3 1886.45  4963.3 1883.11  4963.8 1882.61  4977.3 1883.11
  5068.8 1883.71  5203.7 1886.55  5360.6 1887.84  5705.9 1890.03  6005.3 1898.42
  6399.8 1901.06  6758.6 1896.67  6870.3 1897.39  6934.8 1900.50  7164.9 1902.57
#Mann=9,-1,0
  3581.1   0.045       0  3978.4   0.035       0  4140.3    0.05       0
  4963.3    0.05       0  4977.3    0.05       0  5068.8   0.045       0
  5203.7    0.05       0  5360.6   0.045       0  6399.8    0.05       0
Bank Sta=4963.3,4977.3
Exp/Cntr=0.3,0.1

Type RM Length L Ch R = 1,1055,897,897,897
BEGIN DESCRIPTION:
Mapping XS 6d3df698
END DESCRIPTION:
XS GIS Cut Line= 3
      1410208.92      6975446.74      1408125.63      6975816.52
      1406809.15      6977361.96
#Sta/Elev= 30
  2890.5 1894.91  2945.3 1896.44  2987.3 1894.23  3226.2 1892.31  3789.0 1891.93
  3828.9 1893.49  3879.6 1891.41  4015.1 1891.88  4153.9 1888.89  4194.5 1890.32
  4336.7 1887.14  4377.3 1888.33  4448.3 1885.63  4478.9 1886.79  4639.6 1882.41
  4981.9 1879.78  4982.4 1879.28  4996.0 1879.78  5341.1 1884.05  5703.5 1885.12
  6036.2 1892.83  6136.1 1892.34  6157.0 1895.41  6171.2 1893.85  6199.8 1896.17
  6206.4 1894.46  6270.0 1892.96  6575.3 1894.58  6837.8 1901.75  7036.5 1904.26
#Mann=5,-1,0
  2890.5   0.035       0  3226.2    0.05       0  4448.3   0.045       0
  4981.9   0.045       0  4996.0   0.045       0
Bank Sta=4981.9,4996
Exp/Cntr=0.3,0.1

Type RM Length L Ch R = 1,158,0,0,0
BEGIN DESCRIPTION:
Clear Fork Trib2_2 1.0
END DESCRIPTION:
XS GIS Cut Line= 4
      1410506.80      6975626.56      1407834.69      6975018.13
      1407298.49      6975147.40      1406532.49      6976924.47
#Sta/Elev= 30
  2259.5 1896.53  2404.9 1896.79  2446.0 1894.90  2747.1 1893.62  3191.0 1891.22
  3487.9 1891.21  3512.6 1891.93  3543.3 1889.76  3601.7 1889.25  3628.7 1890.18
  3695.6 1887.44  3762.9 1888.42  3811.0 1886.21  3897.1 1886.70  4011.2 1883.66
  4439.1 1879.34  5258.9 1877.60  5592.4 1876.26  5592.9 1875.76  5607.1 1876.26
  6005.7 1877.57  6207.8 1879.86  6412.5 1885.94  6558.9 1886.69  6597.6 1888.93
  6717.4 1888.42  6833.9 1891.53  7174.7 1892.46  7313.5 1896.68  7486.7 1898.56
#Mann=11,-1,0
  2259.5   0.045       0  2747.1   0.035       0  3191.0   0.045       0
  3487.9    0.05       0  3601.7   0.035       0  3695.6    0.05       0
  4011.2   0.045       0  5258.9    0.07       0  5592.4   0.045       0
  5607.1    0.07       0  6005.7   0.045       0
Bank Sta=5592.4,5607.1
Exp/Cntr=0.3,0.1

Chan Stop Cuts=-1