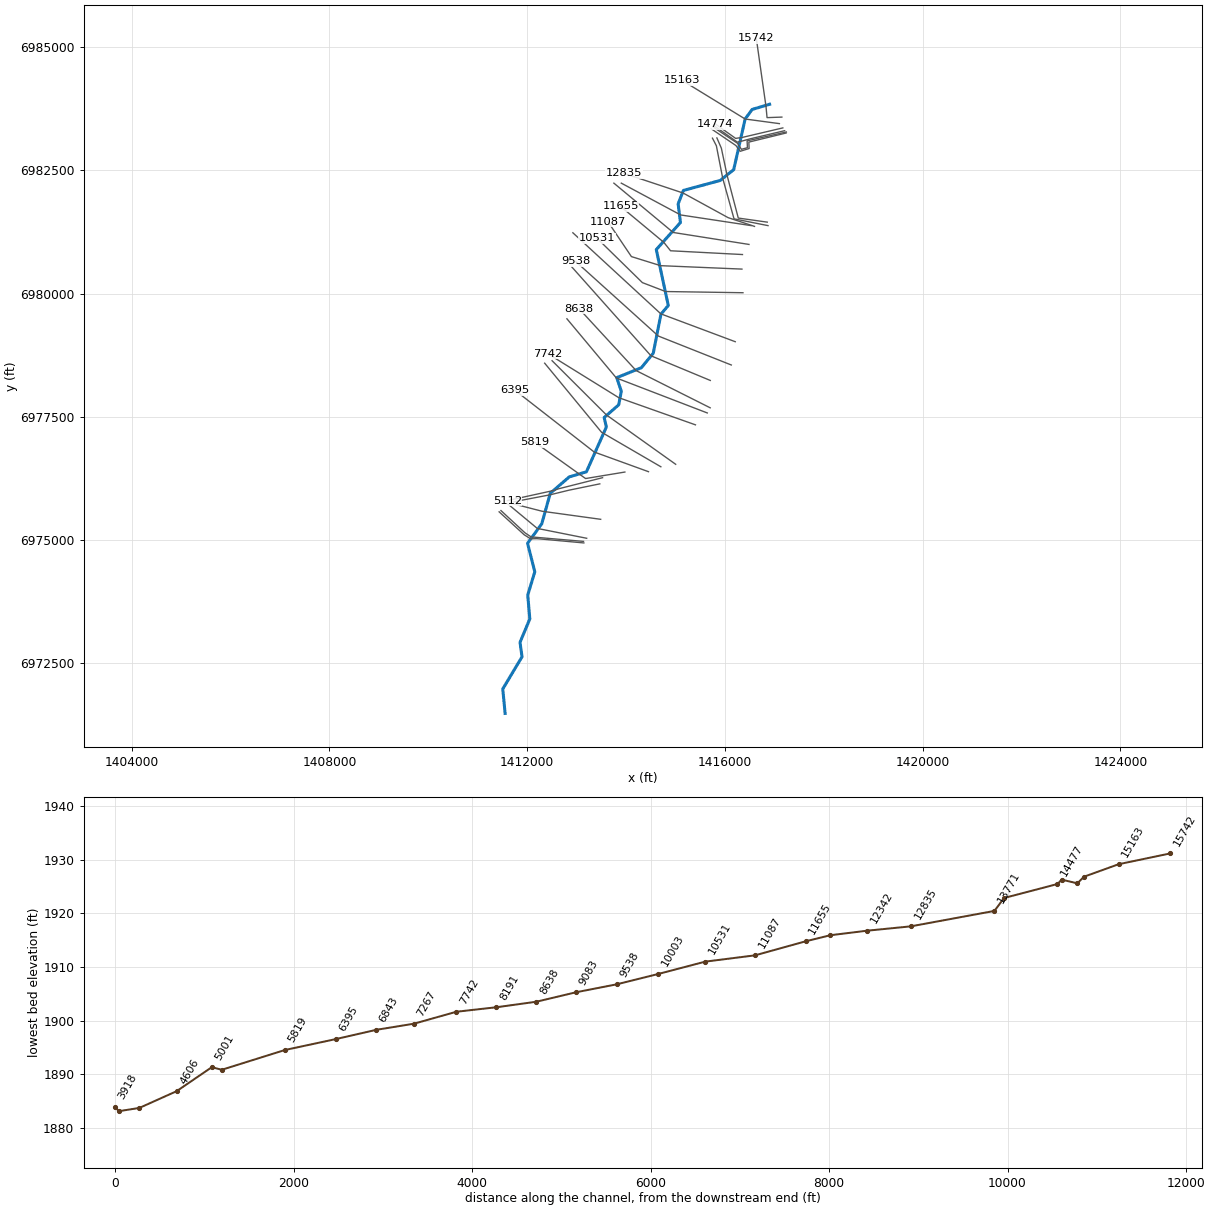
--- Clear Fork Trib2_3.prj (project) ---

Proj Title=Clear Fork Trib2_3 Base Level Engineering
Current Plan=p01
Default Exp/Contr=0.3,0.1
English Units
Geom File=g01
Flow File=f01
Plan File=p01
BEGIN DESCRIPTION:
Clear Fork Trib2_3
END DESCRIPTION:

--- Clear Fork Trib2_3.p01 (plan) ---

Plan Title=Multiple Run
Short Identifier=Multiple
Geom File=g01
Flow File=f01
Subcritical Flow
K Sum by GR= 0
Std Step Tol= 0.01
Critical Tol= 0.01
Num of Std Step Trials= 20
Max Error Tol= 0.3
Flow Tol Ratio= 0.001
Split Flow NTrial= 30
Split Flow Tol= 0.02
Split Flow Ratio= 0.02
Log Output Level= 0
Friction Slope Method= 1
Unsteady Friction Slope Method= 2
Unsteady Bridges Friction Slope Method= 1
Parabolic Critical Depth
Global Vel Dist=  1 , 1 , 1
Global Log Level= 0
CheckData=True
Encroach Param= -1, 0, 0, 0
BEGIN DESCRIPTION:
Multiple Run
END DESCRIPTION:

--- Clear Fork Trib2_3.f01 (steady flow) ---

Flow Title=Multiple
Number of Profiles=7
Profile Names=10-year,25-year,50-year,1pct_min,100-year,1pct_plu,500-year
River Rch & RM= Clear Fork Trib2,Reach-1,15742
     170     230     278     168     335     668     490
River Rch & RM= Clear Fork Trib2,Reach-1,15163
     278     389     480     295     588    1174     895
River Rch & RM= Clear Fork Trib2,Reach-1,12835
     356     504     628     388     774    1545    1194
River Rch & RM= Clear Fork Trib2,Reach-1,8638
     474     680     854     533    1063    2120    1666
River Rch & RM= Clear Fork Trib2,Reach-1,3182
     506     727     916     572    1141    2277    1796
Boundary for River Rch & Prof#=Clear Fork Trib2,Reach-1,1
Up Type=0
Dn Type=3
Dn Slope=0.005
Boundary for River Rch & Prof#=Clear Fork Trib2,Reach-1,2
Up Type=0
Dn Type=3
Dn Slope=0.005
Boundary for River Rch & Prof#=Clear Fork Trib2,Reach-1,3
Up Type=0
Dn Type=3
Dn Slope=0.005
Boundary for River Rch & Prof#=Clear Fork Trib2,Reach-1,4
Up Type=0
Dn Type=3
Dn Slope=0.005
Boundary for River Rch & Prof#=Clear Fork Trib2,Reach-1,5
Up Type=0
Dn Type=3
Dn Slope=0.005
Boundary for River Rch & Prof#=Clear Fork Trib2,Reach-1,6
Up Type=0
Dn Type=3
Dn Slope=0.005
Boundary for River Rch & Prof#=Clear Fork Trib2,Reach-1,7
Up Type=0
Dn Type=3
Dn Slope=0.005

--- Clear Fork Trib2_3.g01 (geometry) ---

Geom Title=Existing Conditions

River Reach=Clear Fork Trib2,Reach-1
Reach XY= 30
      1416905.00      6983838.00      1416552.33      6983732.58
      1416410.48      6983540.44      1416178.83      6982511.13
      1415903.45      6982291.75      1415160.82      6982090.31
      1415055.05      6981817.96      1415101.25      6981439.55
      1414612.79      6980891.42      1414855.40      6979758.13
      1414707.06      6979582.15      1414551.24      6978789.56
      1414311.06      6978496.14      1413812.36      6978294.34
      1413905.10      6978017.90      1413852.93      6977743.86
      1413558.12      6977486.38      1413603.04      6977293.89
      1413199.48      6976385.56      1412852.55      6976282.54
      1412468.62      6975951.22      1412295.86      6975331.25
      1412008.67      6974936.42      1412155.40      6974358.11
      1412012.56      6973888.00      1412054.49      6973403.21
      1411856.22      6972927.50      1411896.96      6972634.68
      1411507.24      6971982.07      1411555.00      6971488.00

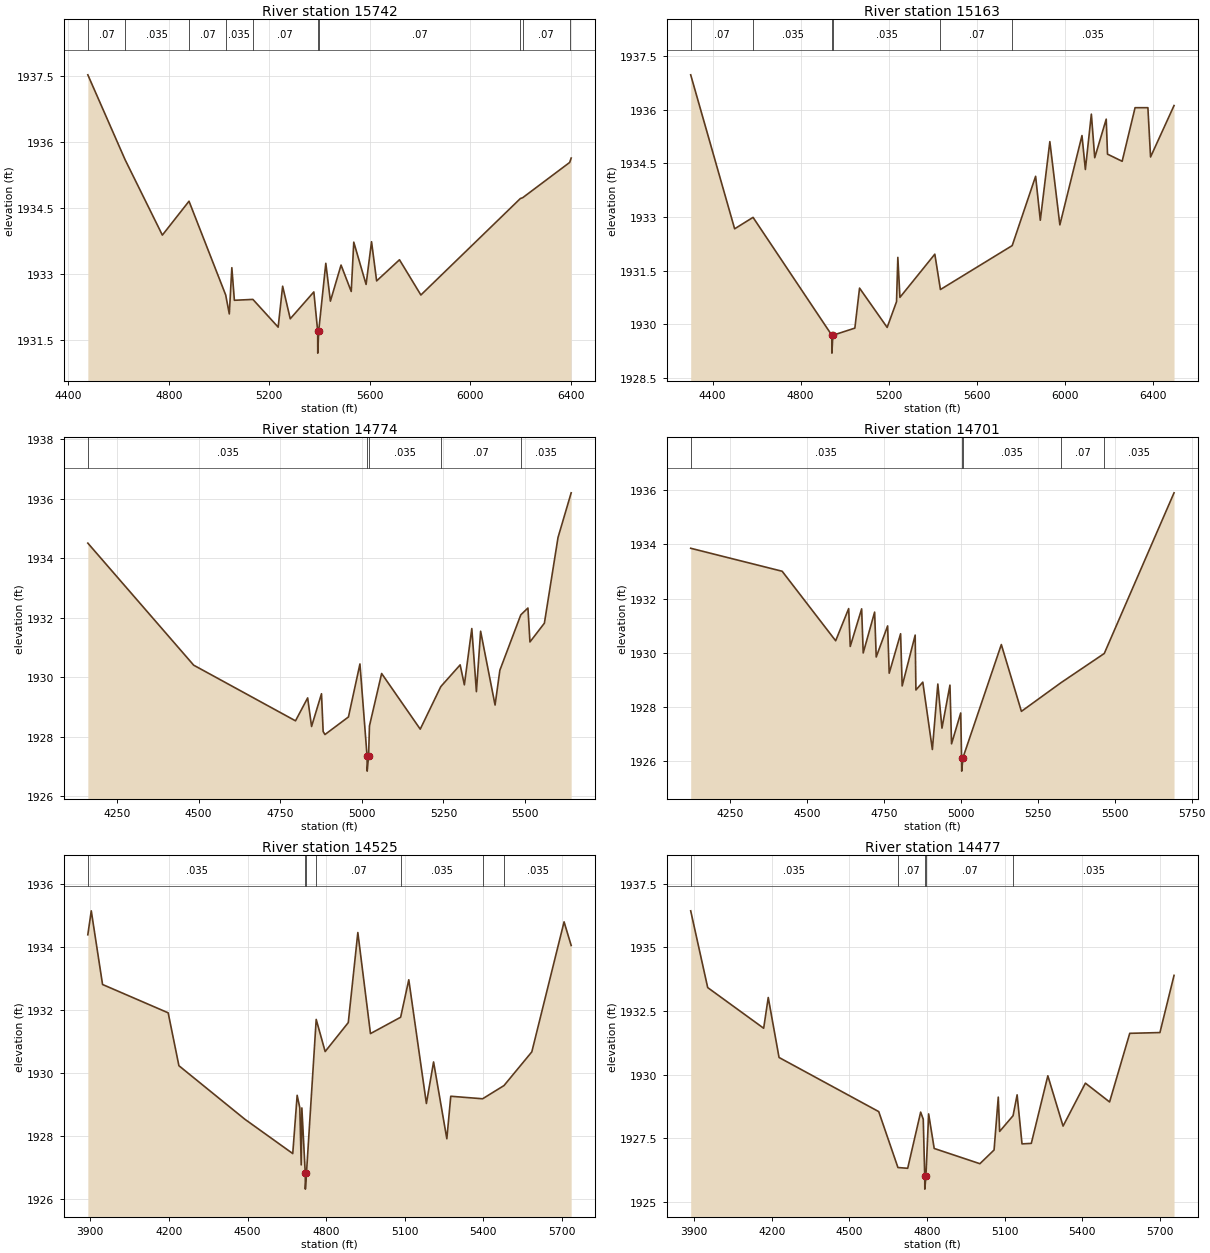
Type RM Length L Ch R = 1,15742,579,579,579
BEGIN DESCRIPTION:
Mapping XS c39c8622
END DESCRIPTION:
XS GIS Cut Line= 4
      1417152.88      6983577.27      1416853.39      6983566.42
      1416831.69      6983794.28      1416635.97      6985174.08
#Sta/Elev= 30
  4478.2 1937.53  4626.6 1935.60  4774.6 1933.89  4880.6 1934.66  5026.5 1932.53
  5040.8 1932.10  5050.9 1933.15  5061.0 1932.41  5134.7 1932.43  5235.1 1931.80
  5252.9 1932.73  5283.2 1931.99  5377.0 1932.60  5392.3 1931.71  5392.6 1931.21
  5396.3 1931.71  5424.6 1933.25  5442.9 1932.39  5485.2 1933.21  5525.7 1932.61
  5535.8 1933.73  5584.8 1932.77  5606.5 1933.74  5626.7 1932.85  5717.6 1933.33
  5802.7 1932.53  6198.2 1934.72  6207.7 1934.74  6394.4 1935.54  6400.4 1935.64
#Mann=10,-1,0
  4478.2    0.07       0  4626.6   0.035       0  4880.6    0.07       0
  5026.5   0.035       0  5134.7    0.07       0  5392.3    0.07       0
  5396.3    0.07       0  6198.2   0.035       0  6207.7    0.07       0
  6394.4   0.035       0
Bank Sta=5392.3,5396.3
Exp/Cntr=0.3,0.1

Type RM Length L Ch R = 1,15163,389,389,389
BEGIN DESCRIPTION:
Mapping XS 99b24ff3
END DESCRIPTION:
XS GIS Cut Line= 3
      1417102.95      6983444.89      1416410.68      6983538.20
      1415134.10      6984322.33
#Sta/Elev= 30
  4300.3 1936.98  4500.0 1932.67  4583.7 1932.99  4941.8 1929.69  4942.1 1929.19
  4946.3 1929.69  5046.4 1929.89  5067.7 1931.01  5193.2 1929.91  5235.8 1930.63
  5241.7 1931.87  5251.2 1930.75  5409.8 1931.96  5435.3 1930.97  5761.5 1932.20
  5867.9 1934.14  5889.2 1932.91  5932.6 1935.11  5978.1 1932.78  6078.6 1935.28
  6094.0 1934.33  6121.2 1935.88  6136.6 1934.66  6188.8 1935.74  6194.6 1934.76
  6261.2 1934.56  6319.9 1936.06  6378.2 1936.06  6390.3 1934.68  6497.0 1936.12
#Mann=6,-1,0
  4300.3    0.07       0  4583.7   0.035       0  4941.8   0.035       0
  4946.3   0.035       0  5435.3    0.07       0  5761.5   0.035       0
Bank Sta=4941.8,4946.3
Exp/Cntr=0.3,0.1

Type RM Length L Ch R = 1,14774,73,73,73
BEGIN DESCRIPTION:
Mapping XS 8949e64d
END DESCRIPTION:
XS GIS Cut Line= 4
      1417172.36      6983358.07      1416360.77      6983167.11
      1416217.54      6983145.41      1415808.65      6983437.47
#Sta/Elev= 30
  4160.4 1934.51  4484.7 1930.41  4796.8 1928.54  4834.0 1929.31  4846.0 1928.35
  4876.4 1929.45  4881.5 1928.18  4887.1 1928.08  4959.0 1928.67  4994.2 1930.45
  5016.1 1927.35  5016.4 1926.85  5020.7 1927.35  5023.4 1928.37  5060.7 1930.13
  5179.0 1928.26  5242.0 1929.69  5301.3 1930.42  5314.2 1929.75  5337.0 1931.64
  5351.1 1929.52  5364.0 1931.55  5408.3 1929.07  5423.0 1930.24  5487.1 1932.10
  5509.0 1932.33  5515.2 1931.19  5559.4 1931.82  5601.2 1934.70  5641.5 1936.20
#Mann=5,-1,0
  4160.4   0.035       0  5016.1   0.035       0  5020.7   0.035       0
  5242.0    0.07       0  5487.1   0.035       0
Bank Sta=5016.1,5020.7
Exp/Cntr=0.3,0.1

Type RM Length L Ch R = 1,14701,176,176,176
BEGIN DESCRIPTION:
Mapping XS abb17dcd
END DESCRIPTION:
XS GIS Cut Line= 5
      1417209.32      6983301.67      1416495.31      6983132.39
      1416362.94      6983095.50      1416252.26      6983069.45
      1415772.63      6983408.02
#Sta/Elev= 30
  4120.7 1933.86  4418.2 1933.01  4592.2 1930.44  4634.5 1931.63  4639.6 1930.23
  4676.7 1931.62  4681.8 1929.99  4718.9 1931.50  4724.1 1929.84  4761.2 1930.99
  4766.3 1929.24  4803.4 1930.70  4808.5 1928.77  4850.8 1930.65  4853.2 1928.62
  4875.6 1928.91  4906.7 1926.42  4924.5 1928.84  4937.9 1927.21  4963.9 1928.80
  4969.1 1926.63  4998.9 1927.77  5001.7 1926.12  5002.1 1925.62  5006.3 1926.12
  5131.0 1930.30  5196.3 1927.83  5325.1 1928.89  5465.8 1929.97  5692.7 1935.91
#Mann=5,-1,0
  4120.7   0.035       0  5001.7   0.035       0  5006.3   0.035       0
  5325.1    0.07       0  5465.8   0.035       0
Bank Sta=5001.7,5006.3
Exp/Cntr=0.3,0.1

Type RM Length L Ch R = 1,14525,48,48,48
BEGIN DESCRIPTION:
Mapping XS e4f1d5bc
END DESCRIPTION:
XS GIS Cut Line= 6
      1417244.00      6983275.62      1416449.74      6983095.50
      1416456.25      6982956.61      1416334.72      6982924.06
      1416256.60      6983045.58      1415758.71      6983378.95
#Sta/Elev= 30
  3890.6 1934.39  3903.7 1935.15  3946.8 1932.81  4197.2 1931.91  4238.2 1930.23
  4489.8 1928.53  4672.6 1927.44  4689.4 1929.29  4699.6 1928.89  4704.9 1927.08
  4707.4 1928.89  4720.3 1926.81  4720.7 1926.31  4724.9 1926.81  4762.1 1931.70
  4796.3 1930.68  4884.5 1931.60  4921.0 1934.46  4969.2 1931.25  5084.3 1931.77
  5115.4 1932.96  5182.6 1929.03  5210.0 1930.35  5260.6 1927.91  5275.6 1929.26
  5397.2 1929.18  5478.8 1929.60  5584.9 1930.67  5708.0 1934.80  5735.1 1934.05
#Mann=7,-1,0
  3890.6   0.035       0  4720.3    0.07       0  4724.9   0.035       0
  4762.1    0.07       0  5084.3   0.035       0  5397.2    0.07       0
  5478.8   0.035       0
Bank Sta=4720.3,4724.9
Exp/Cntr=0.3,0.1

Type RM Length L Ch R = 1,14477,598,598,598
BEGIN DESCRIPTION:
Mapping XS 98ab30c3
END DESCRIPTION:
XS GIS Cut Line= 6
      1417238.84      6983254.68      1416485.21      6983070.46
      1416490.11      6982940.01      1416309.99      6982883.58
      1416223.18      6983000.77      1415721.85      6983341.50
#Sta/Elev= 30
  3887.3 1936.44  3953.0 1933.42  4169.2 1931.82  4186.9 1933.03  4228.6 1930.67
  4613.7 1928.54  4687.9 1926.34  4725.6 1926.31  4775.7 1928.52  4785.7 1928.24
  4791.4 1925.99  4791.7 1925.49  4796.0 1925.99  4806.5 1928.45  4828.0 1927.09
  5004.5 1926.49  5059.3 1927.03  5075.5 1929.11  5080.8 1927.76  5132.7 1928.38
  5148.3 1929.20  5167.2 1927.27  5203.1 1927.29  5267.0 1929.95  5325.8 1927.97
  5412.1 1929.66  5505.5 1928.92  5583.4 1931.62  5700.0 1931.65  5754.5 1933.90
#Mann=5,-1,0
  3887.3   0.035       0  4687.9    0.07       0  4791.4    0.07       0
  4796.0    0.07       0  5132.7   0.035       0
Bank Sta=4791.4,4796
Exp/Cntr=0.3,0.1

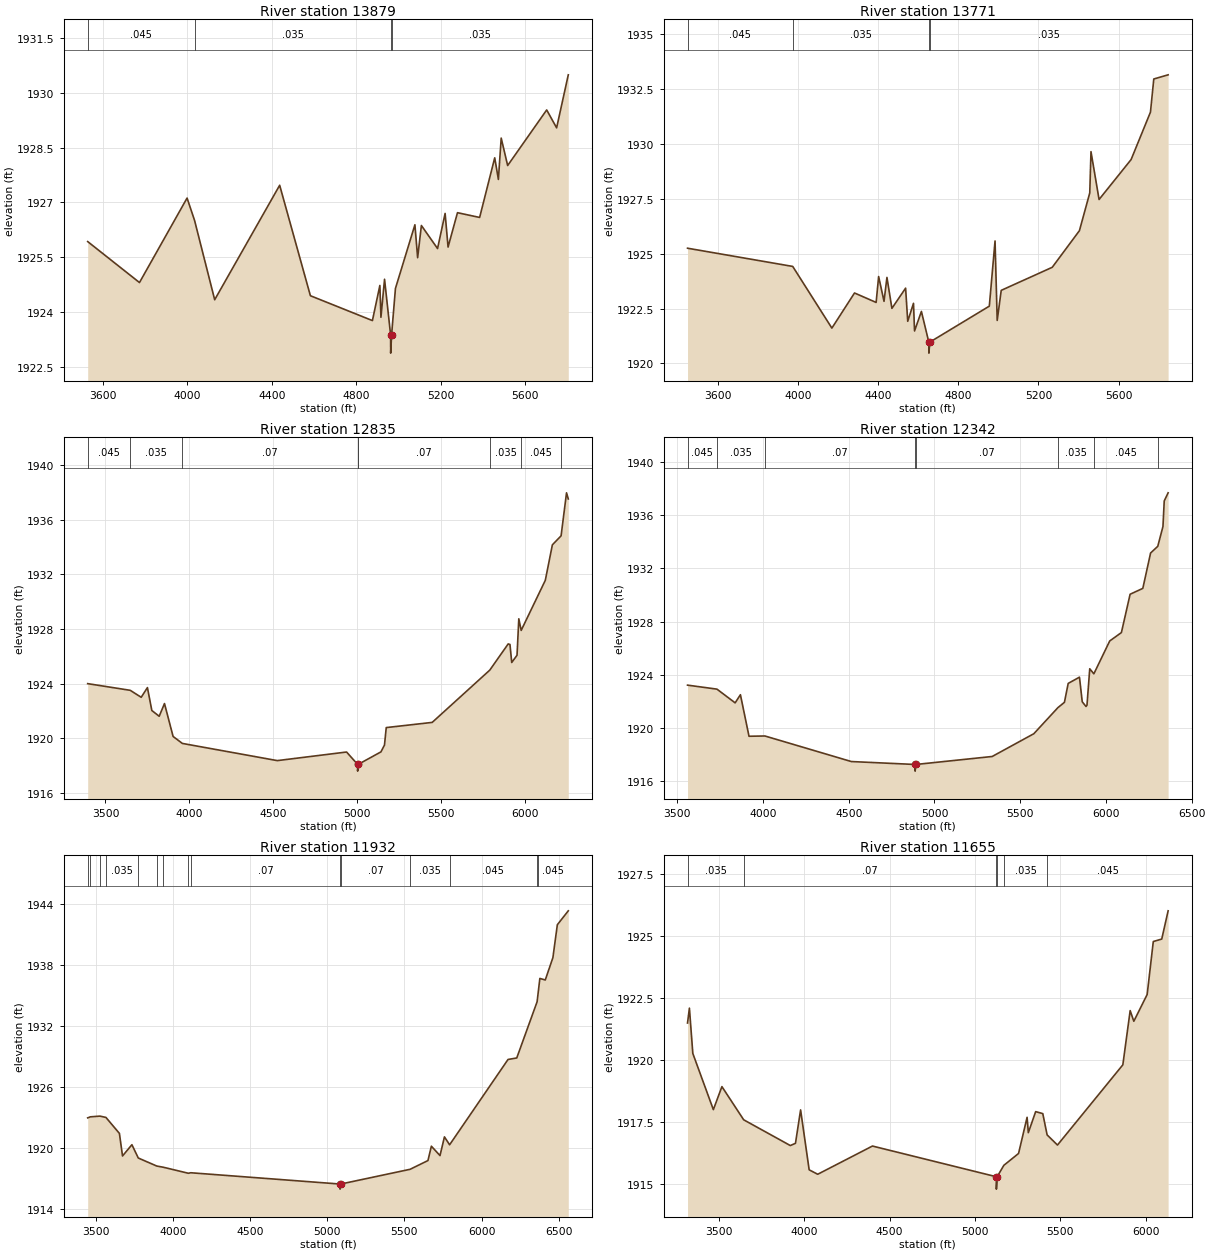
Type RM Length L Ch R = 1,13879,108,108,108
BEGIN DESCRIPTION:
Mapping XS e7f1565e
END DESCRIPTION:
XS GIS Cut Line= 5
      1416858.03      6981447.42      1416271.36      6981530.26
      1416046.96      6982387.92      1415928.91      6982946.95
      1415838.64      6983155.26
#Sta/Elev= 30
  3527.8 1925.93  3773.2 1924.81  3998.7 1927.12  4034.2 1926.51  4129.6 1924.34
  4437.5 1927.47  4583.1 1924.45  4877.0 1923.77  4912.3 1924.73  4917.4 1923.86
  4934.5 1924.90  4963.2 1923.38  4963.6 1922.88  4967.9 1923.38  4986.2 1924.65
  5078.4 1926.39  5091.3 1925.49  5109.1 1926.37  5185.7 1925.74  5221.5 1926.70
  5235.5 1925.78  5280.1 1926.72  5385.1 1926.59  5456.6 1928.22  5474.0 1927.63
  5487.3 1928.76  5517.9 1928.01  5702.9 1929.53  5749.9 1929.04  5805.2 1930.49
#Mann=4,-1,0
  3527.8   0.045       0  4034.2   0.035       0  4963.2   0.035       0
  4967.9   0.035       0
Bank Sta=4963.2,4967.9
Exp/Cntr=0.3,0.1

Type RM Length L Ch R = 1,13771,936,936,936
BEGIN DESCRIPTION:
Mapping XS bedb1a4e
END DESCRIPTION:
XS GIS Cut Line= 5
      1416872.92      6981376.86      1416185.29      6981514.19
      1415956.69      6982335.84      1415828.21      6982995.56
      1415749.16      6983150.24
#Sta/Elev= 30
  3447.9 1925.25  3973.2 1924.42  4168.7 1921.61  4281.8 1923.21  4389.7 1922.78
  4402.2 1923.96  4429.1 1922.83  4443.7 1923.92  4468.5 1922.51  4536.9 1923.43
  4547.5 1921.92  4576.3 1922.74  4581.5 1921.48  4615.8 1922.37  4652.8 1920.97
  4653.2 1920.47  4657.5 1920.97  4954.9 1922.61  4983.5 1925.58  4994.3 1921.96
  5014.4 1923.33  5269.1 1924.38  5404.9 1926.05  5456.5 1927.77  5462.6 1929.65
  5503.0 1927.47  5663.0 1929.29  5759.6 1931.45  5776.2 1932.96  5847.8 1933.15
#Mann=4,-1,0
  3447.9   0.045       0  3973.2   0.035       0  4652.8   0.035       0
  4657.5   0.035       0
Bank Sta=4652.8,4657.5
Exp/Cntr=0.3,0.1

Type RM Length L Ch R = 1,12835,493,493,493
BEGIN DESCRIPTION:
Clear Fork Trib2_3 23.0
END DESCRIPTION:
XS GIS Cut Line= 4
      1416599.74      6981361.43      1416065.93      6981538.49
      1415155.00      6982038.00      1413955.01      6982438.00
#Sta/Elev= 30
  3394.1 1924.00  3647.9 1923.51  3713.3 1923.00  3750.3 1923.71  3776.7 1922.03
  3820.5 1921.61  3852.1 1922.54  3903.4 1920.13  3958.7 1919.62  4524.8 1918.36
  4938.0 1918.99  5003.5 1918.09  5003.9 1917.59  5008.3 1918.09  5143.0 1919.00
  5164.1 1919.50  5174.6 1920.78  5448.7 1921.16  5792.1 1924.99  5901.9 1926.91
  5912.5 1926.87  5923.0 1925.55  5954.6 1926.08  5965.2 1928.75  5979.4 1927.90
  6123.3 1931.57  6165.4 1934.17  6217.4 1934.83  6249.8 1937.98  6260.3 1937.53
#Mann=8,-1,0
  3394.1   0.045       0  3647.9   0.035       0  3958.7    0.07       0
  5003.5    0.07       0  5008.3    0.07       0  5792.1   0.035       0
  5979.4   0.045       0  6217.4    0.07       0
Bank Sta=5003.5,5008.3
Exp/Cntr=0.3,0.1

Type RM Length L Ch R = 1,12342,410,410,410
BEGIN DESCRIPTION:
Clear Fork Trib2_3 22.0
END DESCRIPTION:
XS GIS Cut Line= 3
      1416529.61      6981377.51      1415105.45      6981593.18
      1413904.97      6982238.02
#Sta/Elev= 30
  3559.6 1923.23  3731.2 1922.93  3837.3 1921.90  3868.1 1922.51  3918.2 1919.39
  4011.1 1919.41  4515.0 1917.49  4886.7 1917.27  4887.1 1916.77  4891.6 1917.27
  5336.6 1917.87  5579.4 1919.58  5719.9 1921.54  5757.9 1921.94  5779.8 1923.36
  5845.6 1923.83  5861.8 1921.98  5883.7 1921.63  5889.4 1921.72  5905.6 1924.46
  5929.5 1924.08  6022.1 1926.55  6090.2 1927.18  6141.0 1930.06  6215.1 1930.50
  6260.5 1933.16  6302.3 1933.66  6332.6 1935.15  6340.0 1937.07  6362.7 1937.68
#Mann=8,-1,0
  3559.6   0.045       0  3731.2   0.035       0  4011.1    0.07       0
  4886.7    0.07       0  4891.6    0.07       0  5719.9   0.035       0
  5929.5   0.045       0  6302.3    0.07       0
Bank Sta=4886.7,4891.6
Exp/Cntr=0.3,0.1

Type RM Length L Ch R = 1,11932,277,277,277
BEGIN DESCRIPTION:
Clear Fork Trib2_3 21.0
END DESCRIPTION:
XS GIS Cut Line= 3
      1416487.97      6980995.56      1414955.00      6981238.00
      1413754.98      6982238.02
#Sta/Elev= 30
  3448.0 1922.94  3465.6 1923.04  3527.5 1923.11  3566.3 1922.98  3653.5 1921.41
  3673.7 1919.19  3734.5 1920.30  3775.8 1918.99  3895.7 1918.20  3938.9 1918.08
  4100.4 1917.49  4116.1 1917.54  5082.8 1916.43  5083.2 1915.93  5087.7 1916.43
  5537.1 1917.88  5652.8 1918.74  5675.0 1920.15  5730.9 1919.23  5759.6 1921.07
  5793.1 1920.29  6171.6 1928.68  6228.2 1928.83  6360.1 1934.36  6364.2 1934.89
  6377.9 1936.65  6413.0 1936.50  6462.5 1938.70  6491.1 1941.93  6562.1 1943.30
#Mann=15,-1,0
  3448.0    0.07       0  3465.6   0.035       0  3527.5    0.07       0
  3566.3   0.035       0  3775.8    0.07       0  3895.7   0.035       0
  3938.9    0.07       0  4100.4   0.035       0  4116.1    0.07       0
  5082.8    0.07       0  5087.7    0.07       0  5537.1   0.035       0
  5793.1   0.045       0  6360.1    0.07       0  6364.2   0.045       0
Bank Sta=5082.8,5087.7
Exp/Cntr=0.3,0.1

Type RM Length L Ch R = 1,11655,568,568,568
BEGIN DESCRIPTION:
Mapping XS ea865992
END DESCRIPTION:
XS GIS Cut Line= 4
      1416356.00      6980790.70      1414901.13      6980867.09
      1414765.71      6981037.23      1413890.73      6981766.38
#Sta/Elev= 30
  3317.5 1921.50  3328.5 1922.10  3348.5 1920.27  3468.7 1918.00  3518.8 1918.93
  3646.2 1917.59  3919.3 1916.55  3949.4 1916.64  3979.4 1917.99  4029.5 1915.57
  4079.6 1915.39  4400.0 1916.53  5125.2 1915.29  5125.5 1914.79  5130.1 1915.29
  5169.0 1915.75  5255.2 1916.23  5305.2 1917.69  5312.5 1917.07  5355.4 1917.92
  5397.1 1917.84  5422.5 1916.98  5483.0 1916.57  5865.7 1919.81  5908.6 1922.00
  5930.0 1921.57  6008.1 1922.65  6044.0 1924.79  6093.5 1924.89  6130.8 1926.03
#Mann=6,-1,0
  3317.5   0.035       0  3646.2    0.07       0  5125.2    0.07       0
  5130.1    0.07       0  5169.0   0.035       0  5422.5   0.045       0
Bank Sta=5125.2,5130.1
Exp/Cntr=0.3,0.1

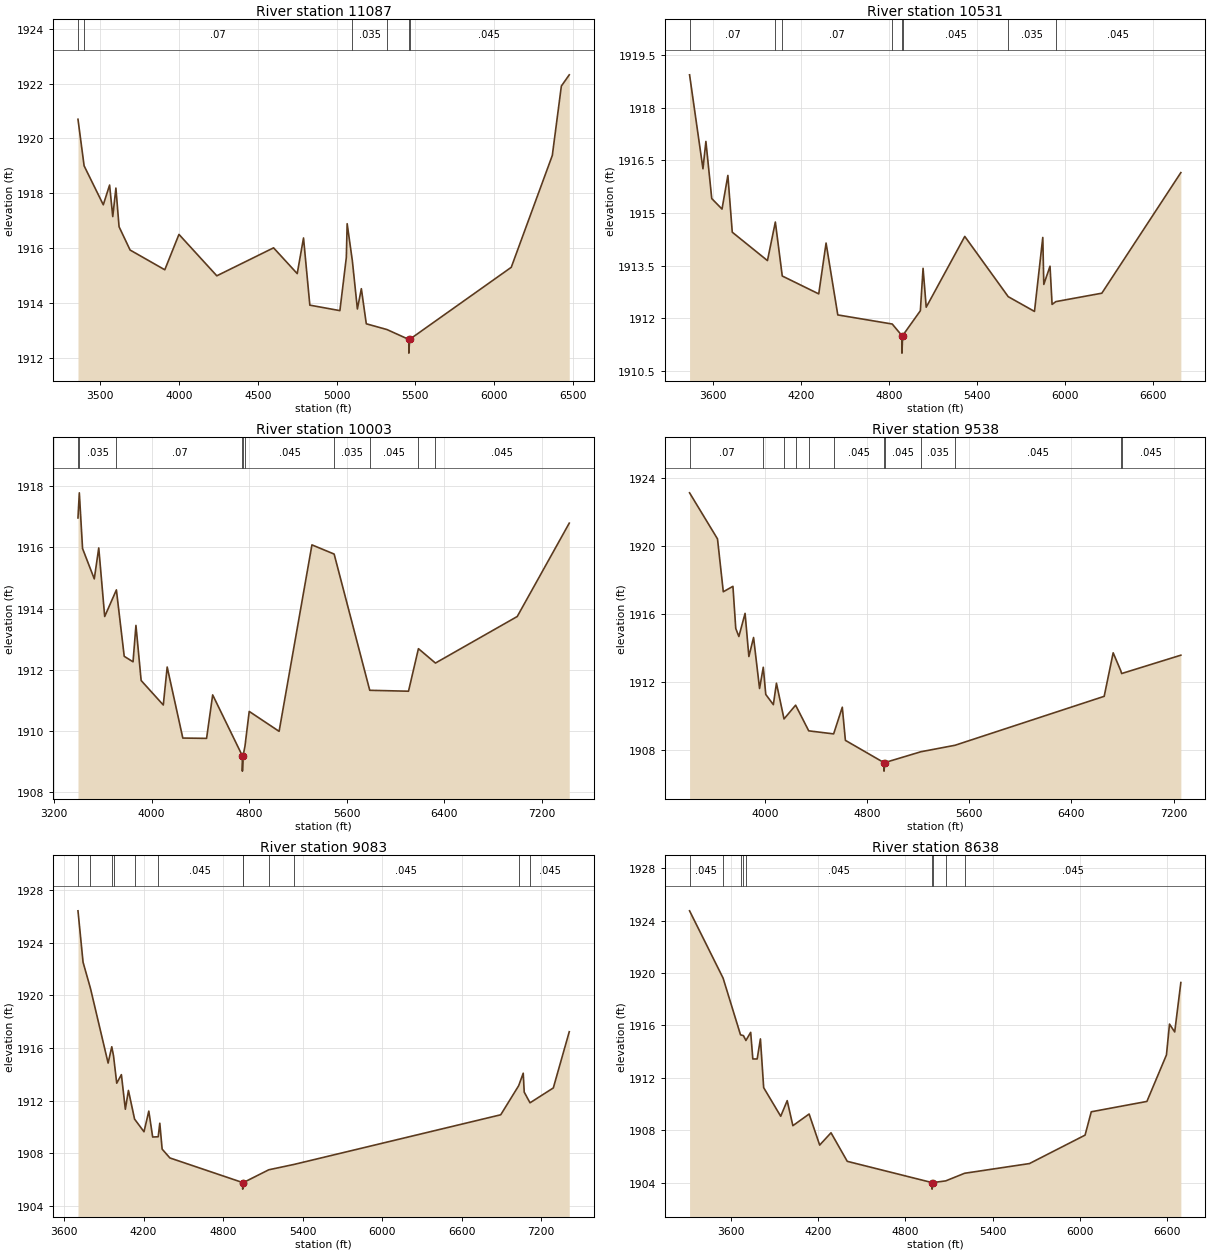
Type RM Length L Ch R = 1,11087,556,556,556
BEGIN DESCRIPTION:
Mapping XS 8c800033
END DESCRIPTION:
XS GIS Cut Line= 4
      1416345.56      6980495.56      1414699.74      6980565.01
      1414109.46      6980749.03      1413633.78      6981457.34
#Sta/Elev= 30
  3358.2 1920.70  3397.2 1919.00  3518.9 1917.58  3558.9 1918.30  3579.0 1917.15
  3599.0 1918.19  3619.0 1916.78  3689.1 1915.93  3909.3 1915.21  3999.3 1916.50
  4239.5 1914.99  4599.9 1916.01  4750.0 1915.07  4790.0 1916.37  4830.1 1913.92
  5020.9 1913.72  5061.8 1915.66  5067.0 1916.89  5100.0 1915.54  5132.0 1913.78
  5157.1 1914.52  5188.5 1913.24  5319.6 1913.03  5458.4 1912.67  5458.7 1912.17
  5463.4 1912.67  6108.8 1915.30  6369.4 1919.38  6426.8 1921.91  6477.0 1922.32
#Mann=6,-1,0
  3358.2   0.035       0  3397.2    0.07       0  5100.0   0.035       0
  5319.6   0.045       0  5458.4    0.07       0  5463.4   0.045       0
Bank Sta=5458.4,5463.4
Exp/Cntr=0.3,0.1

Type RM Length L Ch R = 1,10531,528,528,528
BEGIN DESCRIPTION:
Mapping XS ceaa91c1
END DESCRIPTION:
XS GIS Cut Line= 4
      1416366.41      6980016.39      1414800.44      6980040.70
      1414331.69      6980221.26      1413415.04      6981120.54
#Sta/Elev= 30
  3438.8 1918.94  3530.2 1916.26  3550.2 1917.04  3590.2 1915.41  3660.2 1915.11
  3700.2 1916.07  3730.2 1914.45  3970.3 1913.64  4024.1 1914.74  4071.4 1913.20
  4320.3 1912.69  4370.3 1914.14  4450.3 1912.09  4821.9 1911.83  4887.9 1911.50
  4888.2 1911.00  4892.9 1911.50  5013.8 1912.21  5032.2 1913.42  5053.7 1912.31
  5316.8 1914.33  5613.5 1912.61  5792.6 1912.19  5849.2 1914.30  5856.2 1912.96
  5898.6 1913.48  5912.7 1912.39  5938.7 1912.47  6252.2 1912.71  6791.4 1916.15
#Mann=8,-1,0
  3438.8    0.07       0  4024.1   0.035       0  4071.4    0.07       0
  4821.9   0.045       0  4887.9   0.045       0  4892.9   0.045       0
  5613.5   0.035       0  5938.7   0.045       0
Bank Sta=4887.9,4892.9
Exp/Cntr=0.3,0.1

Type RM Length L Ch R = 1,10003,465,465,465
BEGIN DESCRIPTION:
Clear Fork Trib2_3 19.0
END DESCRIPTION:
XS GIS Cut Line= 3
      1416210.20      6979023.32      1414705.00      6979588.00
      1412925.46      6981231.65
#Sta/Elev= 30
  3396.2 1916.96  3407.2 1917.78  3433.8 1915.96  3529.9 1914.97  3566.7 1915.98
  3615.4 1913.74  3711.3 1914.61  3775.6 1912.44  3847.9 1912.26  3871.7 1913.45
  3914.4 1911.65  4096.0 1910.85  4128.0 1912.09  4256.2 1909.77  4451.2 1909.76
  4501.1 1911.18  4744.6 1909.19  4745.0 1908.69  4750.5 1909.19  4765.9 1909.50
  4800.9 1910.64  5046.1 1909.99  5315.4 1916.08  5497.5 1915.78  5789.7 1911.33
  6107.6 1911.30  6189.0 1912.69  6328.6 1912.22  6999.5 1913.74  7426.3 1916.79
#Mann=10,-1,0
  3396.2    0.07       0  3407.2   0.035       0  3711.3    0.07       0
  4744.6   0.045       0  4750.5    0.07       0  4765.9   0.045       0
  5497.5   0.035       0  5789.7   0.045       0  6189.0   0.035       0
  6328.6   0.045       0
Bank Sta=4744.6,4750.5
Exp/Cntr=0.3,0.1

Type RM Length L Ch R = 1,9538,455,455,455
BEGIN DESCRIPTION:
Clear Fork Trib2_3 18.0
END DESCRIPTION:
XS GIS Cut Line= 3
      1416130.31      6978551.11      1414655.00      6979138.00
      1412981.01      6980651.79
#Sta/Elev= 30
  3411.8 1923.13  3630.4 1920.42  3675.8 1917.31  3751.1 1917.63  3773.3 1915.15
  3797.6 1914.68  3846.2 1916.04  3875.9 1913.50  3912.6 1914.62  3959.5 1911.62
  3988.7 1912.87  4008.1 1911.27  4067.4 1910.67  4091.7 1911.93  4151.0 1909.83
  4241.7 1910.64  4344.3 1909.13  4539.2 1908.95  4607.0 1910.52  4631.3 1908.57
  4933.1 1907.26  4933.6 1906.76  4939.1 1907.26  5222.0 1907.90  5488.8 1908.28
  6656.5 1911.16  6726.8 1913.72  6786.6 1912.66  6793.2 1912.50  7256.5 1913.58
#Mann=12,-1,0
  3411.8    0.07       0  3988.7   0.035       0  4151.0    0.07       0
  4241.7   0.045       0  4344.3    0.07       0  4539.2   0.045       0
  4933.1   0.045       0  4939.1   0.045       0  5222.0   0.035       0
  5488.8   0.045       0  6786.6   0.035       0  6793.2   0.045       0
Bank Sta=4933.1,4939.1
Exp/Cntr=0.3,0.1

Type RM Length L Ch R = 1,9083,445,445,445
BEGIN DESCRIPTION:
Clear Fork Trib2_3 17.0
END DESCRIPTION:
XS GIS Cut Line= 3
      1415704.97      6978238.01      1414505.00      6978738.00
      1412904.99      6980538.01
#Sta/Elev= 30
  3704.6 1926.43  3743.0 1922.52  3798.8 1920.54  3932.1 1914.86  3959.7 1916.10
  3972.9 1915.41  3997.1 1913.33  4032.3 1913.98  4062.1 1911.35  4085.4 1912.78
  4131.9 1910.60  4202.9 1909.64  4239.2 1911.21  4268.4 1909.24  4310.2 1909.26
  4322.1 1910.29  4339.9 1908.32  4398.4 1907.65  4947.4 1905.78  4947.9 1905.28
  4953.4 1905.78  5144.7 1906.75  5336.6 1907.16  6895.7 1910.93  7031.0 1913.14
  7065.4 1914.09  7073.0 1912.65  7116.8 1911.84  7292.5 1912.97  7412.9 1917.24
#Mann=12,-1,0
  3704.6    0.07       0  3798.8   0.045       0  3959.7    0.07       0
  3972.9   0.035       0  4131.9    0.07       0  4310.2   0.045       0
  4947.4   0.045       0  4953.4   0.045       0  5144.7   0.035       0
  5336.6   0.045       0  7031.0   0.035       0  7116.8   0.045       0
Bank Sta=4947.4,4953.4
Exp/Cntr=0.3,0.1

Type RM Length L Ch R = 1,8638,447,447,447
BEGIN DESCRIPTION:
Clear Fork Trib2_3 16.0
END DESCRIPTION:
XS GIS Cut Line= 3
      1415703.23      6977683.05      1414205.00      6978438.00
      1413055.01      6979687.99
#Sta/Elev= 30
  3317.8 1924.74  3548.1 1919.61  3668.0 1915.28  3688.1 1915.22  3704.9 1914.85
  3737.8 1915.47  3752.5 1913.44  3782.4 1913.44  3804.7 1914.97  3827.1 1911.25
  3944.2 1909.07  3988.8 1910.26  4027.8 1908.35  4139.4 1909.24  4211.9 1906.87
  4289.9 1907.81  4401.5 1905.63  4983.8 1904.01  4984.3 1903.51  4990.5 1904.01
  5078.4 1904.14  5208.1 1904.72  5653.6 1905.46  6035.9 1907.63  6078.4 1909.41
  6460.7 1910.20  6595.1 1913.75  6616.0 1916.10  6651.8 1915.50  6694.0 1919.27
#Mann=9,-1,0
  3317.8   0.045       0  3548.1    0.07       0  3668.0   0.045       0
  3688.1    0.07       0  3704.9   0.045       0  4983.8   0.045       0
  4990.5   0.045       0  5078.4   0.035       0  5208.1   0.045       0
Bank Sta=4983.8,4990.5
Exp/Cntr=0.3,0.1

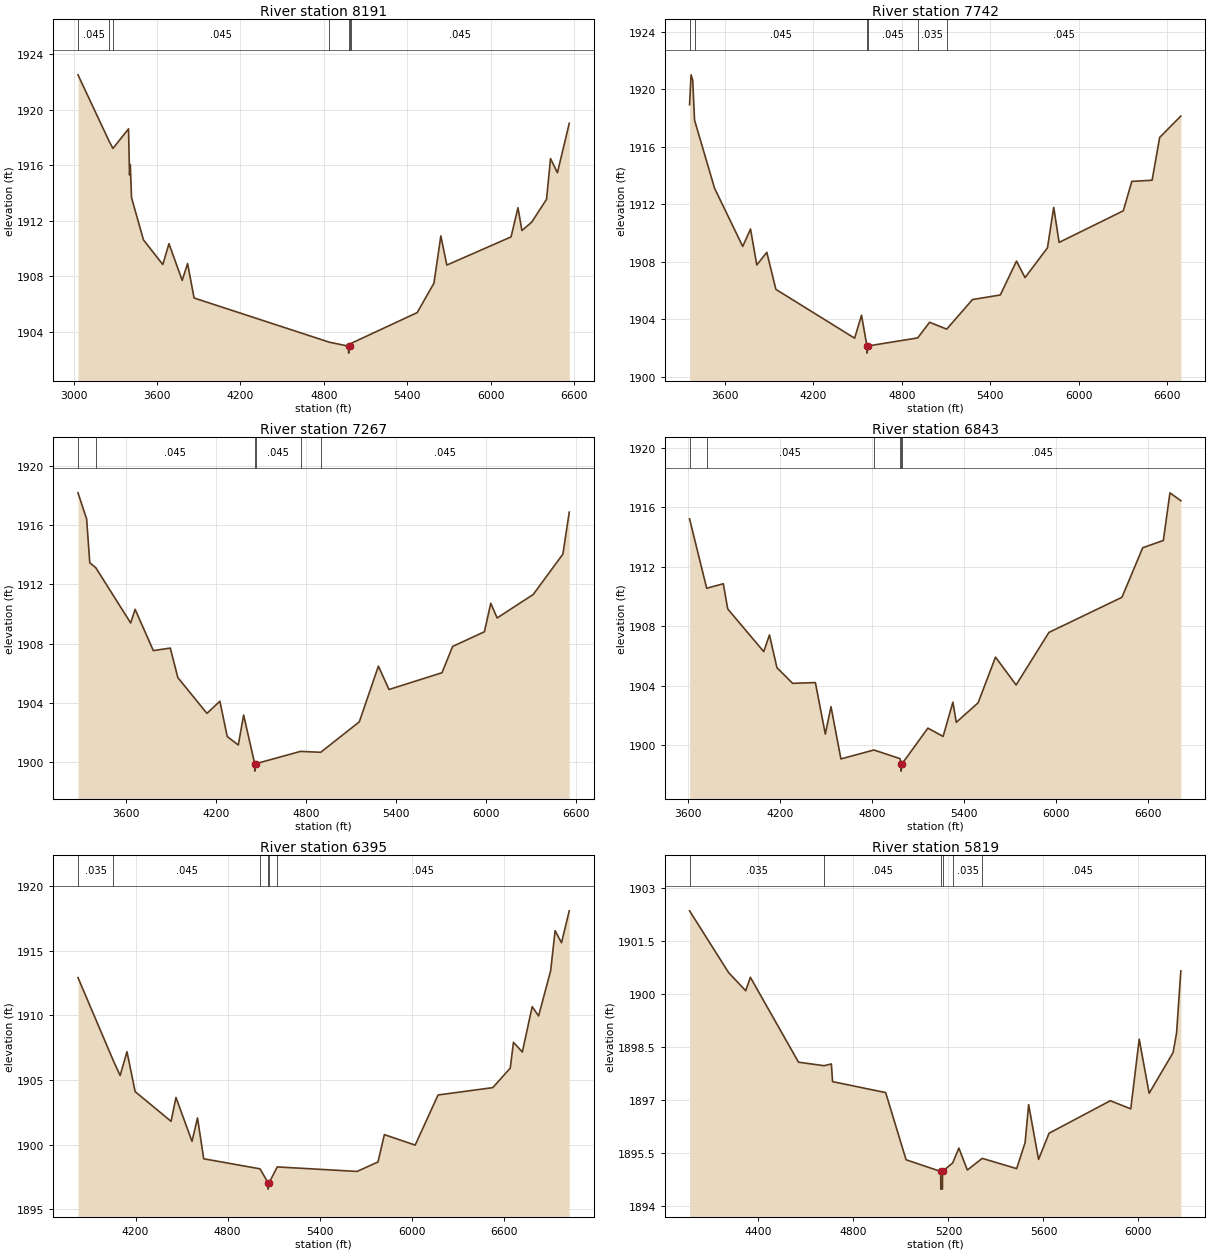
Type RM Length L Ch R = 1,8191,449,449,449
BEGIN DESCRIPTION:
Clear Fork Trib2_3 15.0
END DESCRIPTION:
XS GIS Cut Line= 3
      1415644.20      6977578.89      1413805.00      6978288.00
      1412805.01      6979487.99
#Sta/Elev= 30
  3032.2 1922.52  3256.7 1917.73  3283.7 1917.22  3395.7 1918.63  3403.0 1915.31
  3408.4 1916.06  3417.2 1913.68  3502.9 1910.64  3642.2 1908.86  3686.7 1910.36
  3781.6 1907.72  3820.5 1908.93  3867.3 1906.45  4839.1 1903.27  4978.4 1902.98
  4978.9 1902.48  4985.5 1902.98  4998.0 1903.19  5472.0 1905.40  5592.4 1907.52
  5641.9 1910.92  5684.8 1908.82  6146.9 1910.85  6196.4 1912.95  6225.0 1911.31
  6295.3 1911.91  6402.1 1913.56  6430.7 1916.49  6480.2 1915.47  6565.4 1919.03
#Mann=7,-1,0
  3032.2   0.045       0  3256.7    0.07       0  3283.7   0.045       0
  4839.1   0.035       0  4978.4   0.045       0  4985.5   0.035       0
  4998.0   0.045       0
Bank Sta=4978.4,4985.5
Exp/Cntr=0.3,0.1

Type RM Length L Ch R = 1,7742,475,475,475
BEGIN DESCRIPTION:
Clear Fork Trib2_3 14.0
END DESCRIPTION:
XS GIS Cut Line= 3
      1415405.03      6977337.99      1413855.00      6977888.00
      1412419.25      6978779.81
#Sta/Elev= 30
  3359.4 1918.94  3369.6 1921.02  3380.7 1920.66  3393.2 1917.86  3529.2 1913.12
  3720.2 1909.07  3773.3 1910.28  3815.7 1907.78  3883.7 1908.66  3945.4 1906.08
  4479.8 1902.68  4526.6 1904.28  4563.5 1902.14  4564.0 1901.64  4570.8 1902.14
  4908.0 1902.70  4988.7 1903.79  5105.0 1903.31  5279.8 1905.37  5468.8 1905.69
  5578.6 1908.05  5636.5 1906.90  5788.8 1908.97  5831.3 1911.79  5867.9 1909.35
  6303.6 1911.55  6361.5 1913.60  6499.2 1913.68  6550.4 1916.66  6694.3 1918.15
#Mann=6,-1,0
  3359.4    0.07       0  3393.2   0.045       0  4563.5   0.035       0
  4570.8   0.045       0  4908.0   0.035       0  5105.0   0.045       0
Bank Sta=4563.5,4570.8
Exp/Cntr=0.3,0.1

Type RM Length L Ch R = 1,7267,424,424,424
BEGIN DESCRIPTION:
Clear Fork Trib2_3 13.0
END DESCRIPTION:
XS GIS Cut Line= 3
      1415004.97      6976538.02      1413605.00      6977538.00
      1412504.97      6978638.03
#Sta/Elev= 30
  3279.1 1918.16  3336.8 1916.40  3357.7 1913.45  3397.5 1913.12  3630.5 1909.39
  3660.0 1910.31  3781.7 1907.53  3894.7 1907.70  3945.1 1905.71  4139.3 1903.30
  4225.3 1904.12  4274.5 1901.74  4348.2 1901.17  4383.8 1903.19  4457.6 1899.91
  4458.1 1899.41  4464.9 1899.91  4763.1 1900.74  4897.8 1900.68  5155.1 1902.73
  5282.4 1906.48  5353.1 1904.91  5706.6 1906.04  5777.3 1907.81  5989.5 1908.80
  6031.9 1910.72  6074.3 1909.73  6314.7 1911.31  6512.7 1914.03  6555.2 1916.86
#Mann=6,-1,0
  3279.1   0.035       0  3397.5   0.045       0  4457.6   0.045       0
  4464.9   0.045       0  4763.1   0.035       0  4897.8   0.045       0
Bank Sta=4457.6,4464.9
Exp/Cntr=0.3,0.1

Type RM Length L Ch R = 1,6843,448,448,448
BEGIN DESCRIPTION:
Clear Fork Trib2_3 12.0
END DESCRIPTION:
XS GIS Cut Line= 3
      1414704.99      6976488.01      1413505.00      6977188.00
      1412355.00      6978588.00
#Sta/Elev= 30
  3610.5 1915.21  3722.0 1910.55  3830.5 1910.85  3859.0 1909.16  4093.8 1906.29
  4131.0 1907.41  4179.8 1905.21  4282.0 1904.16  4430.4 1904.21  4494.9 1900.75
  4532.1 1902.59  4596.6 1899.08  4811.8 1899.68  4981.6 1899.10  4988.2 1898.76
  4988.7 1898.26  4995.5 1898.76  5163.3 1901.15  5262.4 1900.59  5326.2 1902.89
  5348.4 1901.54  5490.5 1902.85  5603.9 1905.92  5738.1 1904.05  5951.9 1907.58
  6427.6 1909.94  6563.2 1913.27  6697.4 1913.76  6740.5 1916.96  6811.5 1916.43
#Mann=6,-1,0
  3610.5   0.035       0  3722.0   0.045       0  4811.8   0.035       0
  4981.6   0.045       0  4988.2   0.045       0  4995.5   0.045       0
Bank Sta=4988.2,4995.5
Exp/Cntr=0.3,0.1

Type RM Length L Ch R = 1,6395,576,576,576
BEGIN DESCRIPTION:
Clear Fork Trib2_3 11.0
END DESCRIPTION:
XS GIS Cut Line= 3
      1414455.04      6976387.99      1413355.00      6976788.00
      1411755.00      6978038.00
#Sta/Elev= 30
  3824.7 1912.93  4055.4 1906.49  4099.4 1905.35  4144.0 1907.19  4197.2 1904.10
  4431.3 1901.80  4463.2 1903.65  4567.6 1900.25  4603.5 1902.06  4644.1 1898.90
  5011.0 1898.12  5062.9 1897.05  5063.4 1896.55  5070.5 1897.05  5122.9 1898.27
  5642.8 1897.92  5779.3 1898.65  5820.9 1900.77  6021.7 1899.96  6170.9 1903.84
  6527.3 1904.41  6641.2 1905.92  6662.0 1907.92  6719.9 1907.17  6784.1 1910.68
  6825.7 1909.96  6904.4 1913.46  6933.3 1916.56  6975.0 1915.63  7025.6 1918.10
#Mann=6,-1,0
  3824.7   0.035       0  4055.4   0.045       0  5011.0   0.035       0
  5062.9   0.045       0  5070.5   0.035       0  5122.9   0.045       0
Bank Sta=5062.9,5070.5
Exp/Cntr=0.3,0.1

Type RM Length L Ch R = 1,5819,707,707,707
BEGIN DESCRIPTION:
Mapping XS 6e8177d9
END DESCRIPTION:
XS GIS Cut Line= 3
      1413977.53      6976380.98      1413182.38      6976249.03
      1412156.08      6976984.09
#Sta/Elev= 30
  4110.0 1902.36  4274.7 1900.61  4346.4 1900.10  4366.0 1900.48  4568.7 1898.08
  4676.1 1897.98  4707.0 1898.03  4712.1 1897.53  4935.6 1897.22  5021.6 1895.32
  5167.3 1894.99  5167.8 1894.49  5174.5 1894.49  5175.0 1894.99  5217.7 1895.23
  5243.9 1895.65  5279.6 1895.03  5342.1 1895.36  5487.2 1895.07  5522.8 1895.81
  5537.5 1896.88  5579.3 1895.33  5623.5 1896.07  5881.5 1896.99  5967.5 1896.76
  6003.1 1898.73  6044.9 1897.20  6145.6 1898.35  6160.3 1898.90  6178.4 1900.66
#Mann=6,-1,0
  4110.0   0.035       0  4676.1   0.045       0  5167.3   0.045       0
  5175.0   0.045       0  5217.7   0.035       0  5342.1   0.045       0
Bank Sta=5167.3,5175
Exp/Cntr=0.3,0.1

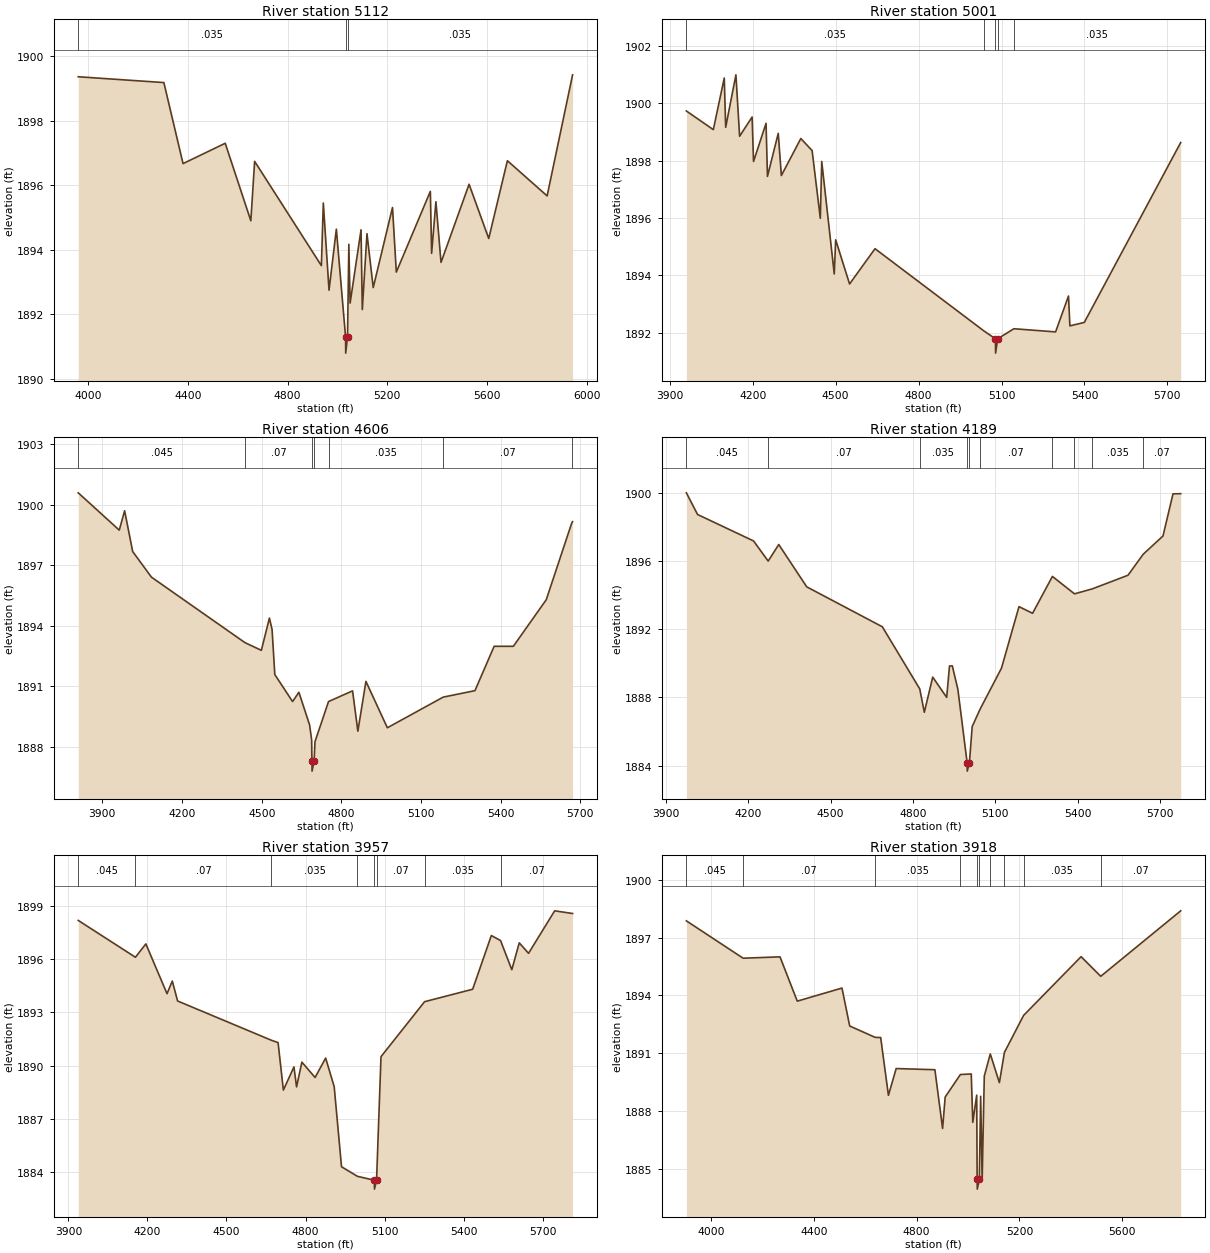
Type RM Length L Ch R = 1,5112,111,111,111
BEGIN DESCRIPTION:
Mapping XS 6c904f55
END DESCRIPTION:
XS GIS Cut Line= 4
      1413526.11      6976266.39      1412633.77      6976040.70
      1412546.96      6976009.45      1411599.57      6975801.23
#Sta/Elev= 30
  3960.2 1899.36  4303.6 1899.18  4380.5 1896.67  4549.7 1897.30  4652.4 1894.90
  4667.6 1896.74  4935.3 1893.51  4943.1 1895.45  4966.0 1892.75  4995.4 1894.64
  5032.4 1891.30  5032.9 1890.80  5040.2 1891.30  5045.5 1894.17  5050.6 1892.35
  5094.4 1894.62  5099.5 1892.15  5118.2 1894.50  5143.3 1892.83  5220.6 1895.31
  5235.9 1893.31  5372.4 1895.81  5377.5 1893.89  5394.7 1895.49  5415.2 1893.61
  5527.8 1896.03  5606.6 1894.35  5681.4 1896.76  5840.8 1895.67  5942.9 1899.42
#Mann=3,-1,0
  3960.2   0.035       0  5032.4   0.035       0  5040.2   0.035       0
Bank Sta=5032.4,5040.2
Exp/Cntr=0.3,0.1

Type RM Length L Ch R = 1,5001,395,395,395
BEGIN DESCRIPTION:
Mapping XS 2874982b
END DESCRIPTION:
XS GIS Cut Line= 4
      1413470.53      6976141.39      1412845.58      6976012.92
      1412463.63      6975919.17      1411720.55      6975776.81
#Sta/Elev= 30
  3960.2 1899.73  4057.7 1899.08  4097.3 1900.88  4102.4 1899.16  4139.4 1900.99
  4152.8 1898.85  4198.0 1899.52  4203.1 1897.97  4248.4 1899.30  4253.5 1897.45
  4292.5 1898.95  4303.8 1897.48  4374.2 1898.77  4415.0 1898.35  4444.7 1895.99
  4449.8 1897.97  4495.1 1894.05  4500.2 1895.24  4550.5 1893.70  4642.5 1894.93
  5036.9 1892.06  5078.1 1891.79  5078.6 1891.29  5086.2 1891.79  5144.8 1892.14
  5295.6 1892.03  5342.3 1893.28  5347.4 1892.24  5399.4 1892.36  5748.1 1898.63
#Mann=5,-1,0
  3960.2   0.035       0  5036.9    0.07       0  5078.1   0.035       0
  5086.2    0.07       0  5144.8   0.035       0
Bank Sta=5078.1,5086.2
Exp/Cntr=0.3,0.1

Type RM Length L Ch R = 1,4606,417,417,417
BEGIN DESCRIPTION:
Mapping XS 539cf5b1
END DESCRIPTION:
XS GIS Cut Line= 3
      1413487.95      6975422.64      1412303.91      6975585.84
      1411659.07      6975752.25
#Sta/Elev= 30
  3809.3 1900.60  3963.7 1898.75  3983.9 1899.71  4014.2 1897.69  4084.8 1896.42
  4437.1 1893.17  4498.7 1892.79  4529.0 1894.39  4539.1 1893.82  4549.3 1891.59
  4616.2 1890.25  4640.0 1890.71  4680.4 1889.09  4688.1 1888.34  4689.1 1887.30
  4689.6 1886.80  4697.3 1887.30  4700.6 1888.26  4751.6 1890.25  4842.1 1890.78
  4862.1 1888.78  4892.4 1891.25  4973.1 1888.95  5183.4 1890.47  5302.9 1890.79
  5375.2 1892.99  5447.5 1892.99  5571.4 1895.30  5666.5 1899.07  5670.5 1899.17
#Mann=7,-1,0
  3809.3   0.045       0  4437.1    0.07       0  4689.1   0.035       0
  4697.3    0.07       0  4751.6   0.035       0  5183.4    0.07       0
  5666.5   0.035       0
Bank Sta=4689.1,4697.3
Exp/Cntr=0.3,0.1

Type RM Length L Ch R = 1,4189,232,232,232
BEGIN DESCRIPTION:
Clear Fork Trib2_3 6.0
END DESCRIPTION:
XS GIS Cut Line= 3
      1413205.03      6975037.99      1412205.00      6975238.00
      1411604.97      6975738.03
#Sta/Elev= 30
  3974.8 1899.99  4015.6 1898.72  4219.6 1897.17  4272.9 1895.99  4311.4 1896.96
  4413.3 1894.48  4688.7 1892.14  4825.0 1888.50  4841.7 1887.13  4872.3 1889.19
  4923.2 1888.00  4933.4 1889.84  4943.6 1889.85  4964.0 1888.47  4997.6 1884.18
  4998.1 1883.68  5006.0 1884.18  5016.1 1886.29  5044.2 1887.29  5122.9 1889.72
  5186.6 1893.32  5236.1 1892.93  5308.4 1895.09  5388.8 1894.07  5453.5 1894.36
  5583.7 1895.16  5639.1 1896.39  5711.2 1897.46  5747.7 1899.93  5775.7 1899.94
#Mann=10,-1,0
  3974.8   0.045       0  4272.9    0.07       0  4825.0   0.035       0
  4997.6   0.035       0  5006.0   0.035       0  5044.2    0.07       0
  5308.4   0.035       0  5388.8    0.07       0  5453.5   0.035       0
  5639.1    0.07       0
Bank Sta=4997.6,5006
Exp/Cntr=0.3,0.1

Type RM Length L Ch R = 1,3957,39,39,39
BEGIN DESCRIPTION:
Mapping XS 18e88332
END DESCRIPTION:
XS GIS Cut Line= 5
      1413140.67      6974974.73      1412175.44      6975058.06
      1412081.69      6975065.01      1411956.69      6975148.34
      1411470.59      6975599.71
#Sta/Elev= 30
  3937.4 1898.17  4154.4 1896.10  4194.0 1896.85  4274.3 1894.05  4294.4 1894.76
  4314.5 1893.64  4670.8 1891.43  4695.9 1891.30  4716.0 1888.63  4756.1 1889.93
  4766.1 1888.81  4786.2 1890.20  4836.4 1889.34  4876.5 1890.43  4908.9 1888.82
  4936.7 1884.32  4997.2 1883.78  5061.3 1883.56  5061.8 1883.06  5069.7 1883.56
  5086.6 1890.51  5252.0 1893.60  5434.5 1894.30  5505.4 1897.32  5540.3 1897.04
  5583.1 1895.40  5611.4 1896.91  5646.6 1896.32  5745.8 1898.71  5813.8 1898.56
#Mann=8,-1,0
  3937.4   0.045       0  4154.4    0.07       0  4670.8   0.035       0
  4997.2    0.07       0  5061.3    0.07       0  5069.7    0.07       0
  5252.0   0.035       0  5540.3    0.07       0
Bank Sta=5061.3,5069.7
Exp/Cntr=0.3,0.1

Type RM Length L Ch R = 1,3918,18,18,18
BEGIN DESCRIPTION:
Mapping XS 8358b88a
END DESCRIPTION:
XS GIS Cut Line= 5
      1413147.63      6974943.48      1412199.74      6975030.28
      1412071.27      6975026.81      1411939.33      6975110.14
      1411433.73      6975574.19
#Sta/Elev= 30
  3904.7 1897.87  4125.4 1895.93  4268.9 1896.00  4336.1 1893.70  4509.9 1894.38
  4540.0 1892.41  4639.0 1891.82  4660.5 1891.81  4690.6 1888.81  4720.7 1890.20
  4871.3 1890.14  4901.3 1887.09  4911.3 1888.72  4970.5 1889.89  5012.8 1889.92
  5018.7 1887.41  5034.0 1888.82  5035.7 1884.44  5036.2 1883.94  5044.1 1884.44
  5049.3 1888.76  5055.2 1884.45  5063.5 1889.81  5086.8 1890.96  5122.2 1889.47
  5141.8 1891.04  5216.4 1892.96  5440.0 1896.01  5516.4 1894.99  5827.4 1898.39
#Mann=10,-1,0
  3904.7   0.045       0  4125.4    0.07       0  4639.0   0.035       0
  4970.5    0.07       0  5035.7    0.07       0  5044.1    0.07       0
  5086.8   0.035       0  5141.8    0.07       0  5216.4   0.035       0
  5516.4    0.07       0
Bank Sta=5035.7,5044.1
Exp/Cntr=0.3,0.1