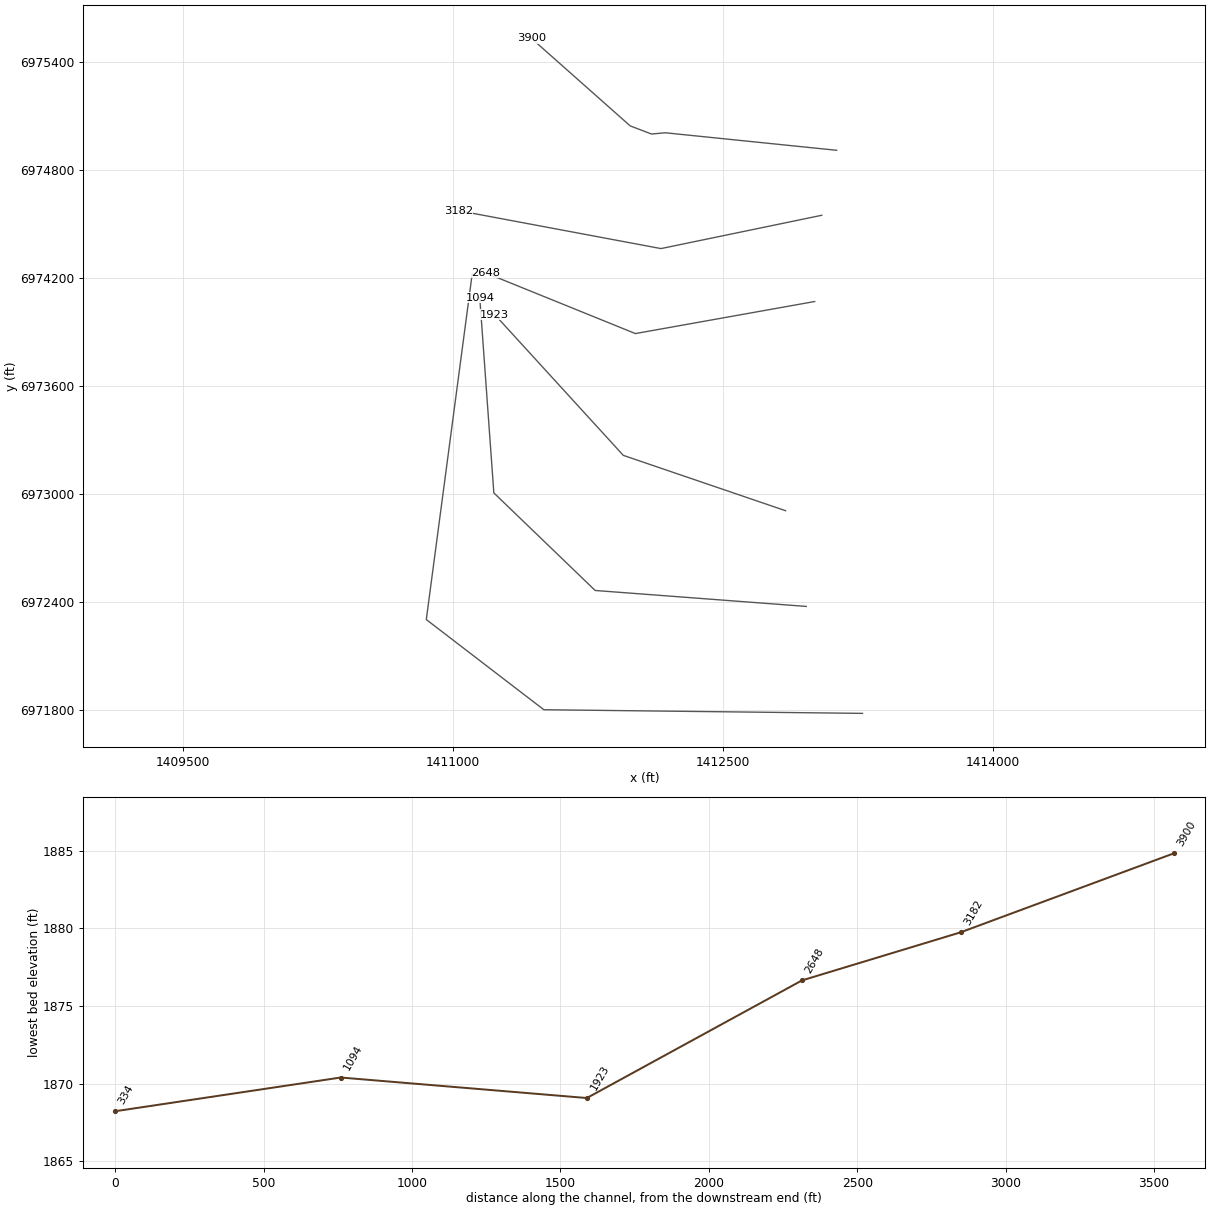
HEC-RAS study Clear Fork Trib2_3.prj: Clear Fork Trib2_3 Base Level Engineering

--- Clear Fork Trib2_3.g01 (geometry) --- (continued)

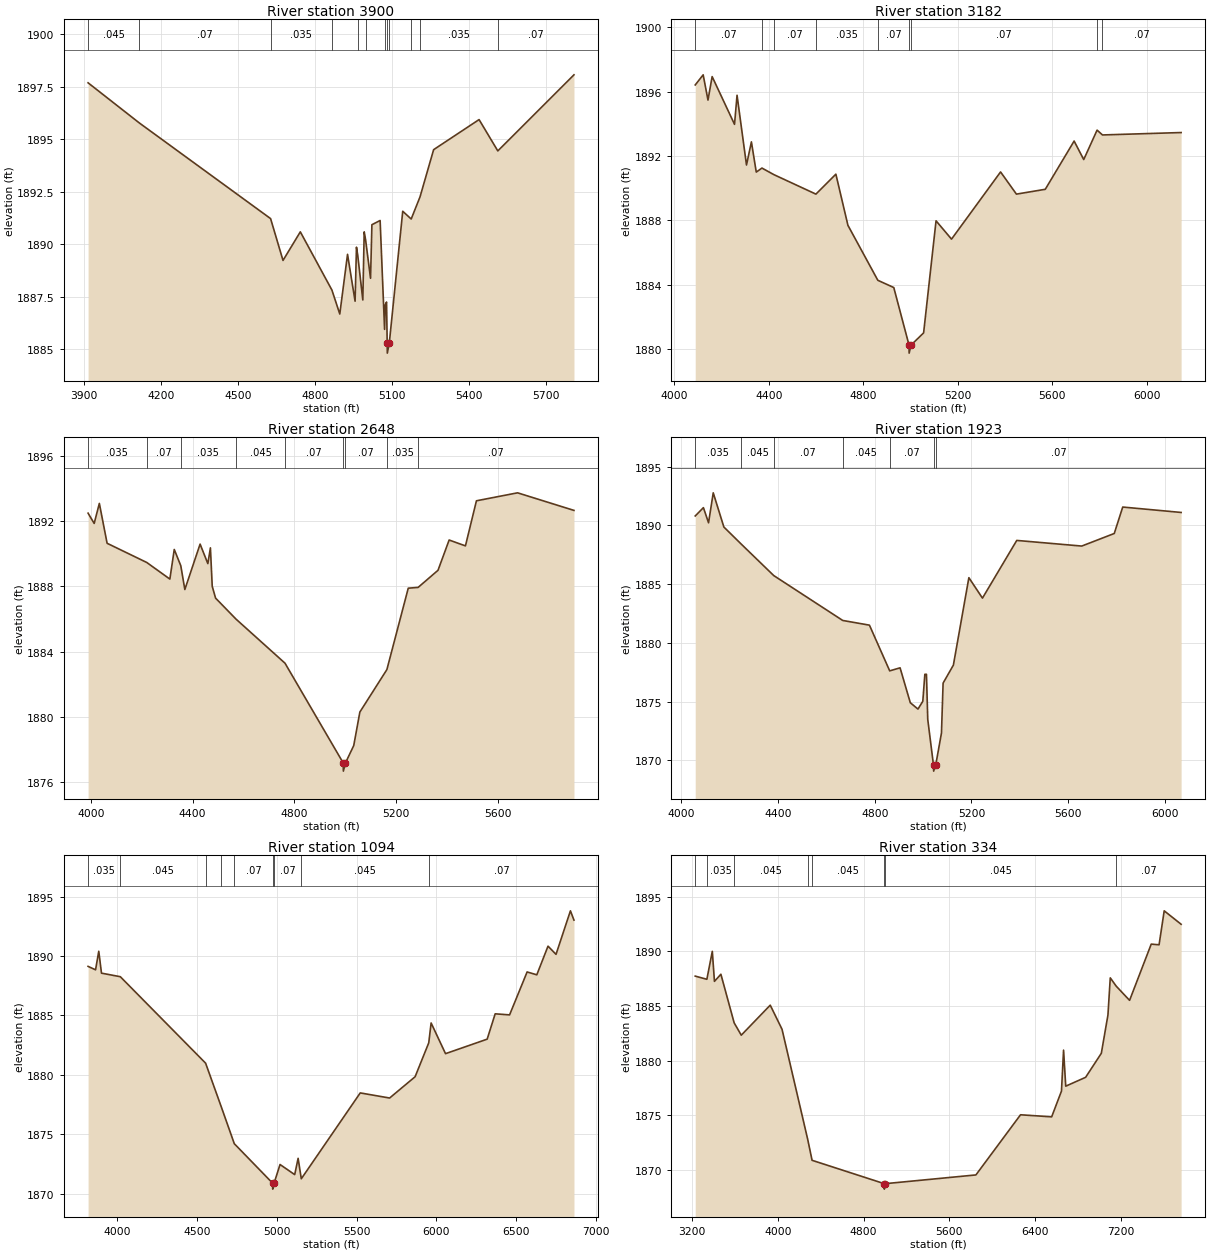
Type RM Length L Ch R = 1,3900,718,718,718
BEGIN DESCRIPTION:
Mapping XS 61c186d5
END DESCRIPTION:
XS GIS Cut Line= 5
      1413130.29      6974908.76      1412178.91      6975005.98
      1412102.52      6974999.03      1411984.46      6975044.17
      1411435.87      6975530.27
#Sta/Elev= 30
  3916.5 1897.68  4116.1 1895.77  4627.3 1891.22  4675.7 1889.23  4743.1 1890.59
  4866.2 1887.82  4896.8 1886.68  4927.0 1889.52  4956.4 1887.29  4961.8 1889.86
  4966.7 1889.48  4986.5 1887.35  4991.9 1890.59  4997.1 1890.23  5016.6 1888.38
  5021.9 1890.93  5053.9 1891.13  5071.3 1885.95  5074.0 1887.12  5078.9 1887.25
  5081.4 1885.32  5081.9 1884.82  5089.8 1885.32  5142.0 1891.57  5174.9 1891.20
  5209.2 1892.25  5262.3 1894.50  5439.3 1895.93  5512.3 1894.44  5808.9 1898.06
#Mann=12,-1,0
  3916.5   0.045       0  4116.1    0.07       0  4627.3   0.035       0
  4866.2    0.07       0  4966.7   0.035       0  4997.1    0.07       0
  5074.0   0.035       0  5081.4    0.07       0  5089.8   0.035       0
  5174.9    0.07       0  5209.2   0.035       0  5512.3    0.07       0
Bank Sta=5081.4,5089.8
Exp/Cntr=0.3,0.1

Type RM Length L Ch R = 1,3182,534,534,534
BEGIN DESCRIPTION:
Clear Fork Trib2_3 4.0
END DESCRIPTION:
XS GIS Cut Line= 3
      1413047.88      6974547.98      1412155.24      6974363.05
      1411029.83      6974573.97
#Sta/Elev= 30
  4088.4 1896.42  4122.0 1897.05  4142.4 1895.48  4160.0 1896.94  4254.7 1893.97
  4265.4 1895.78  4305.4 1891.44  4326.2 1892.88  4346.7 1891.00  4370.8 1891.25
  4421.6 1890.84  4599.2 1889.63  4683.7 1890.87  4734.7 1887.69  4861.3 1884.27
  4928.8 1883.82  4993.3 1880.24  4993.8 1879.74  5001.9 1880.24  5055.1 1881.00
  5107.7 1887.97  5173.2 1886.83  5380.8 1891.01  5447.9 1889.63  5570.0 1889.93
  5692.1 1892.93  5732.8 1891.78  5789.3 1893.61  5812.1 1893.31  6145.0 1893.46
#Mann=9,-1,0
  4088.4    0.07       0  4370.8   0.035       0  4421.6    0.07       0
  4599.2   0.035       0  4861.3    0.07       0  4993.3    0.07       0
  5001.9    0.07       0  5789.3   0.035       0  5812.1    0.07       0
Bank Sta=4993.3,5001.9
Exp/Cntr=0.3,0.1

Type RM Length L Ch R = 1,2648,725,725,725
BEGIN DESCRIPTION:
Clear Fork Trib2_3 3.0
END DESCRIPTION:
XS GIS Cut Line= 3
      1413008.60      6974069.24      1412013.08      6973891.30
      1411179.45      6974229.17
#Sta/Elev= 30
  3988.7 1892.50  4012.7 1891.87  4033.0 1893.10  4063.5 1890.65  4219.5 1889.47
  4310.3 1888.45  4327.6 1890.27  4353.3 1889.27  4369.2 1887.81  4429.2 1890.60
  4459.7 1889.40  4469.8 1890.37  4476.9 1888.01  4490.1 1887.28  4570.5 1885.99
  4763.2 1883.28  4992.1 1877.15  4992.6 1876.65  5000.8 1877.15  5033.4 1878.22
  5057.5 1880.28  5163.8 1882.89  5247.8 1887.89  5286.7 1887.94  5364.8 1888.99
  5408.6 1890.85  5472.7 1890.49  5515.9 1893.26  5677.7 1893.75  5899.5 1892.67
#Mann=9,-1,0
  3988.7   0.035       0  4219.5    0.07       0  4353.3   0.035       0
  4570.5   0.045       0  4763.2    0.07       0  4992.1    0.07       0
  5000.8    0.07       0  5163.8   0.035       0  5286.7    0.07       0
Bank Sta=4992.1,5000.8
Exp/Cntr=0.3,0.1

Type RM Length L Ch R = 1,1923,829,829,829
BEGIN DESCRIPTION:
Mapping XS 3ed0a262
END DESCRIPTION:
XS GIS Cut Line= 3
      1412847.12      6972907.79      1411946.10      6973215.07
      1411232.58      6973996.29
#Sta/Elev= 30
  4057.4 1890.79  4091.3 1891.50  4112.5 1890.21  4131.9 1892.76  4175.9 1889.85
  4247.6 1888.40  4382.2 1885.72  4667.6 1881.90  4778.1 1881.50  4861.9 1877.61
  4904.8 1877.87  4947.1 1874.90  4978.8 1874.36  4998.8 1875.02  5007.3 1877.32
  5013.9 1877.32  5019.3 1873.48  5043.1 1869.58  5043.6 1869.08  5052.1 1869.58
  5076.0 1872.32  5082.8 1876.57  5125.3 1878.10  5189.4 1885.54  5245.6 1883.80
  5387.5 1888.71  5656.3 1888.23  5790.8 1889.30  5825.9 1891.55  6067.4 1891.09
#Mann=7,-1,0
  4057.4   0.035       0  4247.6   0.045       0  4382.2    0.07       0
  4667.6   0.045       0  4861.9    0.07       0  5043.1    0.07       0
  5052.1    0.07       0
Bank Sta=5043.1,5052.1
Exp/Cntr=0.3,0.1

Type RM Length L Ch R = 1,1094,760,760,760
BEGIN DESCRIPTION:
Mapping XS 95415786
END DESCRIPTION:
XS GIS Cut Line= 4
      1412961.71      6972376.53      1411789.85      6972465.07
      1411227.35      6973006.74      1411149.22      6974090.12
#Sta/Elev= 30
  3819.0 1889.13  3865.8 1888.84  3885.9 1890.40  3902.9 1888.56  4020.9 1888.26
  4554.9 1880.99  4654.0 1877.28  4734.5 1874.22  4974.5 1870.90  4975.0 1870.40
  4983.6 1870.90  5020.9 1872.47  5112.7 1871.62  5134.1 1872.99  5154.0 1871.27
  5523.1 1878.49  5707.0 1878.06  5866.6 1879.85  5952.0 1882.70  5966.9 1884.37
  6057.1 1881.79  6317.8 1883.01  6367.9 1885.14  6458.1 1885.05  6567.9 1888.66
  6628.6 1888.42  6698.8 1890.83  6748.9 1890.14  6839.1 1893.80  6861.3 1893.02
#Mann=9,-1,0
  3819.0   0.035       0  4020.9   0.045       0  4554.9    0.07       0
  4654.0   0.045       0  4734.5    0.07       0  4974.5    0.07       0
  4983.6    0.07       0  5154.0   0.045       0  5952.0    0.07       0
Bank Sta=4974.5,4983.6
Exp/Cntr=0.3,0.1

Type RM Length L Ch R = 1,334,0,0,0
BEGIN DESCRIPTION:
Clear Fork Trib2_3 1.0
END DESCRIPTION:
XS GIS Cut Line= 4
      1413274.18      6971782.78      1411505.00      6971803.00
      1410852.35      6972303.61      1411107.39      6974224.22
#Sta/Elev= 30
  3230.7 1887.74  3339.2 1887.45  3389.9 1890.01  3409.9 1887.26  3469.9 1887.91
  3593.6 1883.46  3659.9 1882.33  3929.9 1885.08  4039.9 1882.87  4279.6 1872.77
  4319.9 1870.87  4992.9 1868.73  4993.4 1868.23  5002.0 1868.73  5847.1 1869.53
  6263.1 1875.04  6553.3 1874.85  6644.7 1877.21  6664.2 1880.96  6684.4 1877.66
  6869.7 1878.47  7016.2 1880.67  7077.8 1884.17  7099.6 1887.58  7155.1 1886.82
  7279.6 1885.52  7481.4 1890.67  7554.5 1890.61  7602.4 1893.72  7760.0 1892.49
#Mann=8,-1,0
  3230.7    0.07       0  3339.2   0.035       0  3593.6   0.045       0
  4279.6    0.07       0  4319.9   0.045       0  4992.9   0.045       0
  5002.0   0.045       0  7155.1    0.07       0
Bank Sta=4992.9,5002
Exp/Cntr=0.3,0.1

Chan Stop Cuts=-1