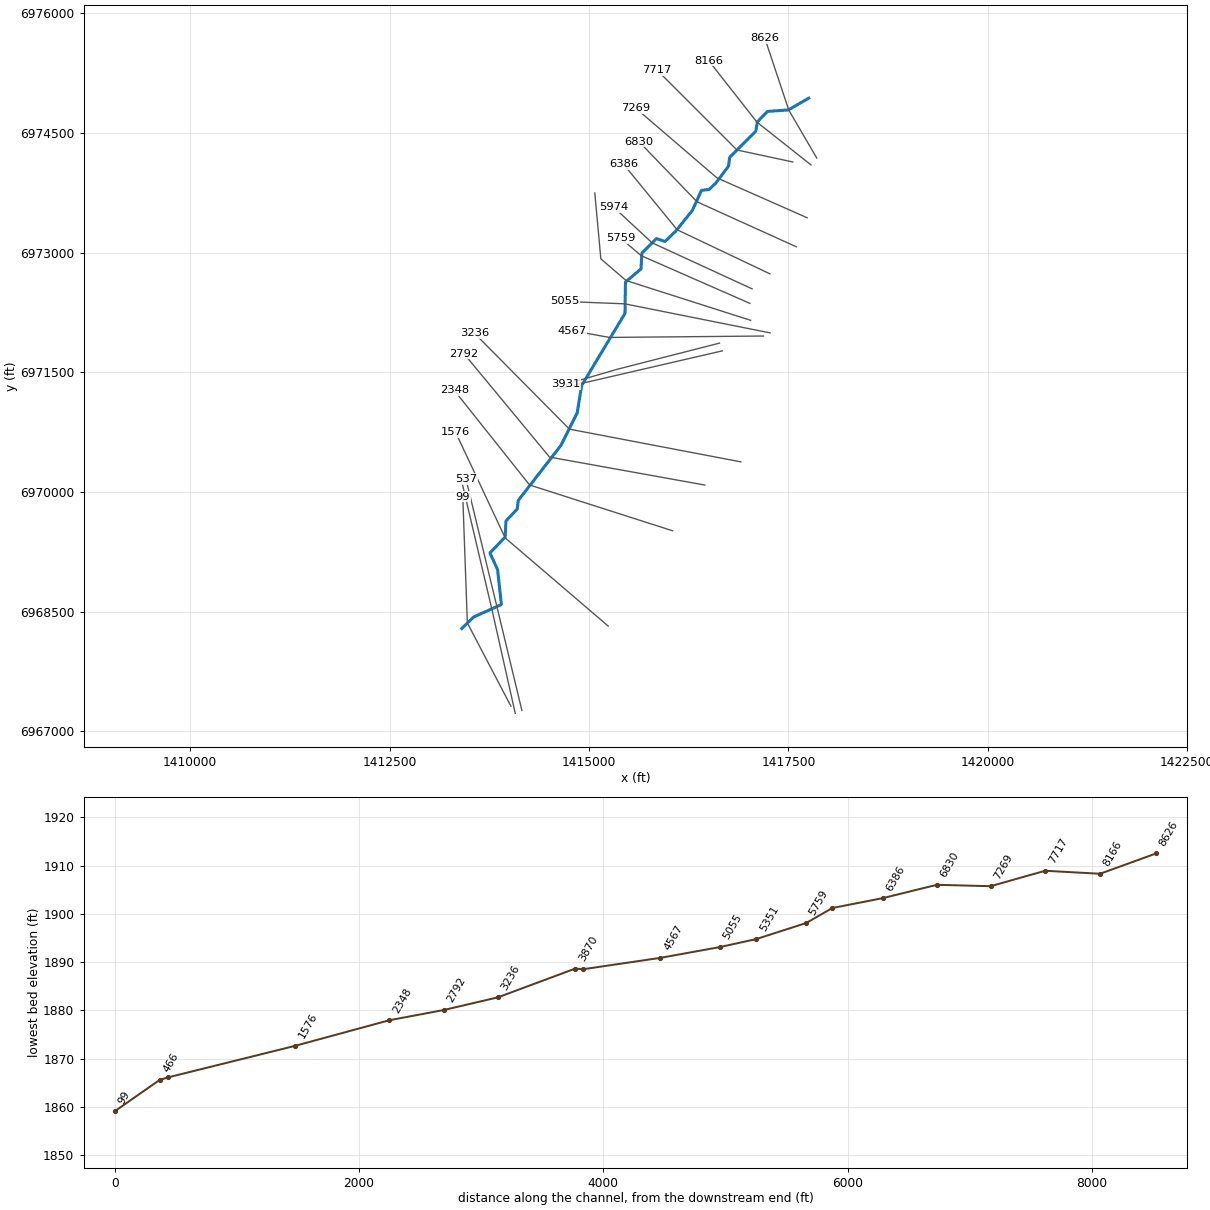
--- Clear Fork Trib2_4.prj (project) ---

Proj Title=Clear Fork Trib2_4 Base Level Engineering
Current Plan=p01
Default Exp/Contr=0.3,0.1
English Units
Geom File=g01
Flow File=f01
Plan File=p01
BEGIN DESCRIPTION:
Clear Fork Trib2_4
END DESCRIPTION:

--- Clear Fork Trib2_4.p01 (plan) ---

Plan Title=Multiple Run
Short Identifier=Multiple
Geom File=g01
Flow File=f01
Subcritical Flow
K Sum by GR= 0
Std Step Tol= 0.01
Critical Tol= 0.01
Num of Std Step Trials= 20
Max Error Tol= 0.3
Flow Tol Ratio= 0.001
Split Flow NTrial= 30
Split Flow Tol= 0.02
Split Flow Ratio= 0.02
Log Output Level= 0
Friction Slope Method= 1
Unsteady Friction Slope Method= 2
Unsteady Bridges Friction Slope Method= 1
Parabolic Critical Depth
Global Vel Dist=  1 , 1 , 1
Global Log Level= 0
CheckData=True
Encroach Param= -1, 0, 0, 0
BEGIN DESCRIPTION:
Multiple Run
END DESCRIPTION:

--- Clear Fork Trib2_4.f01 (steady flow) ---

Flow Title=Multiple
Number of Profiles=7
Profile Names=10-year,25-year,50-year,1pct_min,100-year,1pct_plu,500-year
River Rch & RM= Clear Fork Trib2,Reach-1,8626
     358     509     636     395     787    1571    1224
Boundary for River Rch & Prof#=Clear Fork Trib2,Reach-1,1
Up Type=0
Dn Type=3
Dn Slope=0.005
Boundary for River Rch & Prof#=Clear Fork Trib2,Reach-1,2
Up Type=0
Dn Type=3
Dn Slope=0.005
Boundary for River Rch & Prof#=Clear Fork Trib2,Reach-1,3
Up Type=0
Dn Type=3
Dn Slope=0.005
Boundary for River Rch & Prof#=Clear Fork Trib2,Reach-1,4
Up Type=0
Dn Type=3
Dn Slope=0.005
Boundary for River Rch & Prof#=Clear Fork Trib2,Reach-1,5
Up Type=0
Dn Type=3
Dn Slope=0.005
Boundary for River Rch & Prof#=Clear Fork Trib2,Reach-1,6
Up Type=0
Dn Type=3
Dn Slope=0.005
Boundary for River Rch & Prof#=Clear Fork Trib2,Reach-1,7
Up Type=0
Dn Type=3
Dn Slope=0.005

--- Clear Fork Trib2_4.g01 (geometry) ---

Geom Title=Existing Conditions

River Reach=Clear Fork Trib2,Reach-1
Reach XY= 30
      1417755.00      6974938.00      1417499.07      6974790.24
      1417238.23      6974771.57      1417110.52      6974640.43
      1417091.60      6974524.70      1416762.86      6974194.17
      1416749.48      6974085.57      1416591.38      6973874.76
      1416507.38      6973793.54      1416410.44      6973782.75
      1416296.86      6973531.94      1416088.35      6973271.33
      1415953.35      6973141.16      1415844.95      6973176.89
      1415662.81      6972994.19      1415651.93      6972796.30
      1415457.06      6972632.15      1415451.25      6972239.55
      1414908.76      6971336.44      1414851.24      6970989.56
      1414649.17      6970585.70      1414112.88      6969894.16
      1414099.48      6969785.57      1413958.54      6969636.54
      1413949.54      6969435.55      1413758.12      6969236.37
      1413853.80      6969027.50      1413901.55      6968589.25
      1413552.70      6968432.17      1413405.00      6968288.00

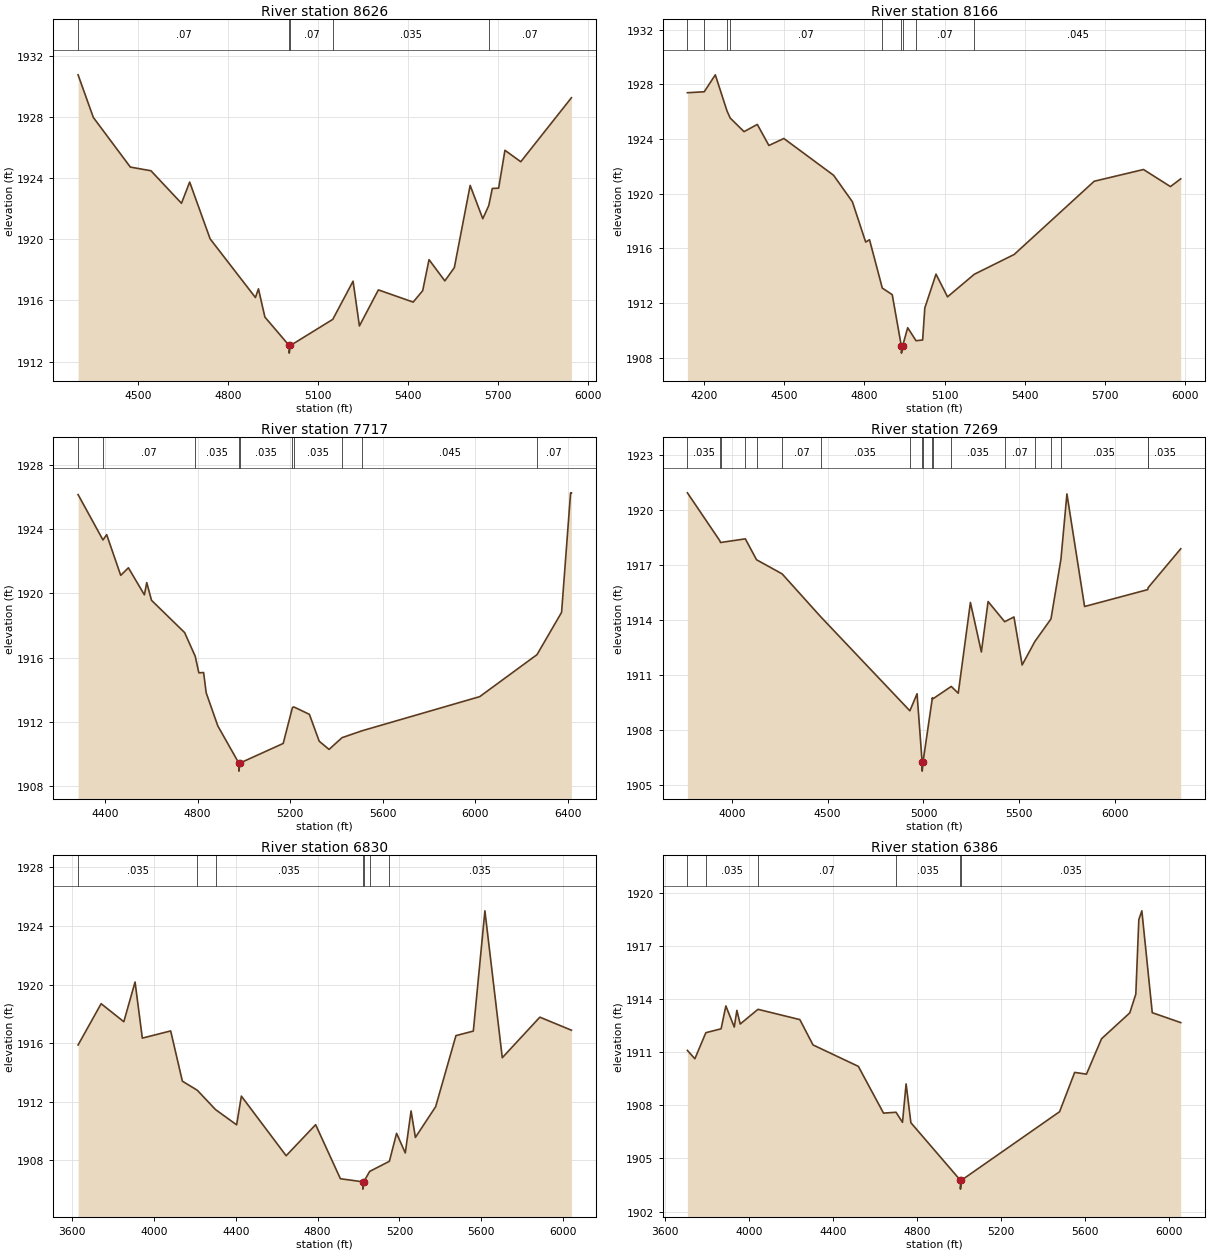
Type RM Length L Ch R = 1,8626,460,460,460
BEGIN DESCRIPTION:
Clear Fork Trib2_4 15.0
END DESCRIPTION:
XS GIS Cut Line= 3
      1417854.99      6974188.01      1417505.00      6974788.00
      1417205.00      6975688.01
#Sta/Elev= 30
  4301.3 1930.77  4352.1 1927.98  4475.4 1924.73  4544.0 1924.49  4645.7 1922.36
  4673.0 1923.75  4741.2 1920.03  4892.1 1916.19  4902.1 1916.76  4923.6 1914.91
  5004.3 1913.05  5004.6 1912.55  5008.6 1913.05  5149.7 1914.76  5217.3 1917.26
  5238.4 1914.33  5301.6 1916.69  5417.5 1915.89  5449.2 1916.64  5470.3 1918.67
  5523.0 1917.28  5554.6 1918.15  5607.3 1923.53  5649.4 1921.35  5669.3 1922.21
  5681.1 1923.33  5702.2 1923.35  5723.2 1925.83  5775.9 1925.08  5944.6 1929.27
#Mann=5,-1,0
  4301.3    0.07       0  5004.3    0.07       0  5008.6    0.07       0
  5149.7   0.035       0  5669.3    0.07       0
Bank Sta=5004.3,5008.6
Exp/Cntr=0.3,0.1

Type RM Length L Ch R = 1,8166,449,449,449
BEGIN DESCRIPTION:
Clear Fork Trib2_4 14.0
END DESCRIPTION:
XS GIS Cut Line= 3
      1417784.35      6974100.21      1417105.00      6974638.00
      1416500.51      6975408.27
#Sta/Elev= 30
  4137.7 1927.39  4200.6 1927.46  4242.1 1928.70  4285.8 1926.06  4297.7 1925.54
  4349.5 1924.54  4399.2 1925.07  4442.5 1923.53  4498.5 1924.04  4684.5 1921.35
  4754.9 1919.41  4804.6 1916.46  4819.0 1916.63  4866.8 1913.09  4904.0 1912.61
  4938.2 1908.83  4938.5 1908.33  4942.5 1908.83  4961.7 1910.19  4993.0 1909.24
  5017.7 1909.29  5025.8 1911.63  5067.7 1914.11  5110.8 1912.45  5210.8 1914.10
  5360.1 1915.55  5659.5 1920.91  5843.9 1921.77  5944.8 1920.52  5983.3 1921.09
#Mann=9,-1,0
  4137.7   0.035       0  4200.6    0.07       0  4285.8   0.035       0
  4297.7    0.07       0  4866.8   0.035       0  4938.2    0.07       0
  4942.5   0.035       0  4993.0    0.07       0  5210.8   0.045       0
Bank Sta=4938.2,4942.5
Exp/Cntr=0.3,0.1

Type RM Length L Ch R = 1,7717,448,448,448
BEGIN DESCRIPTION:
Clear Fork Trib2_4 13.0
END DESCRIPTION:
XS GIS Cut Line= 3
      1417554.97      6974138.01      1416855.00      6974288.00
      1415854.98      6975288.02
#Sta/Elev= 30
  4284.1 1926.14  4391.6 1923.32  4407.6 1923.65  4468.2 1921.12  4501.4 1921.59
  4570.4 1919.91  4580.6 1920.67  4601.1 1919.57  4744.3 1917.56  4789.9 1916.09
  4805.6 1915.06  4826.1 1915.08  4837.2 1913.82  4887.5 1911.76  4978.1 1909.45
  4978.4 1908.95  4982.7 1909.45  5169.7 1910.67  5209.8 1912.91  5215.9 1912.94
  5282.8 1912.48  5325.2 1910.81  5367.7 1910.30  5423.8 1911.03  5510.6 1911.46
  6018.2 1913.58  6265.6 1916.19  6371.7 1918.82  6410.6 1926.25  6414.2 1926.25
#Mann=10,-1,0
  4284.1   0.035       0  4391.6    0.07       0  4789.9   0.035       0
  4978.1   0.035       0  4982.7   0.035       0  5209.8    0.07       0
  5215.9   0.035       0  5423.8    0.07       0  5510.6   0.045       0
  6265.6    0.07       0
Bank Sta=4978.1,4982.7
Exp/Cntr=0.3,0.1

Type RM Length L Ch R = 1,7269,439,439,439
BEGIN DESCRIPTION:
Clear Fork Trib2_4 12.0
END DESCRIPTION:
XS GIS Cut Line= 3
      1417735.95      6973438.08      1416605.00      6973938.00
      1415589.07      6974809.92
#Sta/Elev= 30
  3767.8 1920.93  3936.1 1918.33  3940.9 1918.22  4070.2 1918.42  4128.6 1917.28
  4262.2 1916.51  4463.7 1914.17  4929.1 1909.04  4966.6 1909.97  4993.1 1906.25
  4993.4 1905.75  4997.7 1906.25  5046.6 1909.75  5047.5 1909.68  5145.1 1910.37
  5181.6 1910.00  5245.2 1914.95  5302.3 1912.25  5337.4 1915.00  5424.0 1913.90
  5472.4 1914.16  5515.2 1911.54  5581.5 1912.82  5665.6 1914.05  5717.7 1917.31
  5748.9 1920.87  5841.1 1914.73  6170.7 1915.65  6173.0 1915.76  6343.1 1917.88
#Mann=19,-1,0
  3767.8   0.035       0  3936.1    0.07       0  3940.9   0.035       0
  4070.2    0.07       0  4128.6   0.035       0  4262.2    0.07       0
  4463.7   0.035       0  4929.1    0.07       0  4993.1    0.07       0
  4997.7    0.07       0  5046.6   0.035       0  5047.5    0.07       0
  5145.1   0.035       0  5424.0    0.07       0  5581.5   0.035       0
  5665.6    0.07       0  5717.7   0.035       0  6170.7    0.07       0
  6173.0   0.035       0
Bank Sta=4993.1,4997.7
Exp/Cntr=0.3,0.1

Type RM Length L Ch R = 1,6830,444,444,444
BEGIN DESCRIPTION:
Clear Fork Trib2_4 11.0
END DESCRIPTION:
XS GIS Cut Line= 3
      1417598.63      6973074.75      1416355.00      6973638.00
      1415629.23      6974390.08
#Sta/Elev= 30
  3629.7 1915.88  3742.3 1918.70  3853.2 1917.47  3908.1 1920.18  3943.6 1916.35
  4082.1 1916.84  4139.3 1913.41  4212.2 1912.79  4301.3 1911.47  4404.4 1910.43
  4427.5 1912.39  4646.3 1908.32  4790.4 1910.44  4911.4 1906.75  5020.8 1906.54
  5021.1 1906.04  5025.4 1906.54  5054.4 1907.25  5150.7 1907.94  5185.9 1909.85
  5228.4 1908.51  5256.7 1911.38  5277.8 1909.57  5376.8 1911.67  5475.9 1916.52
  5560.8 1916.83  5617.4 1925.04  5702.3 1915.01  5885.9 1917.78  6040.1 1916.89
#Mann=7,-1,0
  3629.7   0.035       0  4212.2    0.07       0  4301.3   0.035       0
  5020.8   0.035       0  5025.4   0.035       0  5054.4    0.07       0
  5150.7   0.035       0
Bank Sta=5020.8,5025.4
Exp/Cntr=0.3,0.1

Type RM Length L Ch R = 1,6386,412,412,412
BEGIN DESCRIPTION:
Clear Fork Trib2_4 10.0
END DESCRIPTION:
XS GIS Cut Line= 3
      1417267.55      6972735.63      1416105.00      6973288.00
      1415434.63      6974108.32
#Sta/Elev= 30
  3707.8 1911.10  3743.3 1910.63  3795.5 1912.10  3868.0 1912.32  3890.7 1913.61
  3930.6 1912.42  3943.1 1913.36  3958.9 1912.59  4043.4 1913.42  4242.6 1912.84
  4305.2 1911.41  4520.8 1910.20  4640.6 1907.56  4700.0 1907.61  4730.8 1907.04
  4748.0 1909.21  4770.7 1907.02  5006.2 1903.77  5006.5 1903.27  5010.9 1903.77
  5478.0 1907.64  5549.8 1909.86  5605.8 1909.76  5677.6 1911.76  5811.9 1913.22
  5840.6 1914.28  5854.9 1918.48  5869.3 1918.98  5918.8 1913.23  6054.3 1912.67
#Mann=6,-1,0
  3707.8    0.07       0  3795.5   0.035       0  4043.4    0.07       0
  4700.0   0.035       0  5006.2   0.035       0  5010.9   0.035       0
Bank Sta=5006.2,5010.9
Exp/Cntr=0.3,0.1

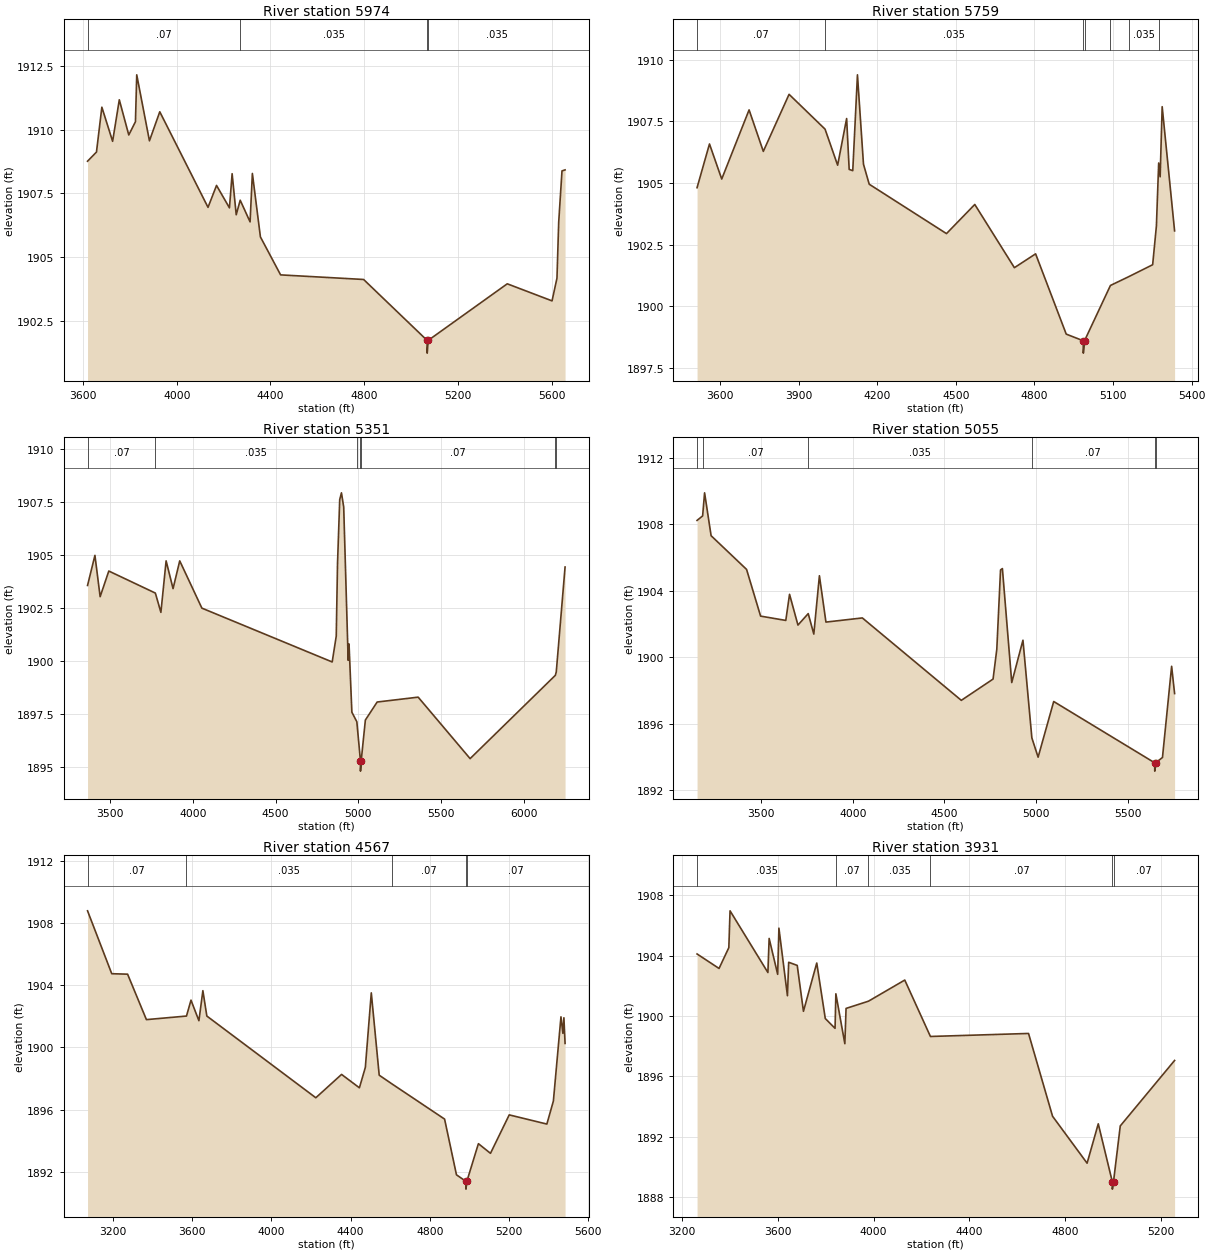
Type RM Length L Ch R = 1,5974,215,215,215
BEGIN DESCRIPTION:
Mapping XS 15307f31
END DESCRIPTION:
XS GIS Cut Line= 3
      1417044.94      6972547.24      1415790.58      6973124.50
      1415309.43      6973570.97
#Sta/Elev= 30
  3619.7 1908.76  3657.8 1909.12  3680.8 1910.88  3726.7 1909.54  3755.2 1911.17
  3795.6 1909.79  3824.1 1910.31  3829.6 1912.15  3883.8 1909.56  3927.9 1910.70
  4133.7 1906.95  4170.0 1907.81  4225.1 1906.93  4236.5 1908.27  4254.0 1906.66
  4271.0 1907.23  4313.1 1906.38  4322.9 1908.28  4357.2 1905.79  4443.3 1904.30
  4797.5 1904.12  5068.3 1901.73  5068.7 1901.23  5073.0 1901.73  5410.3 1903.95
  5601.3 1903.28  5622.3 1904.17  5629.7 1906.36  5643.8 1908.38  5656.9 1908.42
#Mann=4,-1,0
  3619.7    0.07       0  4271.0   0.035       0  5068.3   0.035       0
  5073.0   0.035       0
Bank Sta=5068.3,5073
Exp/Cntr=0.3,0.1

Type RM Length L Ch R = 1,5759,408,408,408
BEGIN DESCRIPTION:
Clear Fork Trib2_4 9.0
END DESCRIPTION:
XS GIS Cut Line= 3
      1417016.47      6972365.31      1415654.71      6972963.12
      1415399.57      6973180.06
#Sta/Elev= 30
  3512.8 1904.81  3560.2 1906.58  3606.9 1905.16  3711.3 1907.96  3765.6 1906.28
  3863.9 1908.59  4001.2 1907.18  4049.2 1905.72  4083.5 1907.61  4093.2 1905.55
  4106.9 1905.50  4124.8 1909.38  4147.8 1905.76  4169.7 1904.95  4464.5 1902.95
  4572.5 1904.13  4723.6 1901.57  4804.6 1902.13  4921.4 1898.88  4986.4 1898.61
  4986.7 1898.11  4991.2 1898.61  5090.1 1900.85  5160.7 1901.21  5251.2 1901.69
  5265.5 1903.26  5274.2 1905.81  5279.8 1905.25  5287.5 1908.09  5334.9 1903.06
#Mann=7,-1,0
  3512.8    0.07       0  4001.2   0.035       0  4986.4   0.035       0
  4991.2   0.035       0  5090.1    0.07       0  5160.7   0.035       0
  5274.2    0.07       0
Bank Sta=4986.4,4991.2
Exp/Cntr=0.3,0.1

Type RM Length L Ch R = 1,5351,296,296,296
BEGIN DESCRIPTION:
Mapping XS 916e3c84
END DESCRIPTION:
XS GIS Cut Line= 4
      1417027.59      6972152.27      1415465.06      6972651.41
      1415148.49      6972923.25      1415072.80      6973749.81
#Sta/Elev= 30
  3362.5 1903.55  3407.2 1904.97  3438.7 1903.02  3491.1 1904.23  3772.6 1903.19
  3806.1 1902.28  3837.6 1904.71  3879.6 1903.40  3920.0 1904.71  4053.9 1902.48
  4841.9 1899.94  4866.4 1901.16  4874.1 1904.58  4887.4 1907.60  4897.9 1907.92
  4911.5 1907.25  4938.5 1900.02  4943.7 1900.79  4960.9 1897.57  4990.9 1897.12
  5012.6 1895.29  5013.0 1894.79  5017.4 1895.29  5042.5 1897.20  5113.8 1898.05
  5361.8 1898.28  5675.9 1895.38  6191.3 1899.31  6196.9 1899.47  6250.1 1904.42
#Mann=7,-1,0
  3362.5    0.07       0  3772.6   0.035       0  4990.9    0.07       0
  5012.6    0.07       0  5017.4    0.07       0  6191.3   0.035       0
  6196.9    0.07       0
Bank Sta=5012.6,5017.4
Exp/Cntr=0.3,0.1

Type RM Length L Ch R = 1,5055,488,488,488
BEGIN DESCRIPTION:
Mapping XS 43454372
END DESCRIPTION:
XS GIS Cut Line= 3
      1417270.19      6971994.93      1415447.47      6972359.48
      1414698.86      6972388.67
#Sta/Elev= 30
  3148.9 1908.23  3179.3 1908.50  3190.0 1909.89  3225.6 1907.31  3419.3 1905.28
  3495.9 1902.47  3633.5 1902.21  3654.0 1903.78  3699.9 1901.93  3756.0 1902.62
  3786.5 1901.39  3817.1 1904.90  3852.8 1902.11  4051.6 1902.36  4592.1 1897.40
  4765.5 1898.68  4785.9 1900.47  4806.3 1905.25  4816.5 1905.33  4867.5 1898.47
  4928.7 1901.02  4977.4 1895.14  5011.5 1893.98  5096.7 1897.33  5648.3 1893.64
  5648.6 1893.14  5653.1 1893.64  5690.7 1893.96  5740.7 1899.45  5756.9 1897.81
#Mann=6,-1,0
  3148.9   0.035       0  3179.3    0.07       0  3756.0   0.035       0
  4977.4    0.07       0  5648.3    0.07       0  5653.1    0.07       0
Bank Sta=5648.3,5653.1
Exp/Cntr=0.3,0.1

Type RM Length L Ch R = 1,4567,636,636,636
BEGIN DESCRIPTION:
Clear Fork Trib2_4 7.0
END DESCRIPTION:
XS GIS Cut Line= 3
      1417187.22      6971955.73      1415255.00      6971938.00
      1414784.62      6972024.13
#Sta/Elev= 30
  3072.5 1908.78  3194.7 1904.74  3274.7 1904.71  3369.7 1901.79  3572.0 1902.02
  3594.7 1903.04  3634.7 1901.72  3654.7 1903.65  3674.7 1902.02  4224.8 1896.77
  4354.8 1898.27  4444.8 1897.41  4474.8 1898.72  4504.8 1903.51  4544.8 1898.22
  4609.2 1897.66  4874.8 1895.40  4934.8 1891.82  4982.4 1891.40  4982.7 1890.90
  4987.2 1891.40  5045.5 1893.82  5106.5 1893.20  5201.1 1895.67  5391.1 1895.08
  5424.0 1896.56  5462.3 1901.97  5472.0 1900.91  5477.1 1901.91  5483.0 1900.26
#Mann=5,-1,0
  3072.5    0.07       0  3572.0   0.035       0  4609.2    0.07       0
  4982.4    0.07       0  4987.2    0.07       0
Bank Sta=4982.4,4987.2
Exp/Cntr=0.3,0.1

Type RM Length L Ch R = 1,3931,61,61,61
BEGIN DESCRIPTION:
Mapping XS a3ec7bca
END DESCRIPTION:
XS GIS Cut Line= 4
      1416635.55      6971866.64      1415346.48      6971536.78
      1414955.82      6971422.66      1414709.69      6971348.34
#Sta/Elev= 30
  3262.4 1904.12  3354.2 1903.16  3395.1 1904.54  3400.2 1906.98  3558.3 1902.89
  3563.5 1905.15  3599.1 1902.77  3604.3 1905.83  3639.9 1901.35  3645.1 1903.57
  3680.8 1903.36  3706.8 1900.32  3762.4 1903.52  3798.0 1899.84  3838.8 1899.19
  3842.2 1901.48  3879.7 1898.17  3884.8 1900.51  3978.5 1900.99  4130.0 1902.39
  4237.2 1898.65  4647.0 1898.85  4747.4 1893.36  4891.6 1890.25  4938.3 1892.86
  4996.8 1889.03  4997.2 1888.53  5002.0 1889.03  5030.2 1892.72  5257.1 1897.06
#Mann=6,-1,0
  3262.4   0.035       0  3842.2    0.07       0  3978.5   0.035       0
  4237.2    0.07       0  4996.8    0.07       0  5002.0    0.07       0
Bank Sta=4996.8,5002
Exp/Cntr=0.3,0.1

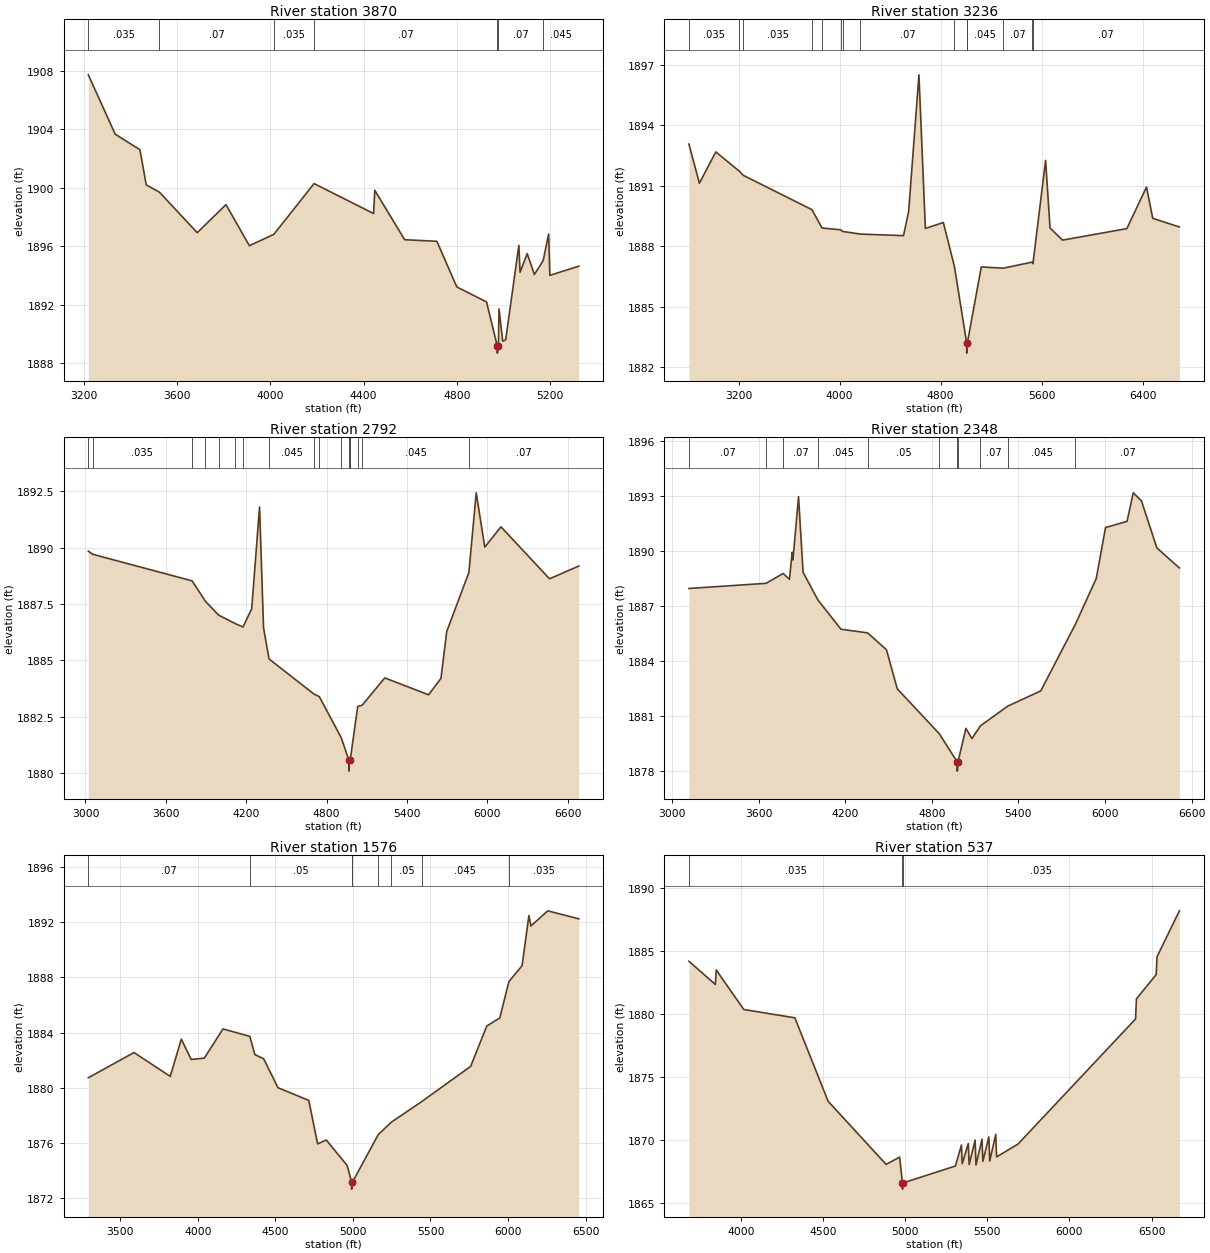
Type RM Length L Ch R = 1,3870,634,634,634
BEGIN DESCRIPTION:
Clear Fork Trib2_4 6.0
END DESCRIPTION:
XS GIS Cut Line= 3
      1416670.85      6971769.37      1414934.72      6971368.12
      1414619.23      6971294.76
#Sta/Elev= 30
  3218.1 1907.72  3333.5 1903.66  3439.6 1902.60  3466.9 1900.19  3523.7 1899.69
  3685.7 1896.92  3809.1 1898.84  3909.6 1896.03  4014.9 1896.81  4187.3 1900.28
  4442.9 1898.23  4448.0 1899.82  4576.2 1896.44  4714.7 1896.33  4800.1 1893.21
  4927.9 1892.18  4973.6 1889.18  4974.0 1888.68  4978.8 1889.18  4981.3 1891.70
  4997.3 1889.50  5010.0 1889.59  5066.6 1896.06  5071.7 1894.21  5102.4 1895.49
  5133.2 1894.06  5171.0 1895.01  5194.4 1896.83  5199.6 1894.00  5323.9 1894.63
#Mann=7,-1,0
  3218.1   0.035       0  3523.7    0.07       0  4014.9   0.035       0
  4187.3    0.07       0  4973.6    0.07       0  4978.8    0.07       0
  5171.0   0.045       0
Bank Sta=4973.6,4978.8
Exp/Cntr=0.3,0.1

Type RM Length L Ch R = 1,3236,444,444,444
BEGIN DESCRIPTION:
Clear Fork Trib2_4 5.0
END DESCRIPTION:
XS GIS Cut Line= 3
      1416904.19      6970377.85      1414755.00      6970788.00
      1413561.37      6971992.74
#Sta/Elev= 30
  2807.0 1893.07  2890.3 1891.13  3020.0 1892.68  3205.6 1891.73  3237.6 1891.52
  3780.8 1889.82  3861.5 1888.91  4009.9 1888.82  4023.4 1888.74  4165.0 1888.61
  4506.3 1888.53  4547.0 1889.73  4628.5 1896.50  4679.4 1888.89  4821.9 1889.18
  4908.9 1887.02  5006.5 1883.21  5006.9 1882.71  5011.7 1883.21  5122.2 1886.98
  5297.0 1886.92  5524.4 1887.22  5531.2 1887.14  5631.4 1892.26  5666.7 1888.91
  5765.7 1888.31  6274.9 1888.88  6430.4 1890.94  6479.9 1889.39  6690.9 1888.96
#Mann=14,-1,0
  2807.0   0.035       0  3205.6    0.07       0  3237.6   0.035       0
  3780.8    0.07       0  3861.5   0.035       0  4009.9    0.07       0
  4023.4   0.035       0  4165.0    0.07       0  4908.9   0.045       0
  5006.5   0.045       0  5011.7   0.045       0  5297.0    0.07       0
  5524.4   0.045       0  5531.2    0.07       0
Bank Sta=5006.5,5011.7
Exp/Cntr=0.3,0.1

Type RM Length L Ch R = 1,2792,444,444,444
BEGIN DESCRIPTION:
Clear Fork Trib2_4 4.0
END DESCRIPTION:
XS GIS Cut Line= 3
      1416452.02      6970087.16      1414505.00      6970438.00
      1413432.74      6971733.68
#Sta/Elev= 30
  3021.4 1889.85  3054.6 1889.71  3795.8 1888.53  3895.8 1887.62  3993.4 1887.01
  4118.9 1886.63  4175.3 1886.48  4240.6 1887.29  4299.3 1891.81  4329.1 1886.44
  4370.3 1885.06  4706.2 1883.50  4745.0 1883.39  4908.5 1881.57  4965.3 1880.58
  4965.7 1880.08  4970.5 1880.58  4976.9 1880.62  5031.6 1882.95  5065.4 1883.01
  5233.6 1884.22  5560.5 1883.47  5653.0 1884.20  5696.0 1886.28  5861.2 1888.90
  5916.1 1892.44  5979.9 1890.03  6101.1 1890.93  6463.2 1888.62  6681.6 1889.19
#Mann=17,-1,0
  3021.4    0.07       0  3054.6   0.035       0  3795.8    0.07       0
  3895.8   0.035       0  3993.4    0.07       0  4118.9   0.035       0
  4175.3    0.07       0  4370.3   0.045       0  4706.2    0.05       0
  4745.0   0.045       0  4908.5    0.05       0  4965.3   0.045       0
  4970.5    0.05       0  4976.9   0.045       0  5031.6    0.05       0
  5065.4   0.045       0  5861.2    0.07       0
Bank Sta=4965.3,4970.5
Exp/Cntr=0.3,0.1

Type RM Length L Ch R = 1,2348,772,772,772
BEGIN DESCRIPTION:
Clear Fork Trib2_4 3.0
END DESCRIPTION:
XS GIS Cut Line= 3
      1416048.34      6969513.86      1414255.00      6970088.00
      1413311.48      6971273.58
#Sta/Elev= 30
  3117.0 1887.96  3651.1 1888.24  3770.0 1888.78  3813.5 1888.46  3832.5 1889.93
  3837.7 1889.52  3876.5 1892.98  3908.0 1888.84  4011.8 1887.32  4170.5 1885.73
  4355.6 1885.53  4485.5 1884.61  4560.7 1882.47  4852.4 1880.01  4976.1 1878.47
  4976.5 1877.97  4981.3 1878.47  5036.0 1880.31  5077.7 1879.75  5137.1 1880.45
  5324.9 1881.52  5555.0 1882.36  5795.1 1886.01  5939.4 1888.51  6003.5 1891.29
  6152.4 1891.63  6195.7 1893.19  6252.5 1892.75  6359.0 1890.18  6515.2 1889.08
#Mann=11,-1,0
  3117.0    0.07       0  3651.1   0.035       0  3770.0    0.07       0
  4011.8   0.045       0  4355.6    0.05       0  4852.4   0.045       0
  4976.1   0.045       0  4981.3   0.045       0  5137.1    0.07       0
  5324.9   0.045       0  5795.1    0.07       0
Bank Sta=4976.1,4981.3
Exp/Cntr=0.3,0.1

Type RM Length L Ch R = 1,1576,1039,1039,1039
BEGIN DESCRIPTION:
Mapping XS ad3f6924
END DESCRIPTION:
XS GIS Cut Line= 3
      1415240.88      6968318.82      1413948.94      6969425.04
      1413327.18      6970749.31
#Sta/Elev= 30
  3293.0 1880.73  3587.7 1882.56  3821.5 1880.83  3892.8 1883.53  3956.5 1882.06
  4041.0 1882.15  4161.7 1884.27  4334.8 1883.73  4367.1 1882.41  4424.1 1882.11
  4516.3 1880.01  4715.0 1879.09  4772.0 1875.94  4828.0 1876.22  4963.0 1874.37
  4991.1 1873.16  4991.6 1872.66  4996.5 1873.16  5163.5 1876.62  5248.6 1877.52
  5443.0 1879.00  5759.4 1881.56  5863.1 1884.48  5947.2 1885.07  6005.8 1887.70
  6090.8 1888.85  6135.0 1892.49  6147.9 1891.73  6256.4 1892.83  6456.8 1892.25
#Mann=8,-1,0
  3293.0    0.07       0  4334.8    0.05       0  4991.1    0.05       0
  4996.5    0.05       0  5163.5   0.045       0  5248.6    0.05       0
  5443.0   0.045       0  6005.8   0.035       0
Bank Sta=4991.1,4996.5
Exp/Cntr=0.3,0.1

Type RM Length L Ch R = 1,537,71,71,71
BEGIN DESCRIPTION:
Mapping XS 58279fd2
END DESCRIPTION:
XS GIS Cut Line= 3
      1414158.69      6967260.75      1413853.14      6968531.59
      1413457.36      6970163.31
#Sta/Elev= 30
  3683.3 1884.17  3844.4 1882.33  3849.5 1883.48  4017.3 1880.35  4328.4 1879.69
  4531.1 1873.08  4883.8 1868.09  4966.1 1868.66  4983.2 1866.63  4983.6 1866.13
  4988.6 1866.63  5305.7 1867.96  5342.4 1869.62  5347.5 1868.15  5384.2 1869.74
  5389.3 1868.08  5425.9 1870.01  5431.1 1868.04  5467.7 1870.08  5472.9 1868.33
  5509.5 1870.26  5514.7 1868.35  5551.3 1870.46  5556.5 1868.68  5687.0 1869.70
  6402.6 1879.60  6407.7 1881.19  6528.0 1883.11  6533.1 1884.52  6669.4 1888.16
#Mann=3,-1,0
  3683.3   0.035       0  4983.2   0.035       0  4988.6   0.035       0
Bank Sta=4983.2,4988.6
Exp/Cntr=0.3,0.1

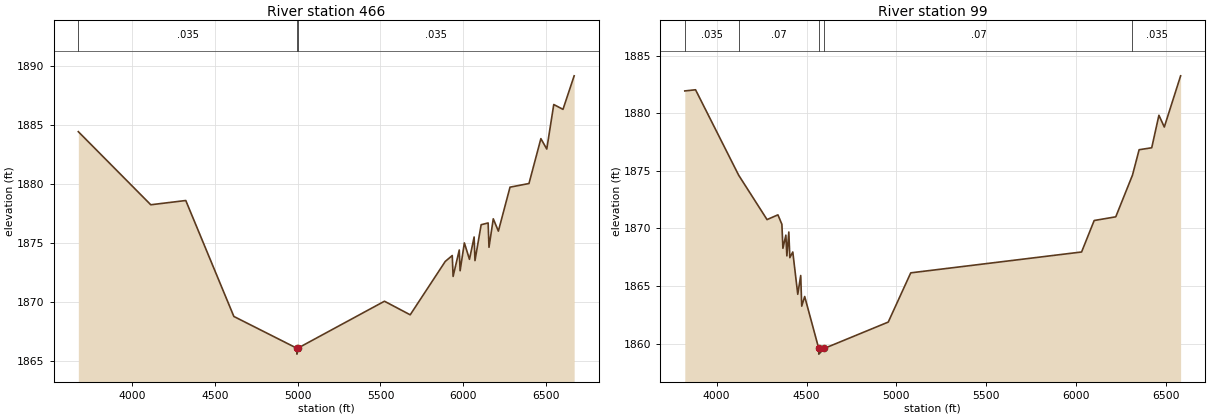
Type RM Length L Ch R = 1,466,367,367,367
BEGIN DESCRIPTION:
Clear Fork Trib2_4 1.0
END DESCRIPTION:
XS GIS Cut Line= 3
      1414075.65      6967224.56      1413785.12      6968517.72
      1413401.93      6970143.68
#Sta/Elev= 30
  3674.6 1884.42  4112.3 1878.23  4323.8 1878.59  4614.4 1868.77  4994.9 1866.08
  4995.3 1865.58  5000.3 1866.08  5524.3 1870.06  5679.9 1868.91  5891.6 1873.43
  5933.9 1873.93  5939.1 1872.16  5976.3 1874.40  5981.4 1872.64  6007.1 1875.00
  6038.0 1873.61  6066.1 1875.50  6071.2 1873.50  6108.5 1876.54  6150.8 1876.69
  6155.9 1874.63  6181.8 1877.04  6212.6 1876.00  6283.0 1879.72  6397.5 1880.03
  6469.5 1883.83  6505.0 1882.95  6547.3 1886.72  6603.0 1886.31  6670.5 1889.15
#Mann=3,-1,0
  3674.6   0.035       0  4994.9   0.035       0  5000.3   0.035       0
Bank Sta=4994.9,5000.3
Exp/Cntr=0.3,0.1

Type RM Length L Ch R = 1,99,0,0,0
BEGIN DESCRIPTION:
Mapping XS 22fd5331
END DESCRIPTION:
XS GIS Cut Line= 3
      1414020.91      6967314.97      1413474.98      6968358.05
      1413417.61      6969938.71
#Sta/Elev= 30
  3822.7 1881.93  3882.5 1882.03  4122.5 1874.62  4280.4 1870.77  4340.9 1871.18
  4363.0 1870.36  4368.7 1868.28  4385.1 1869.42  4390.7 1867.62  4401.5 1869.69
  4407.2 1867.47  4423.6 1867.96  4451.3 1864.29  4467.7 1865.92  4473.4 1863.26
  4489.8 1864.10  4567.9 1859.60  4568.4 1859.10  4599.5 1859.60  4954.8 1861.88
  5080.0 1866.15  6030.6 1867.96  6100.7 1870.69  6220.8 1871.01  6313.7 1874.62
  6350.8 1876.83  6420.9 1877.00  6460.9 1879.82  6490.9 1878.80  6581.7 1883.24
#Mann=5,-1,0
  3822.7   0.035       0  4122.5    0.07       0  4567.9    0.07       0
  4599.5    0.07       0  6313.7   0.035       0
Bank Sta=4567.9,4599.5
Exp/Cntr=0.3,0.1

Chan Stop Cuts=-1