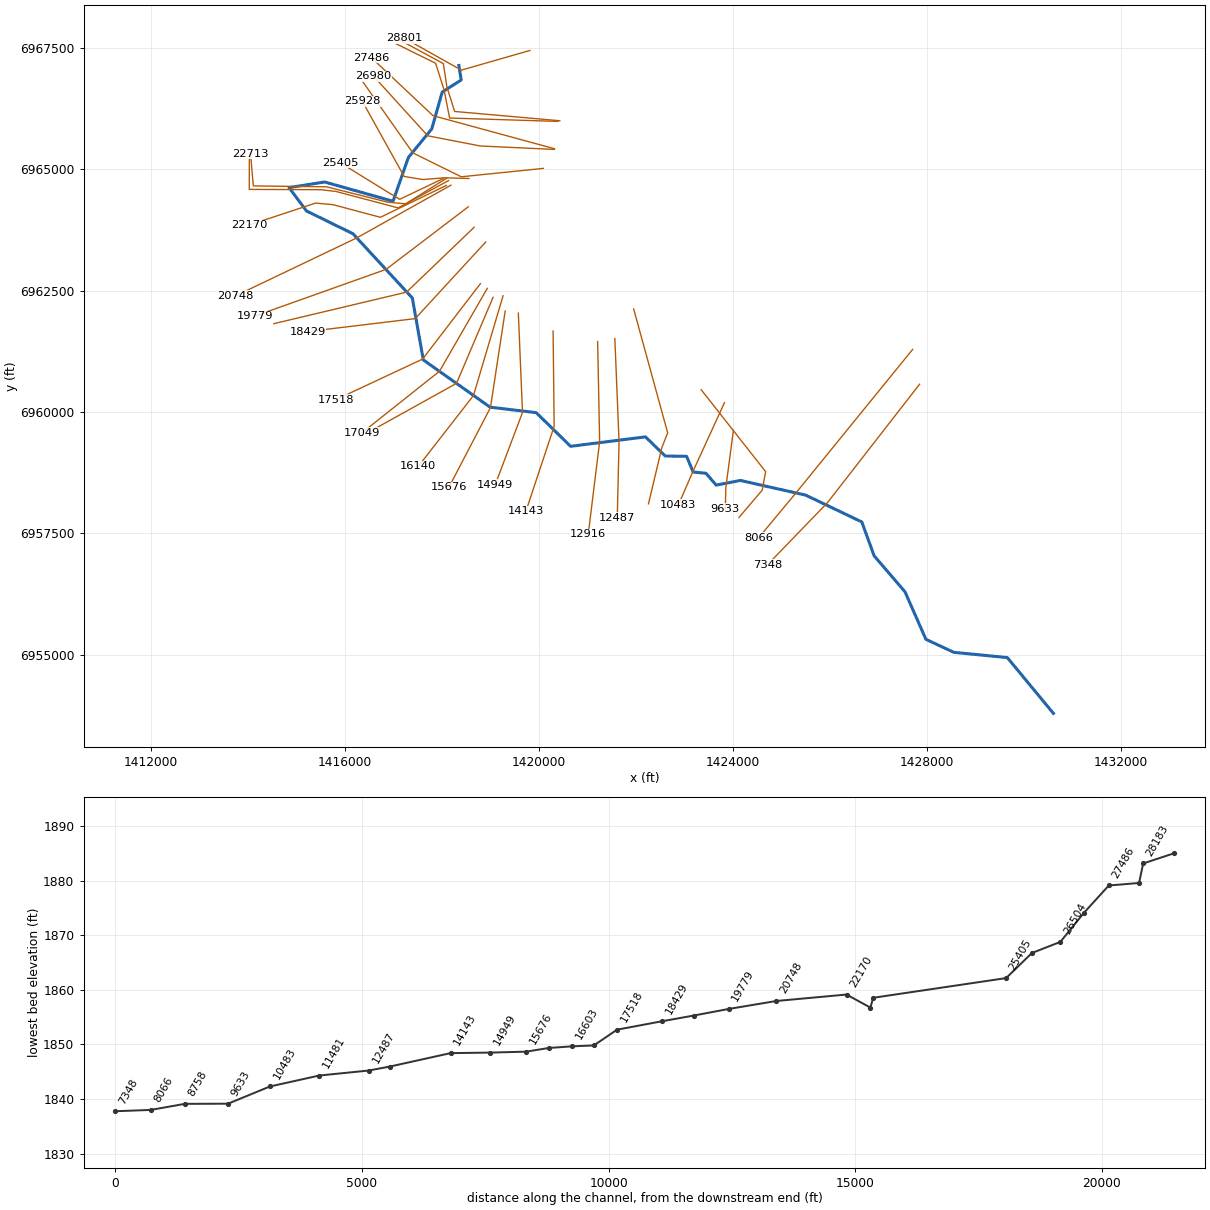
--- Clear Fork Trib3.prj (project) ---

Proj Title=Clear Fork Trib3 Base Level Engineering
Current Plan=p01
Default Exp/Contr=0.3,0.1
English Units
Geom File=g01
Flow File=f01
Plan File=p01
BEGIN DESCRIPTION:
Clear Fork Trib3
END DESCRIPTION:

--- Clear Fork Trib3.p01 (plan) ---

Plan Title=Multiple Run
Short Identifier=Multiple
Geom File=g01
Flow File=f01
Subcritical Flow
K Sum by GR= 0
Std Step Tol= 0.01
Critical Tol= 0.01
Num of Std Step Trials= 20
Max Error Tol= 0.3
Flow Tol Ratio= 0.001
Split Flow NTrial= 30
Split Flow Tol= 0.02
Split Flow Ratio= 0.02
Log Output Level= 0
Friction Slope Method= 1
Unsteady Friction Slope Method= 2
Unsteady Bridges Friction Slope Method= 1
Parabolic Critical Depth
Global Vel Dist=  1 , 1 , 1
Global Log Level= 0
CheckData=True
Encroach Param= -1, 0, 0, 0
BEGIN DESCRIPTION:
Multiple Run
END DESCRIPTION:

--- Clear Fork Trib3.f01 (steady flow) ---

Flow Title=Multiple
Number of Profiles=7
Profile Names=10-year,25-year,50-year,1pct_min,100-year,1pct_plu,500-year
River Rch & RM= Clear Fork Trib3,Reach-1,28801
     216     299     368     225     449     895     676
River Rch & RM= Clear Fork Trib3,Reach-1,28183
     437     626     787     491     979    1954    1536
River Rch & RM= Clear Fork Trib3,Reach-1,19070
     455     651     816     508    1014    2023    1584
River Rch & RM= Clear Fork Trib3,Reach-1,12916
     536     772     973     608    1212    2419    1909
River Rch & RM= Clear Fork Trib3,Reach-1,10483
     624     905    1146     719    1435    2862    2278
River Rch & RM= Clear Fork Trib3,Reach-1,8758
     620     898    1136     712    1420    2833    2249
River Rch & RM= Clear Fork Trib3,Reach-1,7348
     758    1104    1401     880    1757    3505    2800
River Rch & RM= Clear Fork Trib3,Reach-1,1198
     866    1269    1618    1021    2038    4066    3276
Boundary for River Rch & Prof#=Clear Fork Trib3,Reach-1,1
Up Type=0
Dn Type=3
Dn Slope=0.005
Boundary for River Rch & Prof#=Clear Fork Trib3,Reach-1,2
Up Type=0
Dn Type=3
Dn Slope=0.005
Boundary for River Rch & Prof#=Clear Fork Trib3,Reach-1,3
Up Type=0
Dn Type=3
Dn Slope=0.005
Boundary for River Rch & Prof#=Clear Fork Trib3,Reach-1,4
Up Type=0
Dn Type=3
Dn Slope=0.005
Boundary for River Rch & Prof#=Clear Fork Trib3,Reach-1,5
Up Type=0
Dn Type=3
Dn Slope=0.005
Boundary for River Rch & Prof#=Clear Fork Trib3,Reach-1,6
Up Type=0
Dn Type=3
Dn Slope=0.005
Boundary for River Rch & Prof#=Clear Fork Trib3,Reach-1,7
Up Type=0
Dn Type=3
Dn Slope=0.005

--- Clear Fork Trib3.g01 (geometry) ---

Geom Title=Existing Conditions

River Reach=Clear Fork Trib3,Reach-1
Reach XY= 30
      1418355.00      6967138.00      1418401.84      6966839.62
      1418010.52      6966590.43      1417795.41      6965831.45
      1417314.30      6965244.67      1416997.41      6964340.96
      1415589.78      6964737.75      1414854.84      6964622.77
      1415213.48      6964141.51      1416171.68      6963671.36
      1417394.80      6962347.68      1417621.64      6961071.32
      1418998.26      6960097.13      1419947.03      6959985.07
      1420656.65      6959291.10      1422199.15      6959485.94
      1422606.22      6959091.44      1423046.72      6959084.94
      1423181.41      6958760.84      1423447.03      6958735.07
      1423656.56      6958491.76      1424155.00      6958588.00
      1425499.06      6958285.74      1426657.40      6957732.46
      1426910.83      6957035.70      1427546.86      6956294.06
      1427978.18      6955314.30      1428551.70      6955046.08
      1429655.00      6954938.00      1430605.00      6953788.00

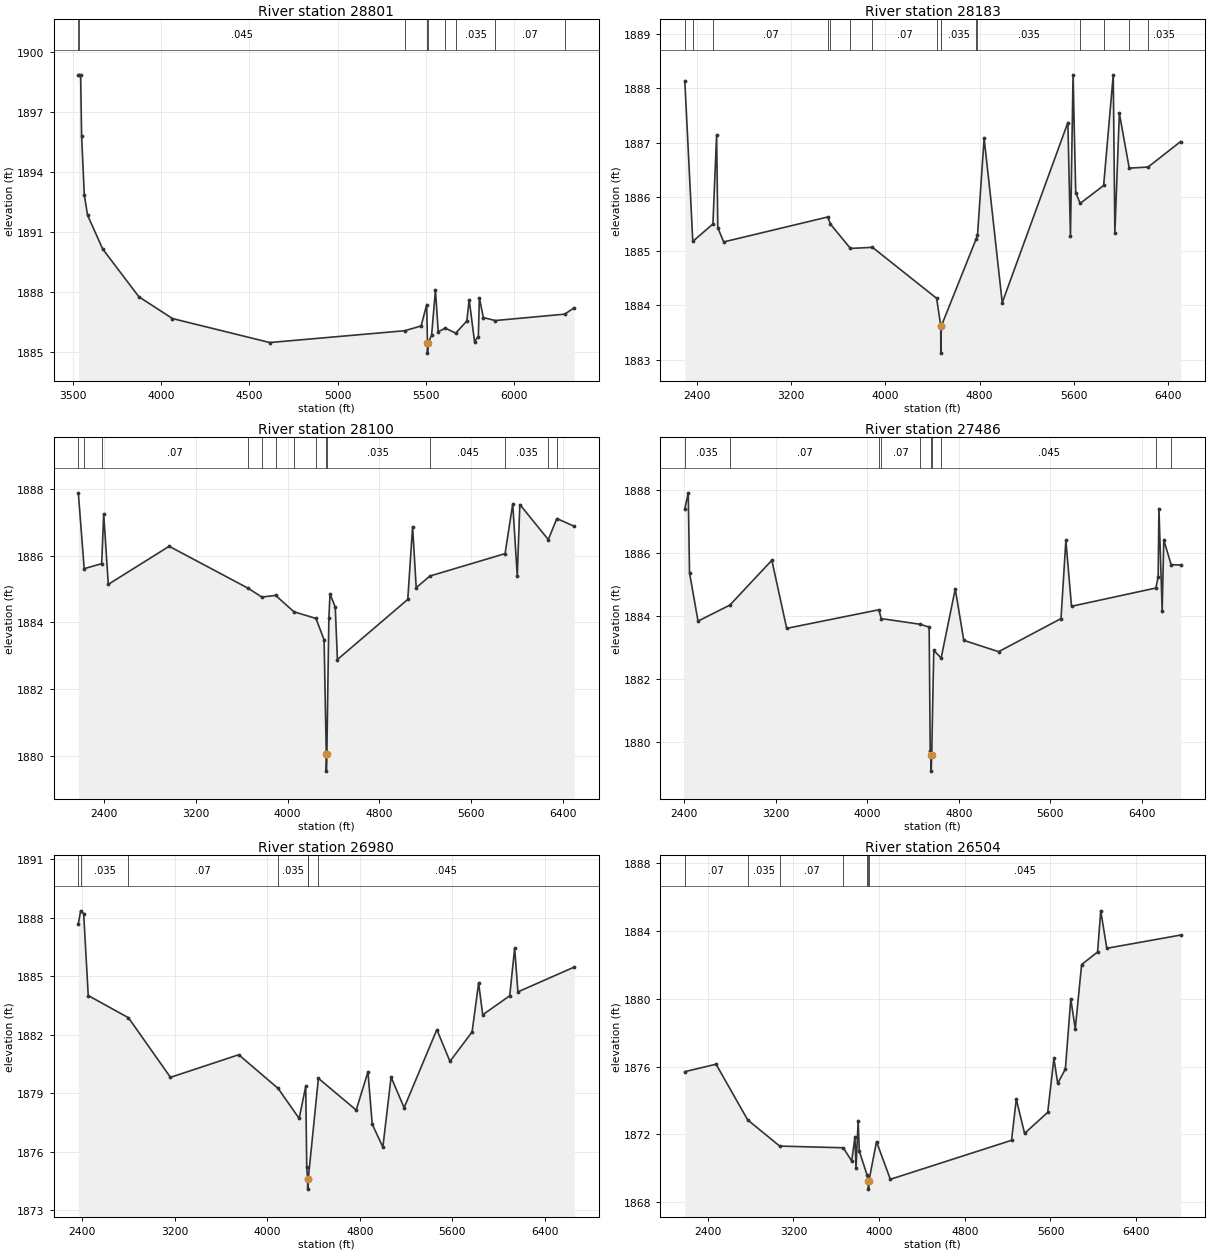
Type RM Length L Ch R = 1,28801,618,618,618
BEGIN DESCRIPTION:
Clear Fork Trib3 31.0
END DESCRIPTION:
XS GIS Cut Line= 3
      1419817.59      6967448.18      1418405.78      6967042.98
      1417236.07      6967698.15
#Sta/Elev= 30
  3531.2 1898.88  3537.3 1898.88  3544.3 1898.86  3549.7 1895.84  3565.1 1892.87
  3583.5 1891.86  3669.1 1890.17  3874.1 1887.78  4064.5 1886.69  4615.9 1885.49
  5380.4 1886.08  5473.6 1886.32  5505.2 1887.39  5509.3 1885.46  5509.5 1884.96
  5513.3 1885.46  5533.0 1885.87  5554.7 1888.11  5570.6 1886.03  5610.5 1886.21
  5669.8 1885.96  5732.7 1886.57  5745.9 1887.64  5776.1 1885.54  5797.8 1885.79
  5803.5 1887.73  5826.1 1886.74  5893.3 1886.59  6287.6 1886.91  6340.7 1887.23
#Mann=9,-1,0
  3531.2    0.07       0  3537.3   0.045       0  5380.4   0.035       0
  5509.3   0.045       0  5513.3   0.035       0  5610.5   0.045       0
  5669.8   0.035       0  5893.3    0.07       0  6287.6   0.035       0
Bank Sta=5509.3,5513.3
Exp/Cntr=0.3,0.1

Type RM Length L Ch R = 1,28183,83,83,83
BEGIN DESCRIPTION:
Mapping XS a4f77552
END DESCRIPTION:
XS GIS Cut Line= 5
      1420433.89      6966000.07      1418267.30      6966191.22
      1418108.32      6966691.35      1418034.66      6967177.33
      1417142.34      6967659.95
#Sta/Elev= 30
  2300.2 1888.14  2368.0 1885.18  2538.7 1885.50  2570.1 1887.14  2580.2 1885.43
  2630.4 1885.17  3513.3 1885.63  3535.1 1885.50  3705.3 1885.05  3892.3 1885.07
  4436.4 1884.13  4471.4 1883.62  4471.7 1883.12  4476.3 1883.62  4772.5 1885.23
  4783.0 1885.29  4839.1 1887.08  4992.8 1884.05  5549.6 1887.37  5571.5 1885.27
  5593.5 1888.24  5616.2 1886.08  5653.7 1885.88  5853.0 1886.21  5934.5 1888.25
  5948.2 1885.34  5986.3 1887.54  6070.1 1886.53  6229.7 1886.55  6506.0 1887.02
#Mann=16,-1,0
  2300.2    0.07       0  2368.0   0.035       0  2538.7    0.07       0
  3513.3   0.035       0  3535.1    0.07       0  3705.3   0.035       0
  3892.3    0.07       0  4436.4   0.035       0  4471.4   0.035       0
  4476.3   0.035       0  4772.5    0.07       0  4783.0   0.035       0
  5653.7   0.045       0  5853.0   0.035       0  6070.1    0.07       0
  6229.7   0.035       0
Bank Sta=4471.4,4476.3
Exp/Cntr=0.3,0.1

Type RM Length L Ch R = 1,28100,614,614,614
BEGIN DESCRIPTION:
Mapping XS c92c992c
END DESCRIPTION:
XS GIS Cut Line= 5
      1420395.76      6965986.36      1418163.14      6966055.80
      1418048.55      6966639.13      1417874.94      6967184.27
      1417052.05      6967590.51
#Sta/Elev= 30
  2177.9 1887.88  2228.9 1885.61  2381.2 1885.76  2398.8 1887.25  2438.8 1885.14
  2969.0 1886.28  3658.7 1885.02  3776.0 1884.76  3896.0 1884.81  4055.4 1884.32
  4247.4 1884.12  4318.1 1883.48  4337.3 1880.05  4337.6 1879.55  4342.2 1880.05
  4359.7 1884.12  4369.7 1884.85  4415.3 1884.46  4434.2 1882.89  5046.9 1884.69
  5088.9 1886.87  5120.3 1885.04  5240.0 1885.39  5894.3 1886.06  5961.1 1887.55
  6000.4 1885.39  6022.9 1887.53  6270.8 1886.48  6345.2 1887.11  6495.9 1886.88
#Mann=14,-1,0
  2177.9    0.07       0  2228.9   0.035       0  2381.2    0.07       0
  3658.7   0.035       0  3776.0    0.07       0  3896.0   0.035       0
  4055.4    0.07       0  4247.4   0.035       0  4337.3   0.035       0
  4342.2   0.035       0  5240.0   0.045       0  5894.3   0.035       0
  6270.8    0.07       0  6345.2   0.035       0
Bank Sta=4337.3,4342.2
Exp/Cntr=0.3,0.1

Type RM Length L Ch R = 1,27486,506,506,506
BEGIN DESCRIPTION:
Clear Fork Trib3 30.0
END DESCRIPTION:
XS GIS Cut Line= 3
      1420324.15      6965423.33      1417821.23      6966104.67
      1416555.33      6967295.97
#Sta/Elev= 30
  2406.0 1887.41  2436.2 1887.92  2447.3 1885.38  2521.6 1883.85  2800.4 1884.36
  3166.5 1885.78  3296.4 1883.62  4102.0 1884.21  4122.1 1883.93  4461.4 1883.75
  4541.0 1883.66  4550.4 1879.72  4558.3 1879.59  4558.7 1879.09  4563.3 1879.59
  4581.5 1882.92  4645.9 1882.68  4769.2 1884.87  4843.6 1883.24  5148.1 1882.88
  5693.1 1883.93  5735.6 1886.41  5785.0 1884.32  6522.2 1884.90  6542.0 1885.26
  6548.8 1887.42  6577.1 1884.18  6591.3 1886.42  6655.6 1885.64  6738.3 1885.63
#Mann=10,-1,0
  2406.0   0.035       0  2800.4    0.07       0  4102.0   0.035       0
  4122.1    0.07       0  4461.4   0.035       0  4558.3   0.045       0
  4563.3   0.035       0  4645.9   0.045       0  6522.2   0.035       0
  6655.6    0.07       0
Bank Sta=4558.3,4563.3
Exp/Cntr=0.3,0.1

Type RM Length L Ch R = 1,26980,476,476,476
BEGIN DESCRIPTION:
Mapping XS c620ed76
END DESCRIPTION:
XS GIS Cut Line= 4
      1420321.19      6965408.79      1418796.23      6965480.07
      1417712.55      6965689.44      1416597.13      6966917.70
#Sta/Elev= 30
  2365.6 1887.69  2385.5 1888.36  2411.8 1888.22  2451.3 1884.01  2799.3 1882.87
  3162.7 1879.81  3753.3 1880.97  4094.2 1879.24  4276.0 1877.70  4333.0 1879.35
  4341.6 1875.20  4349.3 1874.57  4349.7 1874.07  4354.3 1874.57  4442.5 1879.76
  4769.4 1878.13  4871.2 1880.09  4908.1 1877.40  5000.2 1876.23  5071.2 1879.82
  5184.1 1878.25  5467.2 1882.26  5580.7 1880.63  5772.0 1882.14  5828.7 1884.66
  5863.9 1883.02  6097.7 1884.00  6140.3 1886.44  6168.6 1884.20  6655.1 1885.47
#Mann=7,-1,0
  2365.6    0.07       0  2385.5   0.035       0  2799.3    0.07       0
  4094.2   0.035       0  4349.3   0.045       0  4354.3   0.035       0
  4442.5   0.045       0
Bank Sta=4349.3,4354.3
Exp/Cntr=0.3,0.1

Type RM Length L Ch R = 1,26504,576,576,576
BEGIN DESCRIPTION:
Clear Fork Trib3 29.0
END DESCRIPTION:
XS GIS Cut Line= 4
      1420095.43      6965018.16      1418403.30      6964845.20
      1417405.00      6965338.00      1416361.17      6966823.35
#Sta/Elev= 30
  2185.7 1875.70  2477.6 1876.14  2773.4 1872.85  3071.8 1871.31  3665.3 1871.21
  3744.2 1870.43  3774.4 1871.84  3784.4 1870.01  3804.5 1872.81  3814.8 1871.01
  3888.6 1869.59  3900.4 1869.27  3900.8 1868.77  3905.4 1869.27  3975.8 1871.57
  4104.9 1869.35  5236.5 1871.65  5280.9 1874.07  5358.5 1872.06  5574.4 1873.30
  5632.1 1876.48  5667.8 1875.01  5739.3 1875.86  5789.8 1879.99  5831.6 1878.22
  5890.9 1882.02  6039.9 1882.76  6069.5 1885.19  6126.1 1882.98  6815.4 1883.76
#Mann=7,-1,0
  2185.7    0.07       0  2773.4   0.035       0  3071.8    0.07       0
  3665.3   0.035       0  3888.6   0.045       0  3900.4   0.045       0
  3905.4   0.045       0
Bank Sta=3900.4,3905.4
Exp/Cntr=0.3,0.1

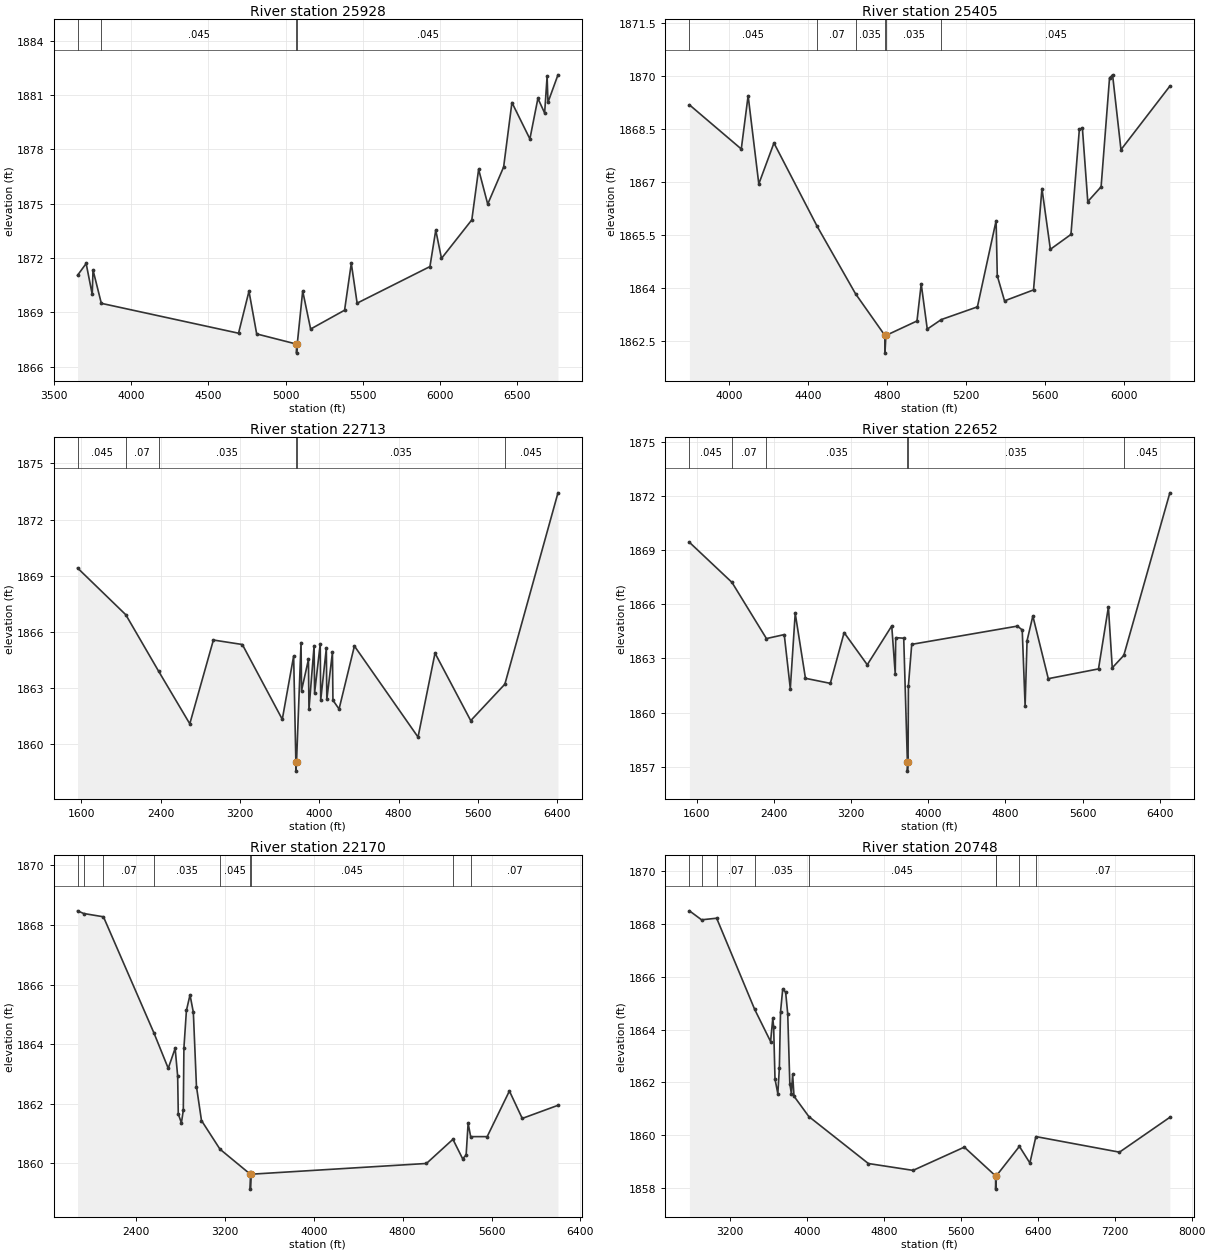
Type RM Length L Ch R = 1,25928,523,523,523
BEGIN DESCRIPTION:
Mapping XS eaf309cf
END DESCRIPTION:
XS GIS Cut Line= 5
      1418560.55      6964810.27      1418055.35      6964824.16
      1417611.87      6964788.46      1417226.44      6964851.77
      1416367.08      6966396.86
#Sta/Elev= 30
  3653.4 1871.04  3709.0 1871.69  3748.4 1869.98  3753.4 1871.33  3807.2 1869.49
  4695.1 1867.84  4762.7 1870.16  4812.5 1867.80  5070.0 1867.24  5070.4 1866.74
  5075.0 1867.24  5110.3 1870.17  5161.6 1868.07  5381.3 1869.11  5424.8 1871.70
  5462.5 1869.50  5933.7 1871.52  5971.4 1873.53  6008.4 1871.97  6204.7 1874.10
  6248.7 1876.89  6307.6 1874.97  6410.6 1877.02  6464.3 1880.58  6580.5 1878.57
  6632.4 1880.81  6675.9 1880.00  6691.9 1882.02  6697.6 1880.59  6762.3 1882.11
#Mann=4,-1,0
  3653.4   0.035       0  3807.2   0.045       0  5070.0   0.045       0
  5075.0   0.045       0
Bank Sta=5070,5075
Exp/Cntr=0.3,0.1

Type RM Length L Ch R = 1,25405,2692,2692,2692
BEGIN DESCRIPTION:
Mapping XS 1c1bb085
END DESCRIPTION:
XS GIS Cut Line= 4
      1418031.64      6964808.94      1417135.83      6964381.86
      1416943.12      6964496.45      1415910.78      6965133.53
#Sta/Elev= 30
  3801.2 1869.18  4063.4 1867.93  4098.0 1869.44  4152.0 1866.94  4228.6 1868.10
  4447.1 1865.74  4641.3 1863.83  4789.8 1862.65  4790.1 1862.15  4794.8 1862.65
  4952.0 1863.06  4973.4 1864.11  5004.0 1862.83  5074.9 1863.10  5257.6 1863.46
  5352.2 1865.90  5358.1 1864.34  5394.8 1863.63  5541.5 1863.94  5584.0 1866.81
  5626.6 1865.09  5730.7 1865.51  5773.2 1868.49  5788.6 1868.52  5815.8 1866.44
  5883.2 1866.86  5925.8 1869.94  5941.2 1870.03  5983.7 1867.91  6230.9 1869.71
#Mann=6,-1,0
  3801.2   0.045       0  4447.1    0.07       0  4641.3   0.035       0
  4789.8   0.035       0  4794.8   0.035       0  5074.9   0.045       0
Bank Sta=4789.8,4794.8
Exp/Cntr=0.3,0.1

Type RM Length L Ch R = 1,22713,61,61,61
BEGIN DESCRIPTION:
Mapping XS ce539b30
END DESCRIPTION:
XS GIS Cut Line= 6
      1418103.98      6964816.82      1417257.57      6964287.54
      1416886.47      6964322.26      1415625.62      6964639.10
      1414118.12      6964657.21      1414061.39      6965317.45
#Sta/Elev= 30
  1563.9 1869.41  2050.4 1866.91  2381.2 1863.89  2695.3 1861.08  2933.1 1865.56
  3225.0 1865.32  3627.7 1861.32  3742.2 1864.70  3764.6 1859.05  3765.1 1858.55
  3771.4 1859.05  3816.8 1865.42  3822.0 1862.86  3891.4 1864.52  3896.6 1861.85
  3948.5 1865.26  3953.6 1862.74  4010.1 1865.35  4015.2 1862.35  4071.7 1865.12
  4076.8 1862.38  4133.4 1864.90  4138.4 1862.34  4200.1 1861.87  4354.8 1865.24
  4996.2 1860.37  5167.4 1864.86  5527.4 1861.25  5871.6 1863.20  6407.0 1873.43
#Mann=6,-1,0
  1563.9   0.045       0  2050.4    0.07       0  2381.2   0.035       0
  3764.6   0.035       0  3771.4   0.035       0  5871.6   0.045       0
Bank Sta=3764.6,3771.4
Exp/Cntr=0.3,0.1

Type RM Length L Ch R = 1,22652,482,482,482
BEGIN DESCRIPTION:
Mapping XS a5ba0999
END DESCRIPTION:
XS GIS Cut Line= 6
      1418142.81      6964767.99      1417101.63      6964204.09
      1415822.98      6964542.63      1415513.09      6964579.09
      1414035.12      6964585.29      1414036.87      6965264.65
#Sta/Elev= 30
  1526.8 1869.43  1967.6 1867.21  2324.6 1864.10  2509.1 1864.32  2571.8 1861.33
  2622.7 1865.50  2728.8 1861.90  2986.3 1861.62  3129.4 1864.43  3369.2 1862.65
  3622.8 1864.80  3659.0 1862.15  3664.2 1864.15  3747.0 1864.12  3785.0 1857.26
  3785.5 1856.76  3791.8 1857.26  3795.5 1861.49  3829.8 1863.78  4924.7 1864.79
  4974.7 1864.58  5004.7 1860.36  5024.7 1863.98  5084.7 1865.35  5244.7 1861.88
  5765.0 1862.42  5867.6 1865.85  5907.6 1862.48  6027.3 1863.17  6504.3 1872.17
#Mann=6,-1,0
  1526.8   0.045       0  1967.6    0.07       0  2324.6   0.035       0
  3785.0   0.035       0  3791.8   0.035       0  6027.3   0.045       0
Bank Sta=3785,3791.8
Exp/Cntr=0.3,0.1

Type RM Length L Ch R = 1,22170,1422,1422,1422
BEGIN DESCRIPTION:
Mapping XS bf4393eb
END DESCRIPTION:
XS GIS Cut Line= 5
      1418096.90      6964667.39      1416736.76      6964010.38
      1415760.20      6964270.79      1415402.13      6964303.34
      1414029.56      6963849.81
#Sta/Elev= 30
  1872.2 1868.47  1927.5 1868.38  2105.3 1868.27  2559.5 1864.38  2688.8 1863.19
  2751.0 1863.86  2773.6 1862.93  2779.2 1861.66  2807.3 1861.36  2824.4 1861.78
  2829.9 1863.87  2852.5 1865.13  2884.9 1865.65  2914.8 1865.07  2942.9 1862.58
  2988.1 1861.44  3154.5 1860.48  3428.0 1859.64  3428.5 1859.14  3434.9 1859.64
  5013.8 1860.00  5252.5 1860.81  5339.7 1860.16  5371.3 1860.28  5389.3 1861.35
  5412.2 1860.90  5560.9 1860.90  5761.0 1862.43  5876.8 1861.51  6198.5 1861.95
#Mann=9,-1,0
  1872.2    0.07       0  1927.5   0.045       0  2105.3    0.07       0
  2559.5   0.035       0  3154.5   0.045       0  3428.0   0.045       0
  3434.9   0.045       0  5252.5   0.035       0  5412.2    0.07       0
Bank Sta=3428,3434.9
Exp/Cntr=0.3,0.1

Type RM Length L Ch R = 1,20748,969,969,969
BEGIN DESCRIPTION:
Clear Fork Trib3 27.0
END DESCRIPTION:
XS GIS Cut Line= 3
      1418190.74      6964672.26      1416255.02      6963588.02
      1413752.68      6962392.16
#Sta/Elev= 30
  2781.3 1868.50  2907.3 1868.16  3064.2 1868.22  3458.9 1864.77  3624.6 1863.55
  3647.5 1864.43  3656.5 1864.09  3670.4 1862.13  3699.9 1861.57  3715.8 1862.56
  3727.8 1864.67  3750.7 1865.54  3780.9 1865.42  3802.6 1864.60  3824.3 1861.96
  3840.3 1861.58  3853.8 1862.31  3867.7 1861.48  4021.7 1860.71  4640.4 1858.93
  5104.9 1858.67  5637.6 1859.55  5962.6 1858.46  5963.1 1857.96  5969.6 1858.46
  6210.0 1859.58  6318.9 1858.95  6381.3 1859.95  7249.9 1859.36  7773.4 1860.68
#Mann=9,-1,0
  2781.3    0.07       0  2907.3   0.045       0  3064.2    0.07       0
  3458.9   0.035       0  4021.7   0.045       0  5962.6   0.045       0
  5969.6   0.045       0  6210.0   0.035       0  6381.3    0.07       0
Bank Sta=5962.6,5969.6
Exp/Cntr=0.3,0.1

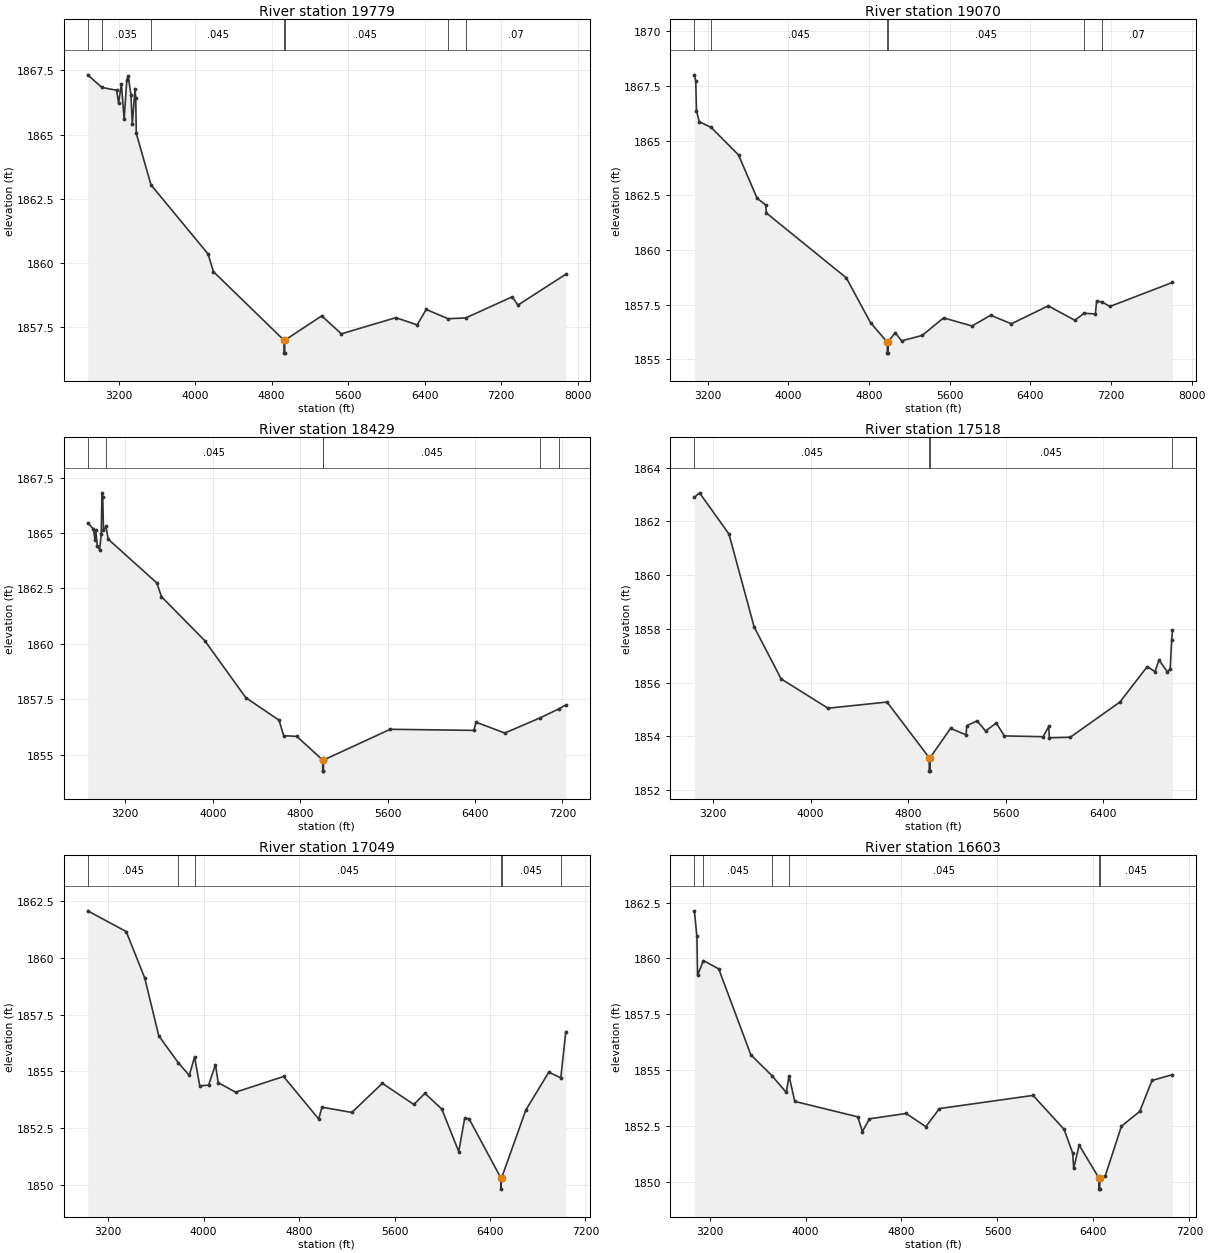
Type RM Length L Ch R = 1,19779,709,709,709
BEGIN DESCRIPTION:
Clear Fork Trib3 26.0
END DESCRIPTION:
XS GIS Cut Line= 3
      1418548.82      6964227.38      1416855.00      6962938.00
      1414150.78      6961974.71
#Sta/Elev= 30
  2876.5 1867.33  3024.2 1866.84  3178.8 1866.73  3199.6 1866.23  3228.7 1866.98
  3257.7 1865.60  3284.9 1867.11  3299.4 1867.30  3328.5 1866.56  3343.0 1865.41
  3371.4 1866.79  3378.4 1866.44  3384.7 1865.05  3537.9 1863.05  4135.1 1860.36
  4191.3 1859.67  4929.9 1857.00  4930.4 1856.50  4936.6 1856.50  4937.1 1857.00
  5323.7 1857.95  5528.7 1857.25  6098.6 1857.88  6321.6 1857.60  6416.3 1858.20
  6644.2 1857.84  6829.8 1857.87  7314.4 1858.69  7376.1 1858.37  7875.9 1859.57
#Mann=7,-1,0
  2876.5   0.045       0  3024.2   0.035       0  3537.9   0.045       0
  4929.9   0.045       0  4937.1   0.045       0  6644.2   0.035       0
  6829.8    0.07       0
Bank Sta=4929.9,4937.1
Exp/Cntr=0.3,0.1

Type RM Length L Ch R = 1,19070,641,641,641
BEGIN DESCRIPTION:
Clear Fork Trib3 25.0
END DESCRIPTION:
XS GIS Cut Line= 3
      1418668.18      6963804.20      1417275.03      6962468.08
      1414541.37      6961818.44
#Sta/Elev= 30
  3069.7 1868.00  3083.5 1867.72  3090.4 1866.35  3118.7 1865.86  3235.9 1865.60
  3507.7 1864.34  3691.7 1862.36  3776.6 1862.06  3783.5 1861.69  4575.7 1858.73
  4816.3 1856.68  4982.4 1855.79  4982.9 1855.29  4989.2 1855.29  4989.7 1855.79
  5060.9 1856.23  5123.4 1855.85  5329.4 1856.10  5540.3 1856.90  5822.3 1856.53
  6007.3 1857.02  6212.9 1856.63  6578.4 1857.45  6841.8 1856.79  6933.2 1857.11
  7045.5 1857.08  7057.8 1857.66  7110.9 1857.63  7189.5 1857.42  7809.8 1858.52
#Mann=6,-1,0
  3069.7   0.035       0  3235.9   0.045       0  4982.4   0.045       0
  4989.7   0.045       0  6933.2   0.035       0  7110.9    0.07       0
Bank Sta=4982.4,4989.7
Exp/Cntr=0.3,0.1

Type RM Length L Ch R = 1,18429,911,911,911
BEGIN DESCRIPTION:
Clear Fork Trib3 24.0
END DESCRIPTION:
XS GIS Cut Line= 3
      1418906.88      6963500.36      1417454.61      6961922.72
      1415239.64      6961655.81
#Sta/Elev= 30
  2855.7 1865.46  2908.3 1865.19  2922.5 1864.69  2929.3 1865.13  2943.5 1864.42
  2965.0 1864.25  2979.2 1864.94  2986.0 1866.82  2993.4 1866.61  3000.2 1865.12
  3023.6 1865.30  3042.7 1864.73  3488.5 1862.75  3531.0 1862.13  3927.4 1860.14
  4302.3 1857.57  4606.8 1856.55  4649.3 1855.85  4769.6 1855.82  5006.0 1854.75
  5006.5 1854.25  5012.9 1854.25  5013.4 1854.75  5624.1 1856.14  6389.6 1856.09
  6409.7 1856.46  6673.0 1855.97  6993.3 1856.65  7170.8 1857.07  7231.0 1857.24
#Mann=6,-1,0
  2855.7   0.035       0  3023.6   0.045       0  5006.0   0.045       0
  5013.4   0.045       0  6993.3   0.035       0  7170.8    0.07       0
Bank Sta=5006,5013.4
Exp/Cntr=0.3,0.1

Type RM Length L Ch R = 1,17518,469,469,469
BEGIN DESCRIPTION:
Clear Fork Trib3 23.0
END DESCRIPTION:
XS GIS Cut Line= 3
      1418798.42      6962643.22      1417605.00      6961088.00
      1415824.61      6960254.23
#Sta/Elev= 30
  3044.8 1862.89  3087.2 1863.06  3328.7 1861.53  3535.8 1858.07  3757.3 1856.14
  4142.2 1855.05  4627.0 1855.28  4973.3 1853.21  4973.8 1852.71  4980.3 1852.71
  4980.8 1853.21  5148.7 1854.30  5276.0 1854.06  5281.5 1854.40  5367.3 1854.58
  5435.8 1854.20  5524.1 1854.50  5590.4 1854.02  5909.0 1853.99  5954.7 1854.37
  5960.2 1853.95  6131.5 1853.97  6540.0 1855.28  6764.1 1856.60  6827.1 1856.41
  6860.9 1856.84  6929.4 1856.40  6952.3 1856.51  6964.0 1857.57  6971.1 1857.94
#Mann=4,-1,0
  3044.8   0.045       0  4973.3   0.045       0  4980.8   0.045       0
  6964.0    0.07       0
Bank Sta=4973.3,4980.8
Exp/Cntr=0.3,0.1

Type RM Length L Ch R = 1,17049,446,446,446
BEGIN DESCRIPTION:
Clear Fork Trib3 22.0
END DESCRIPTION:
XS GIS Cut Line= 3
      1418939.44      6962545.50      1417955.00      6960838.00
      1416361.06      6959572.47
#Sta/Elev= 30
  3029.0 1862.06  3351.6 1861.15  3506.8 1859.11  3624.5 1856.57  3788.6 1855.38
  3880.3 1854.83  3924.7 1855.64  3967.9 1854.37  4041.9 1854.40  4099.6 1855.30
  4122.7 1854.51  4268.1 1854.09  4670.3 1854.78  4964.7 1852.91  4992.1 1853.43
  5242.6 1853.20  5497.9 1854.48  5761.8 1853.55  5854.7 1854.04  5995.9 1853.35
  6138.2 1851.48  6187.9 1852.95  6224.8 1852.92  6490.2 1850.33  6490.7 1849.83
  6497.7 1850.33  6700.6 1853.31  6892.9 1854.97  6993.2 1854.72  7035.2 1856.75
#Mann=6,-1,0
  3029.0   0.045       0  3788.6   0.035       0  3924.7   0.045       0
  6490.2   0.045       0  6497.7   0.045       0  6993.2    0.07       0
Bank Sta=6490.2,6497.7
Exp/Cntr=0.3,0.1

Type RM Length L Ch R = 1,16603,463,463,463
BEGIN DESCRIPTION:
Clear Fork Trib3 21.0
END DESCRIPTION:
XS GIS Cut Line= 3
      1419058.83      6962361.11      1418305.00      6960588.00
      1416505.02      6959588.01
#Sta/Elev= 30
  3073.3 1862.13  3094.4 1860.98  3099.9 1859.24  3148.3 1859.90  3276.2 1859.53
  3543.9 1855.68  3718.7 1854.75  3839.9 1853.99  3862.1 1854.74  3910.8 1853.59
  4435.0 1852.90  4474.5 1852.24  4532.8 1852.81  4838.2 1853.05  5002.9 1852.46
  5116.7 1853.27  5896.9 1853.86  6155.4 1852.34  6227.5 1851.27  6235.5 1850.59
  6281.2 1851.63  6445.6 1850.16  6446.1 1849.66  6452.7 1849.66  6453.2 1850.16
  6498.6 1850.25  6633.6 1852.48  6785.7 1853.14  6888.7 1854.53  7059.1 1854.79
#Mann=6,-1,0
  3073.3   0.035       0  3148.3   0.045       0  3718.7   0.035       0
  3862.1   0.045       0  6445.6   0.045       0  6453.2   0.045       0
Bank Sta=6445.6,6453.2
Exp/Cntr=0.3,0.1

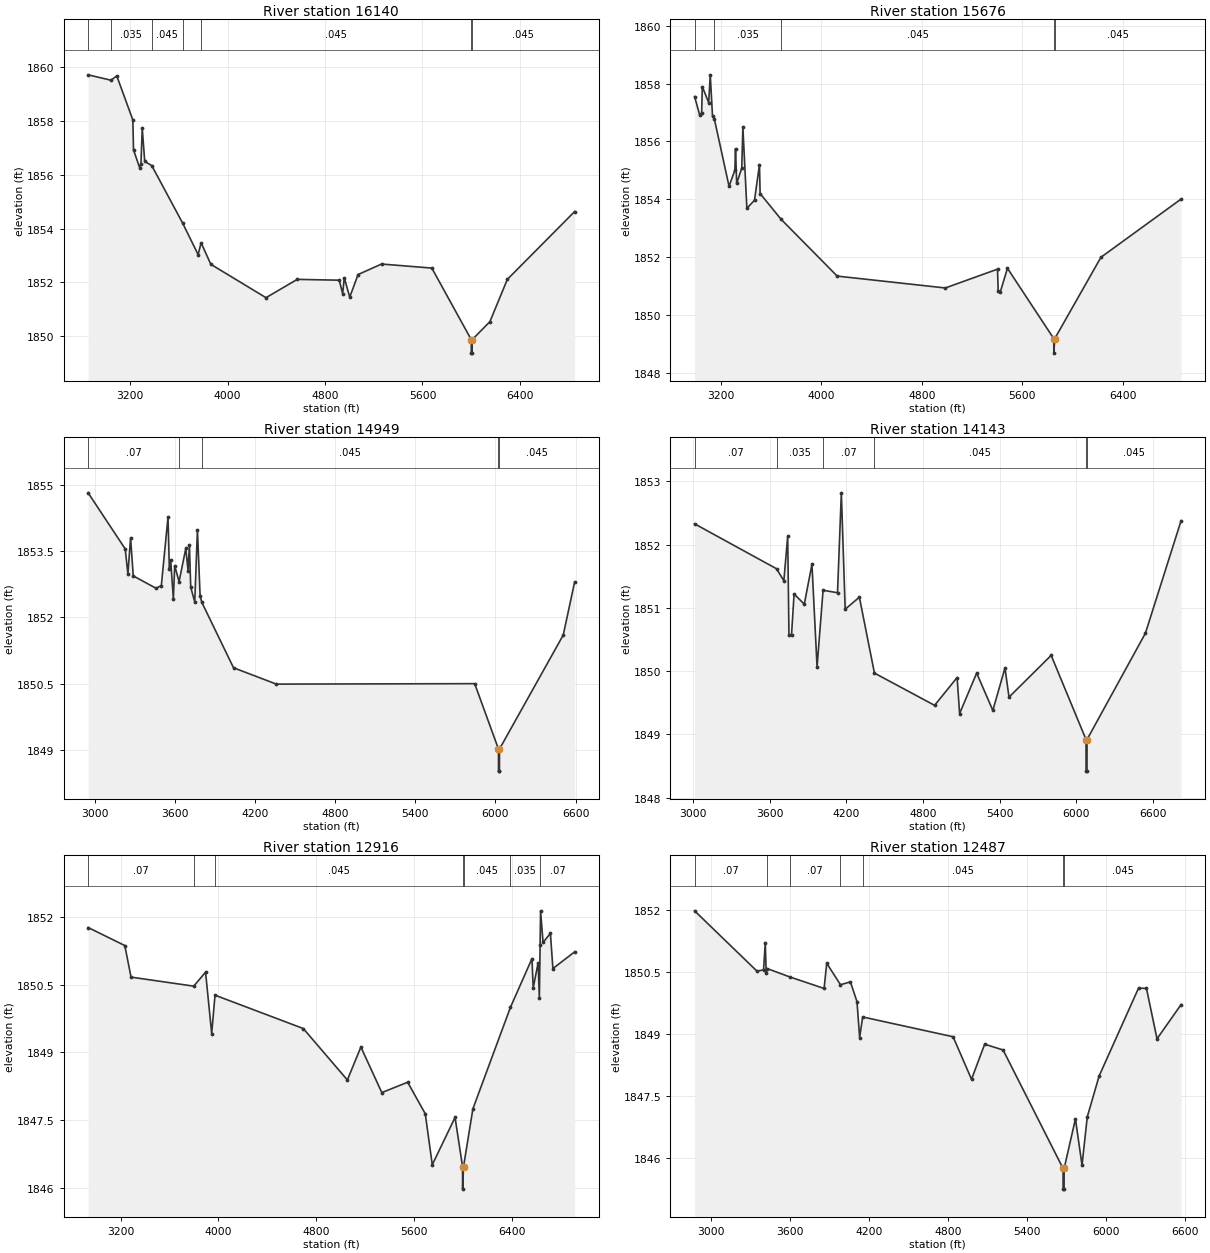
Type RM Length L Ch R = 1,16140,464,464,464
BEGIN DESCRIPTION:
Clear Fork Trib3 20.0
END DESCRIPTION:
XS GIS Cut Line= 3
      1419264.96      6962393.57      1418655.00      6960338.00
      1417519.03      6958879.31
#Sta/Elev= 30
  2855.9 1859.71  3043.2 1859.51  3091.2 1859.67  3223.2 1858.03  3228.4 1856.92
  3279.0 1856.26  3289.4 1856.40  3300.1 1857.72  3320.7 1856.49  3377.9 1856.34
  3630.6 1854.21  3758.8 1853.03  3783.2 1853.47  3863.1 1852.67  4315.7 1851.43
  4572.4 1852.11  4917.0 1852.08  4945.0 1851.58  4958.3 1852.17  5003.2 1851.45
  5071.5 1852.29  5264.3 1852.68  5676.8 1852.53  6000.6 1849.87  6001.1 1849.37
  6007.7 1849.37  6008.2 1849.87  6153.6 1850.54  6296.6 1852.11  6848.9 1854.63
#Mann=7,-1,0
  2855.9    0.07       0  3043.2   0.035       0  3377.9   0.045       0
  3630.6   0.035       0  3783.2   0.045       0  6000.6   0.045       0
  6008.2   0.045       0
Bank Sta=6000.6,6008.2
Exp/Cntr=0.3,0.1

Type RM Length L Ch R = 1,15676,727,727,727
BEGIN DESCRIPTION:
Clear Fork Trib3 19.0
END DESCRIPTION:
XS GIS Cut Line= 3
      1419308.37      6962078.94      1419005.00      6960088.00
      1418147.36      6958443.98
#Sta/Elev= 30
  2993.7 1857.55  3035.1 1856.90  3049.8 1856.99  3055.3 1857.89  3105.9 1857.34
  3118.4 1858.30  3136.3 1856.87  3150.2 1856.79  3267.8 1854.45  3314.1 1855.01
  3319.1 1855.75  3328.5 1854.55  3368.9 1855.08  3377.6 1856.50  3409.4 1853.69
  3470.1 1853.97  3509.7 1855.20  3514.8 1854.20  3681.8 1853.31  4127.6 1851.35
  4987.4 1850.94  5402.2 1851.59  5407.8 1850.83  5424.3 1850.80  5481.3 1851.62
  5849.7 1849.19  5850.2 1848.69  5857.3 1849.19  6224.6 1852.00  6861.9 1854.01
#Mann=5,-1,0
  2993.7    0.07       0  3150.2   0.035       0  3681.8   0.045       0
  5849.7   0.045       0  5857.3   0.045       0
Bank Sta=5849.7,5857.3
Exp/Cntr=0.3,0.1

Type RM Length L Ch R = 1,14949,806,806,806
BEGIN DESCRIPTION:
Clear Fork Trib3 18.0
END DESCRIPTION:
XS GIS Cut Line= 3
      1419579.64      6962035.57      1419664.98      6959987.95
      1419102.21      6958498.20
#Sta/Elev= 30
  2950.6 1854.82  3228.4 1853.55  3248.4 1852.98  3268.4 1853.80  3288.5 1852.94
  3458.6 1852.66  3498.6 1852.72  3548.7 1854.27  3558.7 1853.09  3568.7 1853.29
  3588.7 1852.42  3598.7 1853.17  3631.5 1852.81  3681.7 1853.56  3698.8 1853.06
  3708.8 1853.64  3718.8 1852.68  3748.9 1852.35  3768.9 1853.98  3788.9 1852.49
  3801.8 1852.34  4039.1 1850.86  4359.4 1850.49  5844.4 1850.50  6022.4 1849.02
  6022.9 1848.52  6029.5 1848.52  6030.0 1849.02  6507.2 1851.60  6592.5 1852.80
#Mann=5,-1,0
  2950.6    0.07       0  3631.5   0.035       0  3801.8   0.045       0
  6022.4   0.045       0  6030.0   0.045       0
Bank Sta=6022.4,6030
Exp/Cntr=0.3,0.1

Type RM Length L Ch R = 1,14143,1227,1227,1227
BEGIN DESCRIPTION:
Mapping XS 57d89aab
END DESCRIPTION:
XS GIS Cut Line= 3
      1420295.79      6961666.63      1420317.49      6959702.65
      1419735.67      6957952.95
#Sta/Elev= 30
  3012.5 1852.33  3653.7 1851.62  3711.2 1851.43  3741.2 1852.13  3751.2 1850.58
  3771.2 1850.57  3791.2 1851.22  3871.2 1851.06  3931.2 1851.69  3971.2 1850.07
  4018.2 1851.28  4131.2 1851.24  4161.2 1852.82  4191.2 1850.98  4302.4 1851.17
  4420.3 1849.97  4891.2 1849.46  5067.4 1849.90  5086.9 1849.33  5220.4 1849.97
  5347.0 1849.38  5442.0 1850.05  5473.6 1849.59  5803.5 1850.25  6076.3 1848.92
  6076.8 1848.42  6083.9 1848.42  6084.4 1848.92  6541.2 1850.60  6820.5 1852.38
#Mann=6,-1,0
  3012.5    0.07       0  3653.7   0.035       0  4018.2    0.07       0
  4420.3   0.045       0  6076.3   0.045       0  6084.4   0.045       0
Bank Sta=6076.3,6084.4
Exp/Cntr=0.3,0.1

Type RM Length L Ch R = 1,12916,429,429,429
BEGIN DESCRIPTION:
Clear Fork Trib3 16.0
END DESCRIPTION:
XS GIS Cut Line= 3
      1421213.94      6961449.36      1421255.00      6959388.00
      1421020.57      6957481.43
#Sta/Elev= 30
  2933.3 1851.77  3233.7 1851.37  3284.7 1850.67  3797.9 1850.47  3894.8 1850.78
  3944.9 1849.42  3972.1 1850.27  4695.0 1849.53  5055.5 1848.39  5166.3 1849.12
  5337.6 1848.11  5549.2 1848.34  5693.4 1847.64  5750.7 1846.51  5937.2 1847.56
  5998.5 1846.47  5999.0 1845.97  6006.7 1846.47  6083.2 1847.75  6390.5 1850.00
  6566.8 1851.08  6576.9 1850.43  6617.2 1850.99  6627.3 1850.21  6633.4 1851.39
  6637.3 1852.14  6657.5 1851.44  6717.9 1851.64  6738.1 1850.86  6916.0 1851.23
#Mann=7,-1,0
  2933.3    0.07       0  3797.9   0.035       0  3972.1   0.045       0
  5998.5   0.045       0  6006.7   0.045       0  6390.5   0.035       0
  6633.4    0.07       0
Bank Sta=5998.5,6006.7
Exp/Cntr=0.3,0.1

Type RM Length L Ch R = 1,12487,1006,1006,1006
BEGIN DESCRIPTION:
Clear Fork Trib3 15.0
END DESCRIPTION:
XS GIS Cut Line= 3
      1421568.10      6961511.92      1421655.00      6959388.00
      1421618.03      6957814.93
#Sta/Elev= 30
  2874.3 1851.98  3348.6 1850.52  3398.7 1850.55  3411.8 1851.21  3418.7 1850.48
  3427.4 1850.58  3597.3 1850.38  3859.0 1850.10  3879.1 1850.71  3983.7 1850.19
  4059.2 1850.26  4109.2 1849.78  4129.3 1848.91  4152.3 1849.41  4839.9 1848.93
  4980.0 1847.90  5080.0 1848.75  5220.1 1848.61  5676.1 1845.74  5676.6 1845.24
  5683.8 1845.24  5684.3 1845.74  5770.2 1846.94  5820.2 1845.82  5860.2 1846.99
  5950.3 1847.98  6250.3 1850.11  6310.4 1850.10  6390.4 1848.88  6573.5 1849.71
#Mann=7,-1,0
  2874.3    0.07       0  3427.4   0.035       0  3597.3    0.07       0
  3983.7   0.035       0  4152.3   0.045       0  5676.1   0.045       0
  5684.3   0.045       0
Bank Sta=5676.1,5684.3
Exp/Cntr=0.3,0.1

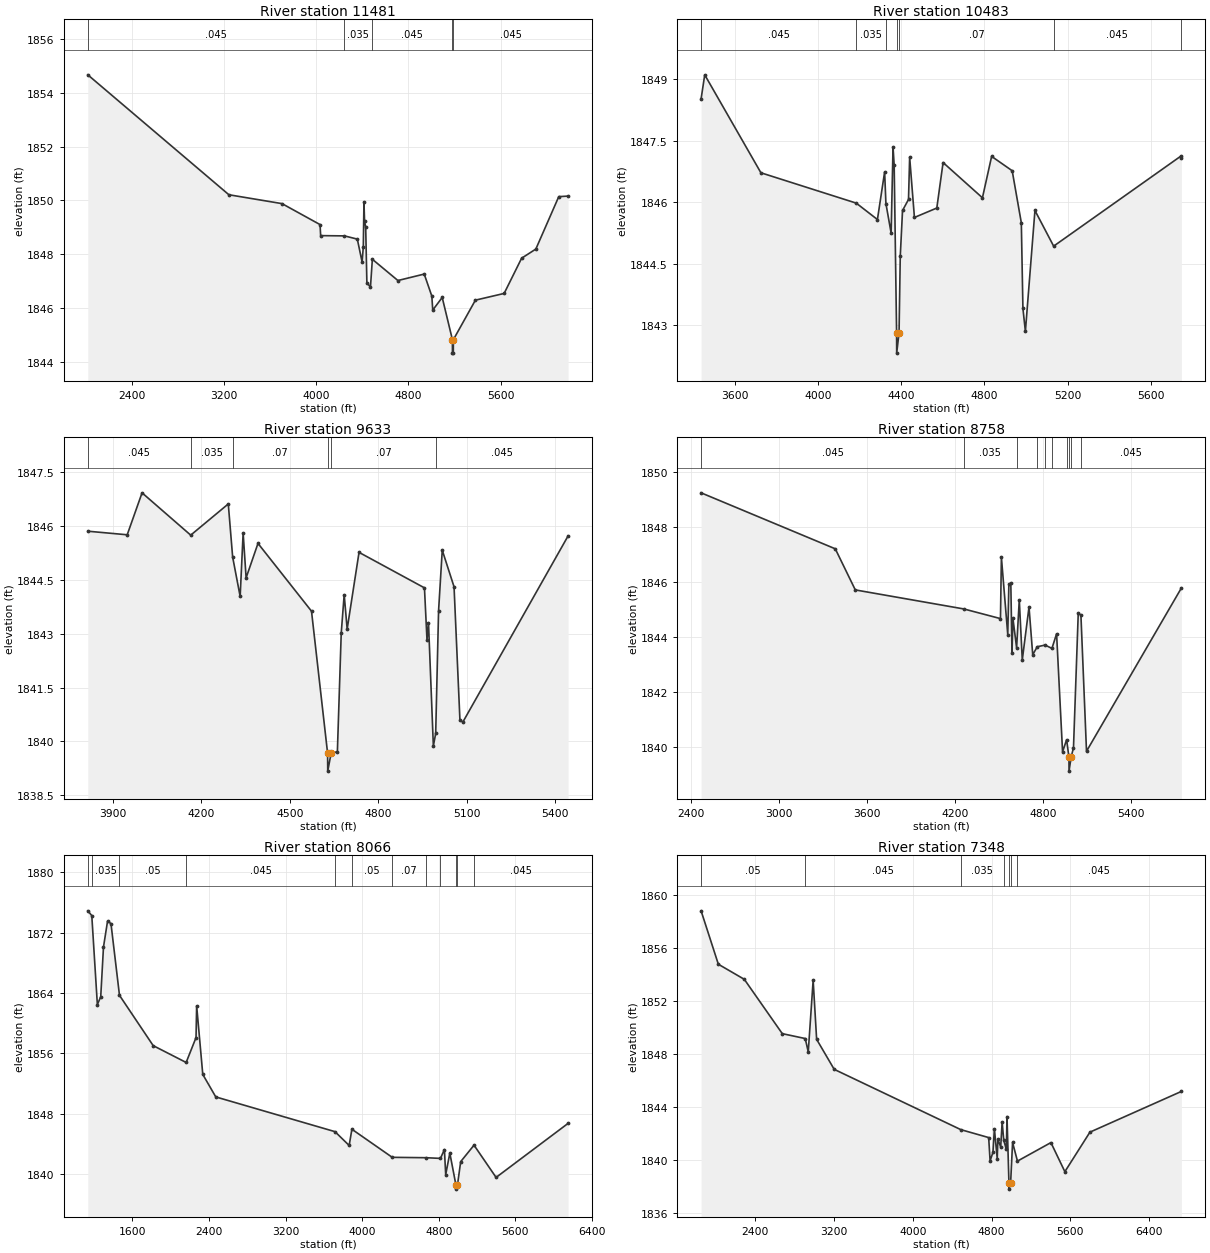
Type RM Length L Ch R = 1,11481,998,998,998
BEGIN DESCRIPTION:
Clear Fork Trib3 14.0
END DESCRIPTION:
XS GIS Cut Line= 4
      1421955.94      6962122.39      1422656.65      6959569.18
      1422535.39      6959258.20      1422260.82      6958105.65
#Sta/Elev= 30
  2018.6 1854.67  3242.3 1850.21  3703.1 1849.88  4033.1 1849.10  4038.3 1848.69
  4245.0 1848.68  4356.3 1848.56  4397.8 1847.71  4408.2 1848.27  4413.9 1849.95
  4419.1 1849.23  4428.9 1849.00  4439.3 1846.93  4470.4 1846.78  4486.8 1847.81
  4708.5 1847.02  4936.7 1847.26  5002.7 1846.44  5010.5 1845.92  5092.7 1846.39
  5181.1 1844.82  5181.6 1844.32  5188.9 1844.32  5189.4 1844.82  5380.6 1846.29
  5629.9 1846.54  5781.5 1847.85  5904.8 1848.19  6103.7 1850.14  6184.8 1850.16
#Mann=5,-1,0
  2018.6   0.045       0  4245.0   0.035       0  4486.8   0.045       0
  5181.1   0.045       0  5189.4   0.045       0
Bank Sta=5181.1,5189.4
Exp/Cntr=0.3,0.1

Type RM Length L Ch R = 1,10483,850,850,850
BEGIN DESCRIPTION:
Clear Fork Trib3 12.0
END DESCRIPTION:
XS GIS Cut Line= 3
      1423826.81      6960189.93      1423174.71      6958767.47
      1422876.15      6958081.32
#Sta/Elev= 30
  3435.2 1848.52  3452.7 1849.11  3723.3 1846.72  4182.4 1845.98  4284.4 1845.58
  4319.1 1846.74  4325.3 1845.97  4350.4 1845.25  4359.6 1847.35  4365.1 1846.90
  4376.7 1842.82  4377.2 1842.32  4388.6 1842.82  4394.4 1844.69  4405.4 1845.80
  4434.1 1846.07  4439.6 1847.10  4462.6 1845.63  4570.4 1845.86  4600.6 1846.97
  4790.1 1846.11  4834.4 1847.12  4933.4 1846.77  4977.4 1845.50  4985.1 1843.41
  4997.0 1842.85  5043.0 1845.80  5133.1 1844.93  5746.6 1847.13  5748.3 1847.09
#Mann=7,-1,0
  3435.2   0.045       0  4182.4   0.035       0  4325.3    0.07       0
  4376.7    0.07       0  4388.6    0.07       0  5133.1   0.045       0
  5746.6    0.07       0
Bank Sta=4376.7,4388.6
Exp/Cntr=0.3,0.1

Type RM Length L Ch R = 1,9633,875,875,875
BEGIN DESCRIPTION:
Clear Fork Trib3 11.0
END DESCRIPTION:
XS GIS Cut Line= 3
      1424011.14      6959620.56      1423855.00      6958438.00
      1423844.02      6958001.06
#Sta/Elev= 30
  3814.7 1845.86  3948.4 1845.76  3998.8 1846.93  4163.9 1845.75  4291.4 1846.62
  4306.2 1845.14  4331.7 1844.04  4341.8 1845.81  4351.9 1844.56  4392.2 1845.52
  4573.8 1843.63  4628.4 1839.67  4628.9 1839.17  4640.3 1839.67  4661.6 1839.71
  4674.7 1843.02  4684.7 1844.09  4694.8 1843.13  4735.1 1845.27  4957.1 1844.28
  4965.7 1842.83  4970.8 1843.31  4987.3 1839.87  4995.2 1840.22  5005.0 1843.64
  5017.5 1845.33  5057.5 1844.31  5077.5 1840.59  5087.5 1840.54  5444.6 1845.73
#Mann=6,-1,0
  3814.7   0.045       0  4163.9   0.035       0  4306.2    0.07       0
  4628.4   0.045       0  4640.3    0.07       0  4995.2   0.045       0
Bank Sta=4628.4,4640.3
Exp/Cntr=0.3,0.1

Type RM Length L Ch R = 1,8758,692,692,692
BEGIN DESCRIPTION:
Clear Fork Trib3 10.0
END DESCRIPTION:
XS GIS Cut Line= 4
      1423347.98      6960456.52      1424676.10      6958769.03
      1424605.00      6958388.00      1424126.10      6957825.50
#Sta/Elev= 30
  2469.2 1849.23  3383.9 1847.20  3520.3 1845.71  4259.9 1845.02  4509.8 1844.67
  4516.1 1846.89  4559.5 1844.09  4567.0 1845.91  4580.3 1845.95  4588.4 1843.42
  4594.7 1844.68  4619.8 1843.61  4638.0 1845.35  4658.4 1843.17  4704.3 1845.09
  4729.6 1843.36  4760.6 1843.65  4813.9 1843.71  4860.6 1843.59  4892.3 1844.12
  4933.0 1839.84  4960.7 1840.28  4976.6 1839.64  4977.1 1839.14  4991.2 1839.64
  5007.5 1839.99  5039.9 1844.86  5058.1 1844.80  5096.2 1839.86  5743.0 1845.78
#Mann=10,-1,0
  2469.2   0.045       0  4259.9   0.035       0  4619.8    0.07       0
  4760.6   0.045       0  4813.9    0.07       0  4860.6   0.045       0
  4960.7   0.035       0  4976.6   0.035       0  4991.2   0.035       0
  5058.1   0.045       0
Bank Sta=4976.6,4991.2
Exp/Cntr=0.3,0.1

Type RM Length L Ch R = 1,8066,718,718,718
BEGIN DESCRIPTION:
Clear Fork Trib3 9.0
END DESCRIPTION:
XS GIS Cut Line= 3
      1427704.98      6961287.97      1425265.39      6958288.01
      1424529.08      6957404.12
#Sta/Elev= 30
  1133.3 1874.88  1174.9 1874.25  1233.1 1862.47  1268.3 1863.50  1297.0 1870.08
  1339.5 1873.51  1375.3 1873.19  1464.2 1863.69  1816.3 1857.03  2160.6 1854.80
  2263.8 1858.10  2270.2 1862.31  2334.2 1853.22  2469.9 1850.24  3715.3 1845.64
  3863.3 1843.81  3891.8 1845.96  4313.2 1842.24  4665.2 1842.19  4816.8 1842.10
  4858.2 1843.27  4871.7 1839.95  4914.8 1842.80  4979.3 1838.53  4979.8 1838.03
  4994.0 1838.53  5028.3 1841.67  5167.4 1843.85  5398.0 1839.58  6150.4 1846.74
#Mann=12,-1,0
  1133.3   0.063       0  1174.9   0.035       0  1464.2    0.05       0
  2160.6   0.045       0  3715.3   0.035       0  3891.8    0.05       0
  4313.2    0.07       0  4665.2   0.035       0  4816.8    0.07       0
  4979.3    0.07       0  4994.0    0.07       0  5167.4   0.045       0
Bank Sta=4979.3,4994
Exp/Cntr=0.3,0.1

Type RM Length L Ch R = 1,7348,982,982,982
BEGIN DESCRIPTION:
Mapping XS 5168c96a
END DESCRIPTION:
XS GIS Cut Line= 3
      1427847.89      6960570.73      1425949.00      6958129.30
      1424712.00      6956848.89
#Sta/Elev= 30
  1853.0 1858.84  2028.1 1854.80  2291.4 1853.66  2676.9 1849.55  2909.7 1849.18
  2940.3 1848.17  2990.0 1853.58  3025.3 1849.12  3203.6 1846.85  4488.1 1842.29
  4770.9 1841.69  4785.3 1839.93  4814.3 1840.57  4828.8 1842.36  4857.7 1840.10
  4864.1 1841.56  4893.0 1840.98  4907.5 1842.86  4923.8 1841.49  4950.3 1840.79
  4956.8 1843.28  4976.4 1838.29  4976.9 1837.79  4993.8 1838.29  5013.4 1841.32
  5062.9 1839.91  5402.4 1841.31  5543.9 1839.11  5798.3 1842.10  6726.3 1845.18
#Mann=7,-1,0
  1853.0    0.05       0  2909.7   0.045       0  4488.1   0.035       0
  4923.8    0.07       0  4976.4    0.07       0  4993.8    0.07       0
  5062.9   0.045       0
Bank Sta=4976.4,4993.8
Exp/Cntr=0.3,0.1