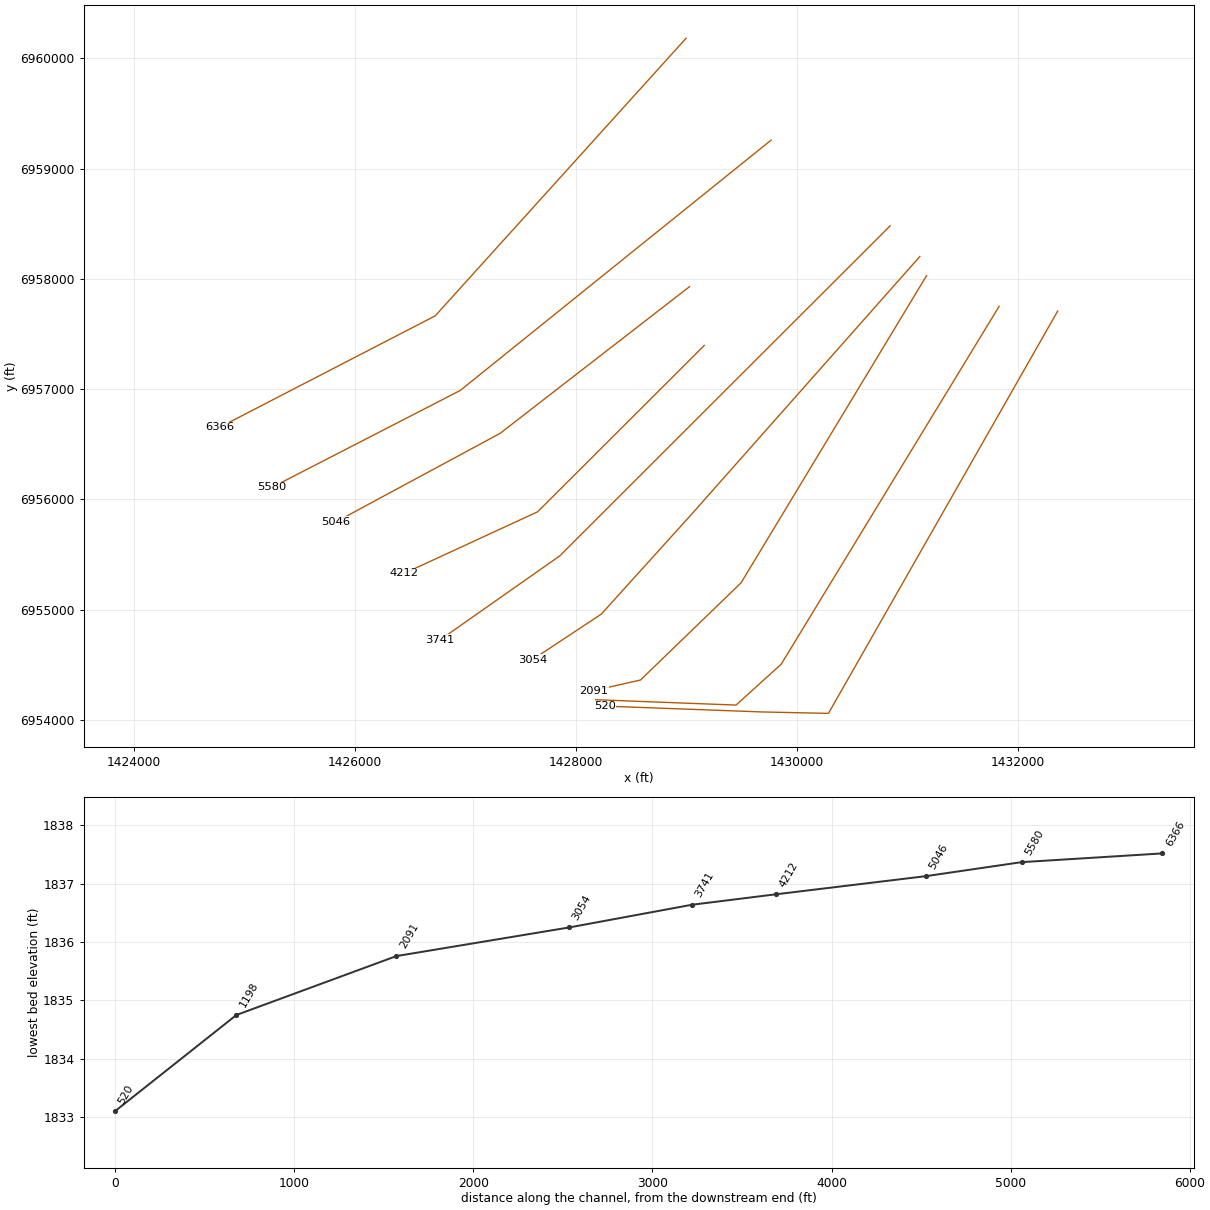
HEC-RAS study Clear Fork Trib3.prj: Clear Fork Trib3 Base Level Engineering

--- Clear Fork Trib3.g01 (geometry) --- (continued)

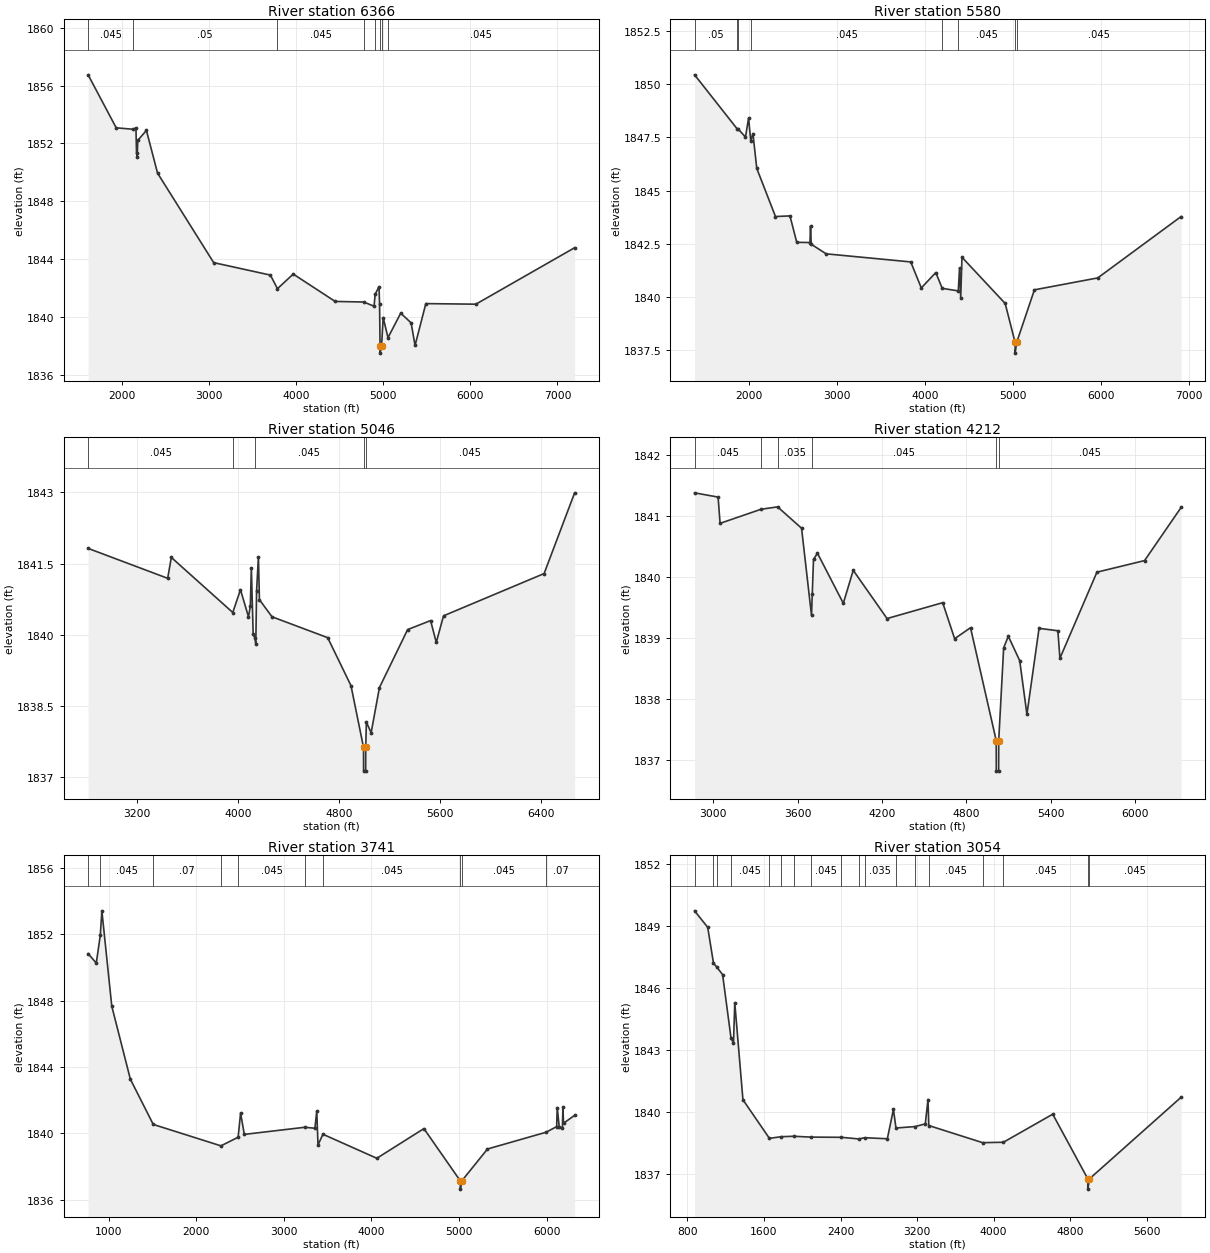
Type RM Length L Ch R = 1,6366,786,786,786
BEGIN DESCRIPTION:
Clear Fork Trib3 8.0
END DESCRIPTION:
XS GIS Cut Line= 3
      1428998.05      6960180.09      1426729.25      6957664.73
      1424778.59      6956654.36
#Sta/Elev= 30
  1612.6 1856.74  1935.0 1853.08  2129.6 1852.98  2161.5 1853.07  2168.2 1851.37
  2175.7 1851.06  2182.4 1852.21  2281.8 1852.90  2409.6 1849.95  3053.8 1843.77
  3704.7 1842.91  3785.8 1841.97  3967.0 1842.98  4448.3 1841.09  4776.2 1841.05
  4894.5 1840.76  4907.8 1841.59  4951.3 1842.11  4958.0 1840.89  4963.5 1838.02
  4964.0 1837.52  4980.9 1838.02  4999.4 1839.97  5054.8 1838.59  5200.7 1840.28
  5320.1 1839.61  5365.2 1838.05  5489.0 1840.94  6063.4 1840.90  7196.8 1844.80
#Mann=8,-1,0
  1612.6   0.045       0  2129.6    0.05       0  3785.8   0.045       0
  4776.2   0.035       0  4907.8    0.07       0  4963.5    0.07       0
  4980.9    0.07       0  5054.8   0.045       0
Bank Sta=4963.5,4980.9
Exp/Cntr=0.3,0.1

Type RM Length L Ch R = 1,5580,534,534,534
BEGIN DESCRIPTION:
Clear Fork Trib3 7.0
END DESCRIPTION:
XS GIS Cut Line= 3
      1429768.43      6959257.76      1426955.00      6956988.00
      1425254.56      6956111.07
#Sta/Elev= 30
  1384.9 1850.43  1871.4 1847.88  1877.0 1847.90  1963.4 1847.51  1998.6 1848.40
  2023.0 1847.33  2048.2 1847.67  2091.4 1846.04  2304.1 1843.78  2468.6 1843.81
  2545.7 1842.57  2695.9 1842.56  2702.4 1843.33  2710.3 1842.48  2879.9 1842.03
  3841.0 1841.65  3961.0 1840.43  4125.7 1841.15  4199.0 1840.41  4381.4 1840.29
  4395.9 1841.38  4408.8 1839.96  4423.2 1841.87  4914.2 1839.70  5027.1 1837.87
  5027.6 1837.37  5044.6 1837.87  5246.2 1840.34  5966.2 1840.90  6913.0 1843.78
#Mann=8,-1,0
  1384.9    0.05       0  1871.4   0.045       0  1877.0   0.035       0
  2023.0   0.045       0  4199.0   0.035       0  4381.4   0.045       0
  5027.1   0.045       0  5044.6   0.045       0
Bank Sta=5027.1,5044.6
Exp/Cntr=0.3,0.1

Type RM Length L Ch R = 1,5046,834,834,834
BEGIN DESCRIPTION:
Mapping XS 26f3034c
END DESCRIPTION:
XS GIS Cut Line= 3
      1429029.52      6957928.90      1427316.19      6956599.35
      1425829.85      6955796.51
#Sta/Elev= 30
  2812.0 1841.82  3442.9 1841.19  3471.8 1841.63  3959.2 1840.47  4020.2 1840.95
  4083.7 1840.38  4098.2 1840.60  4106.4 1841.41  4120.8 1840.02  4133.2 1839.94
  4141.7 1839.81  4148.0 1840.93  4162.5 1841.64  4170.6 1840.74  4270.2 1840.38
  4711.9 1839.94  4896.5 1838.93  4996.0 1837.63  4996.5 1837.13  5013.0 1837.13
  5013.5 1837.63  5018.5 1838.16  5056.5 1837.94  5122.2 1838.89  5345.7 1840.11
  5527.6 1840.30  5573.0 1839.84  5630.4 1840.40  6428.0 1841.29  6670.0 1842.99
#Mann=5,-1,0
  2812.0   0.045       0  3959.2   0.035       0  4133.2   0.045       0
  4996.0   0.045       0  5013.5   0.045       0
Bank Sta=4996,5013.5
Exp/Cntr=0.3,0.1

Type RM Length L Ch R = 1,4212,471,471,471
BEGIN DESCRIPTION:
Clear Fork Trib3 6.0
END DESCRIPTION:
XS GIS Cut Line= 3
      1429163.28      6957396.28      1427655.00      6955888.00
      1426449.20      6955330.44
#Sta/Elev= 30
  2866.6 1841.38  3033.9 1841.31  3048.0 1840.88  3338.4 1841.11  3457.2 1841.15
  3627.8 1840.80  3698.6 1839.37  3704.1 1839.73  3712.7 1840.29  3741.0 1840.39
  3924.8 1839.57  3995.5 1840.11  4236.0 1839.32  4631.9 1839.58  4716.8 1838.99
  4829.9 1839.17  5012.8 1837.32  5013.3 1836.82  5030.0 1836.82  5030.5 1837.32
  5065.7 1838.84  5098.8 1839.03  5179.9 1838.63  5231.2 1837.75  5317.5 1839.16
  5451.3 1839.12  5466.1 1838.67  5729.3 1840.08  6068.3 1840.27  6328.1 1841.14
#Mann=6,-1,0
  2866.6   0.045       0  3338.4    0.07       0  3457.2   0.035       0
  3704.1   0.045       0  5012.8   0.045       0  5030.5   0.045       0
Bank Sta=5012.8,5030.5
Exp/Cntr=0.3,0.1

Type RM Length L Ch R = 1,3741,687,687,687
BEGIN DESCRIPTION:
Clear Fork Trib3 5.0
END DESCRIPTION:
XS GIS Cut Line= 3
      1430844.60      6958480.38      1427855.00      6955488.00
      1426771.25      6954725.88
#Sta/Elev= 30
   765.6 1850.84   858.9 1850.27   904.9 1851.95   922.6 1853.42  1035.7 1847.67
  1247.8 1843.27  1509.4 1840.54  2282.2 1839.25  2478.5 1839.77  2506.5 1841.23
  2548.9 1839.94  3240.4 1840.37  3355.0 1840.31  3376.2 1841.35  3390.4 1839.30
  3446.4 1839.95  4062.1 1838.50  4599.5 1840.29  5015.0 1837.14  5015.5 1836.64
  5032.7 1837.14  5325.6 1839.06  5994.3 1840.07  6115.4 1840.41  6121.6 1841.56
  6144.7 1840.39  6180.8 1840.32  6186.9 1841.60  6193.6 1840.61  6320.4 1841.09
#Mann=10,-1,0
   765.6    0.05       0   904.9   0.045       0  1509.4    0.07       0
  2282.2   0.035       0  2478.5   0.045       0  3240.4   0.035       0
  3446.4   0.045       0  5015.0   0.045       0  5032.7   0.045       0
  5994.3    0.07       0
Bank Sta=5015,5032.7
Exp/Cntr=0.3,0.1

Type RM Length L Ch R = 1,3054,963,963,963
BEGIN DESCRIPTION:
Clear Fork Trib3 4.0
END DESCRIPTION:
XS GIS Cut Line= 4
      1431113.71      6958202.62      1429037.96      6955854.51
      1428230.95      6954960.14      1427609.55      6954548.83
#Sta/Elev= 30
   874.9 1849.73  1012.1 1848.93  1072.3 1847.20  1108.0 1847.00  1167.7 1846.64
  1255.0 1843.59  1281.5 1843.31  1294.8 1845.28  1380.2 1840.58  1656.7 1838.71
  1781.7 1838.79  1910.0 1838.81  2092.1 1838.77  2408.3 1838.76  2593.9 1838.68
  2650.8 1838.74  2889.2 1838.69  2952.8 1840.11  2979.4 1839.21  3178.2 1839.28
  3285.7 1839.41  3314.1 1840.59  3322.3 1839.33  3885.2 1838.50  4102.0 1838.52
  4617.5 1839.88  4983.7 1836.75  4984.2 1836.25  5001.6 1836.75  5958.8 1840.70
#Mann=18,-1,0
   874.9    0.05       0  1072.3    0.07       0  1108.0    0.05       0
  1255.0   0.045       0  1656.7    0.07       0  1781.7   0.035       0
  1910.0    0.07       0  2092.1   0.045       0  2408.3   0.035       0
  2593.9   0.045       0  2650.8   0.035       0  2979.4   0.045       0
  3178.2   0.035       0  3322.3   0.045       0  3885.2   0.035       0
  4102.0   0.045       0  4983.7   0.045       0  5001.6   0.045       0
Bank Sta=4983.7,5001.6
Exp/Cntr=0.3,0.1

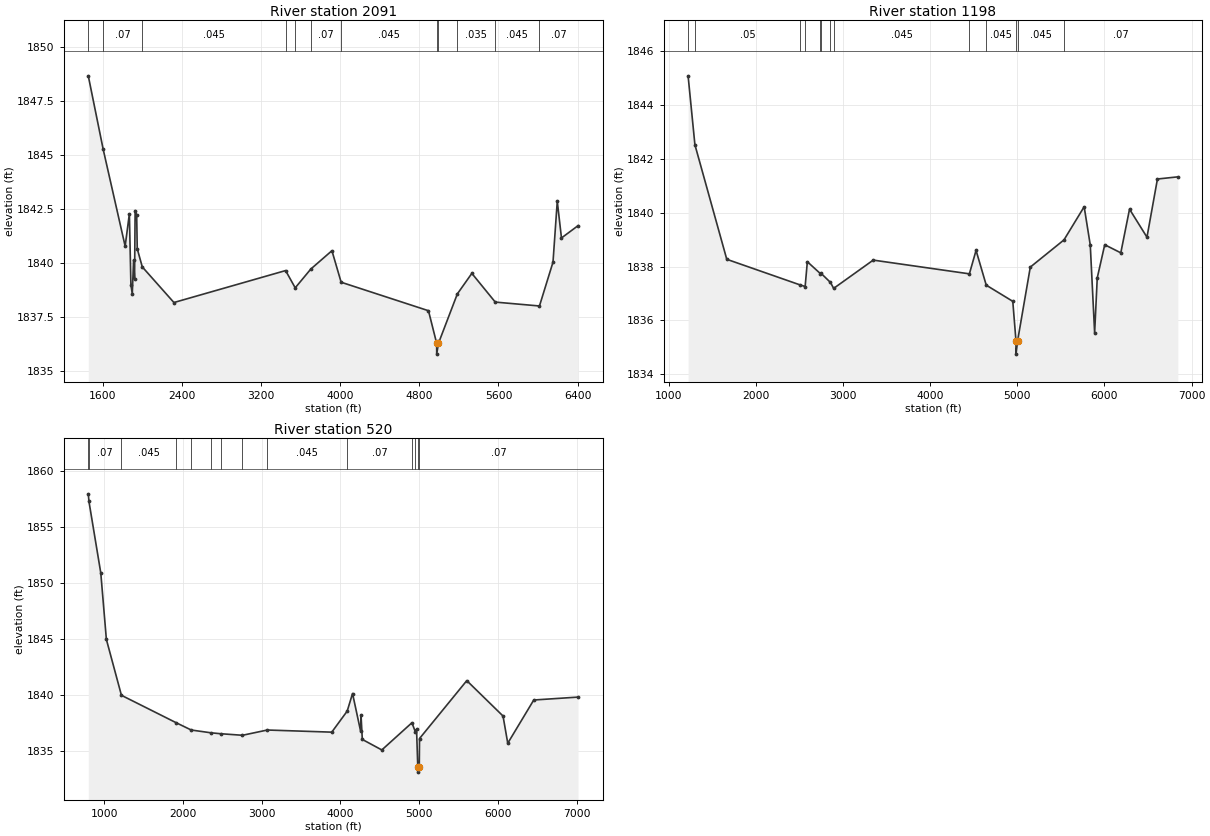
Type RM Length L Ch R = 1,2091,893,893,893
BEGIN DESCRIPTION:
Clear Fork Trib3 3.0
END DESCRIPTION:
XS GIS Cut Line= 4
      1431174.48      6958029.02      1429496.59      6955245.01
      1428586.35      6954363.71      1428161.50      6954267.15
#Sta/Elev= 30
  1451.5 1848.65  1602.5 1845.24  1824.4 1840.76  1867.1 1842.26  1882.6 1838.97
  1896.4 1838.55  1909.8 1840.12  1919.5 1839.23  1925.3 1842.41  1940.9 1842.20
  1946.7 1840.64  1997.6 1839.80  2317.6 1838.15  3447.0 1839.63  3544.2 1838.83
  3701.9 1839.70  3915.5 1840.55  4008.7 1839.09  4892.0 1837.77  4974.8 1836.26
  4975.3 1835.76  4992.8 1836.26  5184.0 1838.55  5330.6 1839.50  5567.3 1838.17
  6014.4 1837.99  6151.3 1840.02  6194.4 1842.84  6237.0 1841.14  6404.7 1841.71
#Mann=12,-1,0
  1451.5    0.05       0  1602.5    0.07       0  1997.6   0.045       0
  3447.0   0.035       0  3544.2   0.045       0  3701.9    0.07       0
  4008.7   0.045       0  4974.8   0.045       0  4992.8   0.045       0
  5184.0   0.035       0  5567.3   0.045       0  6014.4    0.07       0
Bank Sta=4974.8,4992.8
Exp/Cntr=0.3,0.1

Type RM Length L Ch R = 1,1198,678,678,678
BEGIN DESCRIPTION:
Clear Fork Trib3 2.0
END DESCRIPTION:
XS GIS Cut Line= 4
      1431830.99      6957751.19      1429859.69      6954507.36
      1429450.57      6954136.45      1428180.78      6954185.08
#Sta/Elev= 30
  1223.2 1845.08  1301.5 1842.52  1666.9 1838.27  2507.3 1837.32  2566.0 1837.26
  2591.2 1838.18  2740.3 1837.74  2748.2 1837.75  2856.8 1837.41  2893.1 1837.19
  3347.0 1838.24  4450.2 1837.73  4526.8 1838.60  4643.6 1837.31  4948.1 1836.71
  4984.6 1835.25  4985.1 1834.75  5003.7 1835.25  5149.1 1837.98  5535.5 1838.99
  5767.0 1840.22  5837.0 1838.80  5887.1 1835.54  5917.1 1837.58  6003.0 1838.81
  6187.3 1838.51  6287.4 1840.13  6487.5 1839.09  6607.6 1841.25  6842.0 1841.33
#Mann=13,-1,0
  1223.2   0.045       0  1301.5    0.05       0  2507.3   0.045       0
  2566.0   0.035       0  2740.3    0.07       0  2748.2   0.045       0
  2856.8    0.07       0  2893.1   0.045       0  4450.2    0.07       0
  4643.6   0.045       0  4984.6   0.045       0  5003.7   0.045       0
  5535.5    0.07       0
Bank Sta=4984.6,5003.7
Exp/Cntr=0.3,0.1

Type RM Length L Ch R = 1,520,0,0,0
BEGIN DESCRIPTION:
Mapping XS c2344dbf
END DESCRIPTION:
XS GIS Cut Line= 4
      1432360.48      6957707.76      1430286.74      6954061.19
      1429687.12      6954074.03      1428262.85      6954127.14
#Sta/Elev= 30
   799.5 1857.95   808.0 1857.27   958.4 1850.88  1029.3 1844.95  1220.5 1839.96
  1919.0 1837.50  2107.1 1836.86  2359.1 1836.61  2479.3 1836.53  2757.8 1836.39
  3072.8 1836.86  3891.8 1836.67  4087.8 1838.55  4155.6 1840.12  4257.9 1836.76
  4263.6 1838.16  4279.5 1836.02  4527.4 1835.08  4909.8 1837.51  4952.9 1836.70
  4968.5 1836.94  4983.9 1833.60  4984.4 1833.10  5003.0 1833.60  5006.2 1836.10
  5606.4 1841.27  6066.7 1838.11  6126.7 1835.68  6457.0 1839.54  7019.5 1839.80
#Mann=14,-1,0
   799.5   0.045       0   808.0    0.07       0  1220.5   0.045       0
  1919.0   0.035       0  2107.1   0.045       0  2359.1    0.07       0
  2479.3   0.045       0  2757.8    0.07       0  3072.8   0.045       0
  4087.8    0.07       0  4909.8   0.035       0  4952.9    0.07       0
  4983.9    0.07       0  5003.0    0.07       0
Bank Sta=4983.9,5003
Exp/Cntr=0.3,0.1

Chan Stop Cuts=-1