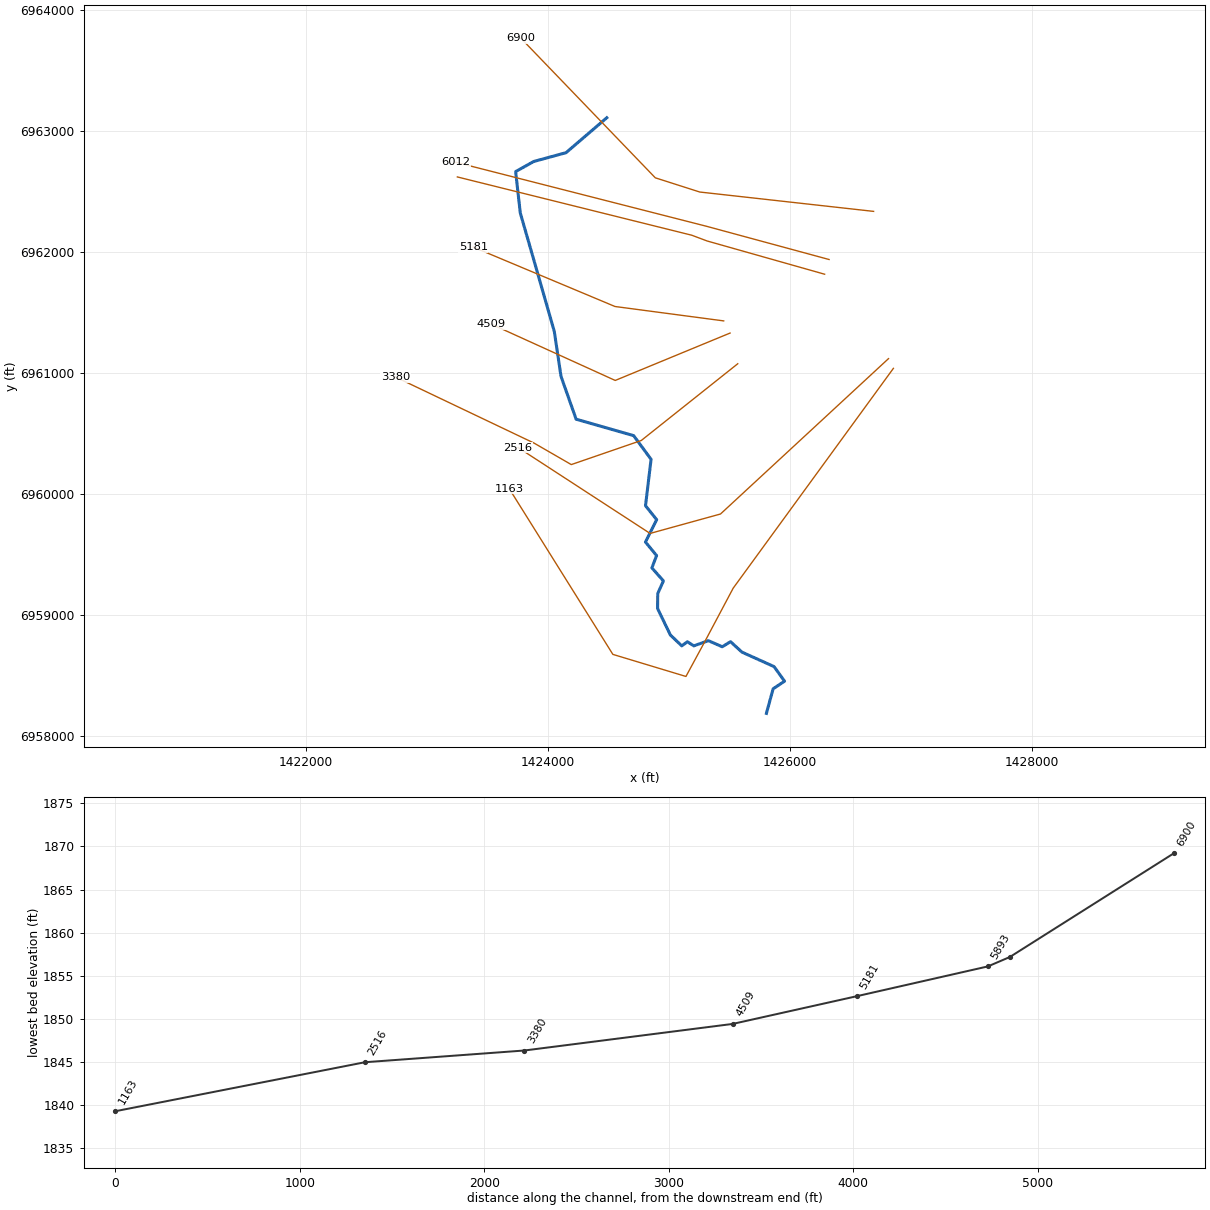
--- Clear Fork Trib3_2.prj (project) ---

Proj Title=Clear Fork Trib3_2 Base Level Engineering
Current Plan=p01
Default Exp/Contr=0.3,0.1
English Units
Geom File=g01
Flow File=f01
Plan File=p01
BEGIN DESCRIPTION:
Clear Fork Trib3_2
END DESCRIPTION:

--- Clear Fork Trib3_2.p01 (plan) ---

Plan Title=Multiple Run
Short Identifier=Multiple
Geom File=g01
Flow File=f01
Subcritical Flow
K Sum by GR= 0
Std Step Tol= 0.01
Critical Tol= 0.01
Num of Std Step Trials= 20
Max Error Tol= 0.3
Flow Tol Ratio= 0.001
Split Flow NTrial= 30
Split Flow Tol= 0.02
Split Flow Ratio= 0.02
Log Output Level= 0
Friction Slope Method= 1
Unsteady Friction Slope Method= 2
Unsteady Bridges Friction Slope Method= 1
Parabolic Critical Depth
Global Vel Dist=  1 , 1 , 1
Global Log Level= 0
CheckData=True
Encroach Param= -1, 0, 0, 0
BEGIN DESCRIPTION:
Multiple Run
END DESCRIPTION:

--- Clear Fork Trib3_2.f01 (steady flow) ---

Flow Title=Multiple
Number of Profiles=7
Profile Names=10-year,25-year,50-year,1pct_min,100-year,1pct_plu,500-year
River Rch & RM= Clear Fork Trib3,Reach-1,6900
     307     432     536     331     660    1317    1012
Boundary for River Rch & Prof#=Clear Fork Trib3,Reach-1,1
Up Type=0
Dn Type=3
Dn Slope=0.005
Boundary for River Rch & Prof#=Clear Fork Trib3,Reach-1,2
Up Type=0
Dn Type=3
Dn Slope=0.005
Boundary for River Rch & Prof#=Clear Fork Trib3,Reach-1,3
Up Type=0
Dn Type=3
Dn Slope=0.005
Boundary for River Rch & Prof#=Clear Fork Trib3,Reach-1,4
Up Type=0
Dn Type=3
Dn Slope=0.005
Boundary for River Rch & Prof#=Clear Fork Trib3,Reach-1,5
Up Type=0
Dn Type=3
Dn Slope=0.005
Boundary for River Rch & Prof#=Clear Fork Trib3,Reach-1,6
Up Type=0
Dn Type=3
Dn Slope=0.005
Boundary for River Rch & Prof#=Clear Fork Trib3,Reach-1,7
Up Type=0
Dn Type=3
Dn Slope=0.005

--- Clear Fork Trib3_2.g01 (geometry) ---

Geom Title=Existing Conditions

River Reach=Clear Fork Trib3,Reach-1
Reach XY= 30
      1424485.13      6963107.57      1424148.32      6962819.38
      1423880.96      6962746.46      1423731.65      6962663.13
      1423769.85      6962322.85      1424051.10      6961343.68
      1424106.65      6960972.16      1424231.65      6960617.99
      1424707.25      6960482.15      1424851.26      6960286.44
      1424805.39      6959903.16      1424897.70      6959788.08
      1424804.96      6959603.34      1424897.16      6959491.40
      1424858.17      6959389.65      1424953.37      6959281.96
      1424906.23      6959177.50      1424905.49      6959053.22
      1425010.83      6958835.67      1425104.99      6958745.53
      1425151.66      6958779.43      1425204.90      6958745.79
      1425325.05      6958788.58      1425439.66      6958738.23
      1425508.40      6958780.17      1425602.70      6958693.86
      1425868.25      6958574.39      1425954.82      6958454.05
      1425860.46      6958390.66      1425805.00      6958188.00

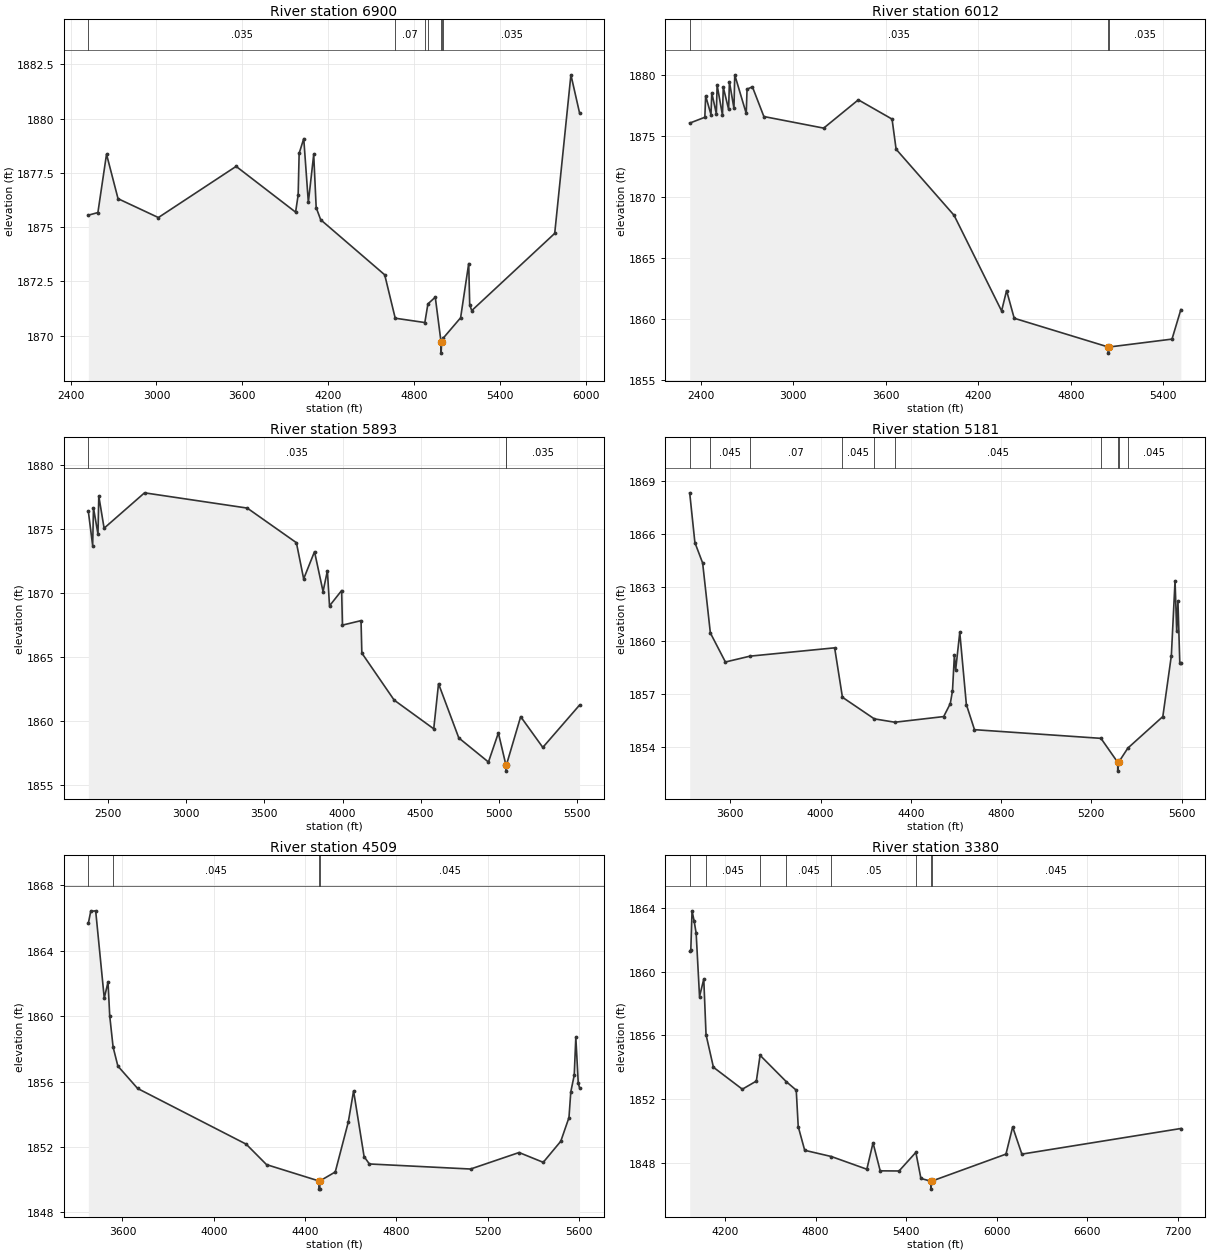
Type RM Length L Ch R = 1,6900,888,888,888
BEGIN DESCRIPTION:
Clear Fork Trib3_2 5.0
END DESCRIPTION:
XS GIS Cut Line= 4
      1426691.26      6962334.46      1425253.99      6962494.32
      1424886.26      6962611.79      1423775.88      6963763.81
#Sta/Elev= 30
  2524.3 1875.55  2591.0 1875.67  2651.3 1878.36  2731.8 1876.31  3013.6 1875.44
  3556.9 1877.80  3972.5 1875.69  3990.4 1876.48  3997.3 1878.40  4029.5 1879.08
  4061.6 1876.14  4099.1 1878.35  4116.3 1875.90  4147.8 1875.34  4595.2 1872.80
  4668.7 1870.80  4875.6 1870.60  4897.2 1871.46  4948.6 1871.77  4989.1 1869.69
  4989.3 1869.19  4993.1 1869.69  5005.3 1869.89  5125.6 1870.82  5182.2 1873.32
  5189.2 1871.42  5203.3 1871.15  5783.2 1874.71  5896.4 1882.02  5956.5 1880.27
#Mann=7,-1,0
  2524.3   0.035       0  4668.7    0.07       0  4875.6   0.035       0
  4897.2    0.07       0  4989.1    0.07       0  4993.1    0.07       0
  5005.3   0.035       0
Bank Sta=4989.1,4993.1
Exp/Cntr=0.3,0.1

Type RM Length L Ch R = 1,6012,119,119,119
BEGIN DESCRIPTION:
Mapping XS 56e5e7a9
END DESCRIPTION:
XS GIS Cut Line= 3
      1426323.35      6961936.87      1425309.28      6962211.51
      1423239.38      6962739.57
#Sta/Elev= 30
  2327.1 1876.04  2425.4 1876.52  2430.6 1878.27  2465.3 1876.74  2470.5 1878.52
  2500.0 1876.81  2505.1 1879.16  2539.8 1876.69  2545.0 1878.98  2579.7 1877.17
  2584.8 1879.43  2614.3 1877.25  2619.5 1880.00  2694.0 1876.83  2699.2 1878.82
  2733.9 1879.02  2808.4 1876.58  3196.5 1875.63  3421.2 1877.95  3640.1 1876.37
  3666.4 1873.90  4042.6 1868.48  4350.8 1860.64  4383.2 1862.31  4432.6 1860.04
  5043.6 1857.68  5043.8 1857.18  5047.6 1857.68  5456.5 1858.33  5513.9 1860.75
#Mann=3,-1,0
  2327.1   0.035       0  5043.6   0.035       0  5047.6   0.035       0
Bank Sta=5043.6,5047.6
Exp/Cntr=0.3,0.1

Type RM Length L Ch R = 1,5893,712,712,712
BEGIN DESCRIPTION:
Mapping XS 2753b13c
END DESCRIPTION:
XS GIS Cut Line= 4
      1426286.33      6961815.41      1425314.56      6962090.04
      1425187.81      6962137.57      1423249.60      6962618.96
#Sta/Elev= 30
  2373.9 1876.35  2401.5 1873.68  2406.7 1876.63  2435.5 1874.58  2440.7 1877.55
  2474.7 1875.04  2733.3 1877.80  3390.4 1876.61  3704.9 1873.91  3751.4 1871.09
  3820.8 1873.21  3875.5 1870.10  3903.2 1871.72  3916.8 1868.98  3994.4 1870.18
  3999.5 1867.48  4118.4 1867.83  4123.6 1865.30  4330.4 1861.63  4583.6 1859.39
  4614.2 1862.91  4743.9 1858.68  4933.6 1856.80  4997.1 1859.07  5044.9 1856.59
  5045.2 1856.09  5049.0 1856.59  5139.7 1860.34  5281.4 1857.94  5516.2 1861.24
#Mann=3,-1,0
  2373.9   0.035       0  5044.9   0.035       0  5049.0   0.035       0
Bank Sta=5044.9,5049
Exp/Cntr=0.3,0.1

Type RM Length L Ch R = 1,5181,672,672,672
BEGIN DESCRIPTION:
Clear Fork Trib3_2 4.0
END DESCRIPTION:
XS GIS Cut Line= 3
      1425451.92      6961429.85      1424553.24      6961548.75
      1423381.29      6962039.35
#Sta/Elev= 30
  3419.7 1868.34  3442.8 1865.53  3477.1 1864.38  3511.3 1860.43  3578.0 1858.79
  3686.8 1859.12  4062.2 1859.59  4096.7 1856.80  4238.0 1855.58  4329.2 1855.39
  4545.5 1855.71  4574.7 1856.44  4584.5 1857.16  4593.0 1859.19  4598.5 1858.34
  4616.8 1860.46  4646.0 1856.39  4682.0 1854.97  5242.6 1854.48  5316.7 1853.13
  5317.0 1852.63  5320.8 1853.13  5361.8 1853.93  5516.8 1855.71  5554.5 1859.14
  5571.0 1863.37  5578.3 1860.54  5583.8 1862.21  5592.0 1858.74  5596.7 1858.74
#Mann=10,-1,0
  3419.7   0.035       0  3511.3   0.045       0  3686.8    0.07       0
  4096.7   0.045       0  4238.0    0.07       0  4329.2   0.045       0
  5242.6    0.07       0  5316.7   0.045       0  5320.8    0.07       0
  5361.8   0.045       0
Bank Sta=5316.7,5320.8
Exp/Cntr=0.3,0.1

Type RM Length L Ch R = 1,4509,1129,1129,1129
BEGIN DESCRIPTION:
Clear Fork Trib3_2 3.0
END DESCRIPTION:
XS GIS Cut Line= 3
      1425504.68      6961329.50      1424555.00      6960938.00
      1423530.21      6961403.09
#Sta/Elev= 30
  3450.6 1865.69  3461.1 1866.42  3482.7 1866.45  3520.3 1861.11  3536.8 1862.09
  3544.3 1860.02  3559.0 1858.12  3580.0 1856.95  3666.6 1855.58  4142.5 1852.17
  4231.5 1850.92  4461.1 1849.92  4461.3 1849.42  4464.9 1849.42  4465.2 1849.92
  4532.7 1850.47  4589.9 1853.53  4613.0 1855.43  4659.1 1851.41  4682.2 1850.96
  5125.7 1850.65  5338.3 1851.66  5444.2 1851.06  5521.1 1852.35  5557.0 1853.80
  5565.0 1855.37  5580.1 1856.40  5587.0 1858.71  5597.7 1855.90  5603.2 1855.63
#Mann=4,-1,0
  3450.6   0.035       0  3559.0   0.045       0  4461.1   0.045       0
  4465.2   0.045       0
Bank Sta=4461.1,4465.2
Exp/Cntr=0.3,0.1

Type RM Length L Ch R = 1,3380,864,864,864
BEGIN DESCRIPTION:
Mapping XS f5165a10
END DESCRIPTION:
XS GIS Cut Line= 5
      1425568.05      6961075.98      1424770.57      6960442.22
      1424191.72      6960242.99      1423884.69      6960420.08
      1422738.67      6960965.86
#Sta/Elev= 30
  3966.3 1861.28  3973.8 1861.38  3981.9 1863.83  3995.7 1863.19  4009.1 1862.43
  4031.5 1858.44  4059.6 1859.54  4074.6 1856.05  4123.5 1854.00  4315.1 1852.62
  4408.0 1853.13  4432.8 1854.75  4606.7 1853.09  4672.3 1852.56  4685.5 1850.27
  4728.4 1848.78  4904.6 1848.39  5140.2 1847.59  5181.2 1849.25  5228.6 1847.49
  5353.5 1847.48  5464.9 1848.65  5498.5 1847.01  5564.5 1846.84  5564.8 1846.34
  5569.1 1846.84  6062.0 1848.54  6106.3 1850.25  6167.4 1848.54  7220.9 1850.15
#Mann=8,-1,0
  3966.3   0.035       0  4074.6   0.045       0  4432.8    0.07       0
  4606.7   0.045       0  4904.6    0.05       0  5464.9   0.045       0
  5564.5    0.05       0  5569.1   0.045       0
Bank Sta=5564.5,5569.1
Exp/Cntr=0.3,0.1

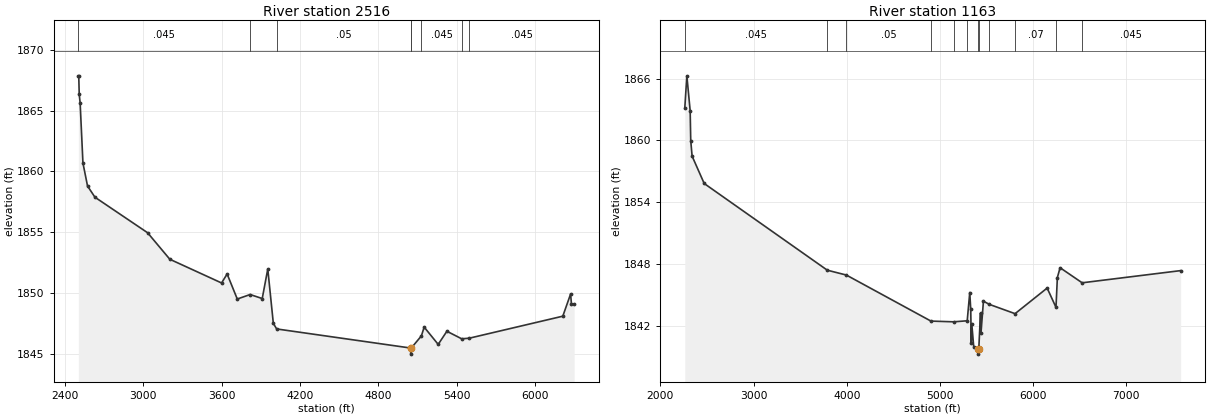
Type RM Length L Ch R = 1,2516,1353,1353,1353
BEGIN DESCRIPTION:
Clear Fork Trib3_2 2.0
END DESCRIPTION:
XS GIS Cut Line= 4
      1426814.51      6961118.26      1425425.47      6959834.85
      1424843.21      6959674.38      1423752.09      6960383.58
#Sta/Elev= 30
  2502.7 1867.86  2505.8 1867.86  2509.6 1866.33  2516.5 1865.64  2538.0 1860.69
  2573.2 1858.80  2629.9 1857.88  3033.0 1854.96  3203.1 1852.78  3599.5 1850.83
  3642.0 1851.57  3719.7 1849.51  3818.2 1849.88  3910.8 1849.55  3953.3 1851.98
  3995.8 1847.51  4021.3 1847.05  5047.8 1845.48  5048.0 1844.98  5052.0 1845.48
  5129.5 1846.48  5150.8 1847.20  5258.1 1845.78  5324.7 1846.86  5438.1 1846.24
  5496.2 1846.29  6212.3 1848.10  6271.9 1849.92  6278.8 1849.07  6299.2 1849.08
#Mann=8,-1,0
  2502.7   0.045       0  3818.2   0.035       0  4021.3    0.05       0
  5047.8    0.05       0  5052.0    0.05       0  5129.5   0.045       0
  5438.1    0.07       0  5496.2   0.045       0
Bank Sta=5047.8,5052
Exp/Cntr=0.3,0.1

Type RM Length L Ch R = 1,1163,0,0,0
BEGIN DESCRIPTION:
Clear Fork Trib3_2 1.0
END DESCRIPTION:
XS GIS Cut Line= 6
      1426855.00      6961038.00      1425530.26      6959222.16
      1425299.95      6958788.77      1425139.64      6958492.99
      1424535.47      6958675.28      1423678.26      6960044.60
#Sta/Elev= 30
  2261.5 1863.14  2283.5 1866.26  2319.0 1862.89  2325.2 1859.99  2339.9 1858.48
  2469.7 1855.83  3791.1 1847.43  3995.6 1846.96  4903.4 1842.50  5146.9 1842.43
  5292.5 1842.53  5319.9 1845.27  5330.4 1843.63  5336.0 1840.36  5341.5 1842.23
  5362.2 1840.03  5412.0 1839.80  5412.3 1839.30  5416.8 1839.80  5435.2 1843.29
  5440.4 1841.34  5466.6 1844.43  5529.9 1844.12  5806.1 1843.22  6150.5 1845.70
  6245.4 1843.83  6260.1 1846.72  6289.3 1847.67  6526.1 1846.21  7583.0 1847.39
#Mann=12,-1,0
  2261.5   0.045       0  3791.1   0.035       0  3995.6    0.05       0
  4903.4    0.07       0  5146.9   0.035       0  5292.5    0.07       0
  5412.0    0.07       0  5416.8    0.07       0  5529.9   0.045       0
  5806.1    0.07       0  6245.4   0.035       0  6526.1   0.045       0
Bank Sta=5412,5416.8
Exp/Cntr=0.3,0.1

Chan Stop Cuts=-1