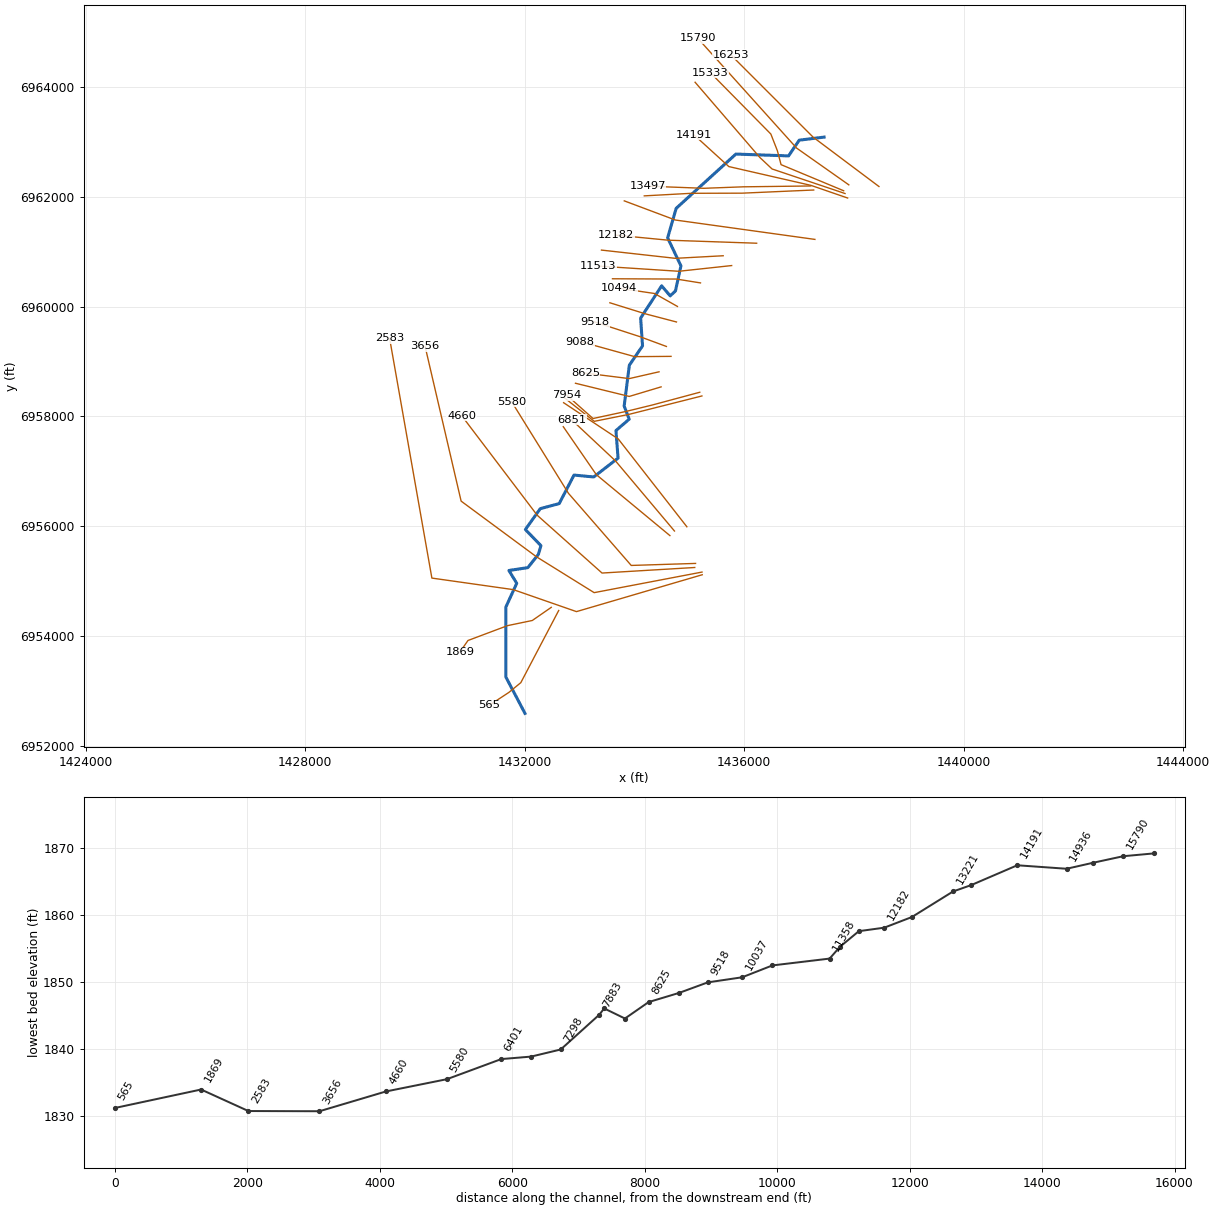
--- Clear Fork Trib4.prj (project) ---

Proj Title=Clear Fork Trib4 Base Level Engineering
Current Plan=p01
Default Exp/Contr=0.3,0.1
English Units
Geom File=g01
Flow File=f01
Plan File=p01
BEGIN DESCRIPTION:
Clear Fork Trib4
END DESCRIPTION:

--- Clear Fork Trib4.p01 (plan) ---

Plan Title=Multiple Run
Short Identifier=Multiple
Geom File=g01
Flow File=f01
Subcritical Flow
K Sum by GR= 0
Std Step Tol= 0.01
Critical Tol= 0.01
Num of Std Step Trials= 20
Max Error Tol= 0.3
Flow Tol Ratio= 0.001
Split Flow NTrial= 30
Split Flow Tol= 0.02
Split Flow Ratio= 0.02
Log Output Level= 0
Friction Slope Method= 1
Unsteady Friction Slope Method= 2
Unsteady Bridges Friction Slope Method= 1
Parabolic Critical Depth
Global Vel Dist=  1 , 1 , 1
Global Log Level= 0
CheckData=True
Encroach Param= -1, 0, 0, 0
BEGIN DESCRIPTION:
Multiple Run
END DESCRIPTION:

--- Clear Fork Trib4.f01 (steady flow) ---

Flow Title=Multiple
Number of Profiles=7
Profile Names=10-year,25-year,50-year,1pct_min,100-year,1pct_plu,500-year
River Rch & RM= Clear Fork Trib4,Reach-1,16253
     398     566     708     440     877    1751    1365
River Rch & RM= Clear Fork Trib4,Reach-1,14191
     441     632     795     496     989    1974    1552
River Rch & RM= Clear Fork Trib4,Reach-1,11358
     504     726     915     572    1141    2277    1799
River Rch & RM= Clear Fork Trib4,Reach-1,6401
     822    1211    1550     983    1961    3914    3182
Boundary for River Rch & Prof#=Clear Fork Trib4,Reach-1,1
Up Type=0
Dn Type=3
Dn Slope=0.005
Boundary for River Rch & Prof#=Clear Fork Trib4,Reach-1,2
Up Type=0
Dn Type=3
Dn Slope=0.005
Boundary for River Rch & Prof#=Clear Fork Trib4,Reach-1,3
Up Type=0
Dn Type=3
Dn Slope=0.005
Boundary for River Rch & Prof#=Clear Fork Trib4,Reach-1,4
Up Type=0
Dn Type=3
Dn Slope=0.005
Boundary for River Rch & Prof#=Clear Fork Trib4,Reach-1,5
Up Type=0
Dn Type=3
Dn Slope=0.005
Boundary for River Rch & Prof#=Clear Fork Trib4,Reach-1,6
Up Type=0
Dn Type=3
Dn Slope=0.005
Boundary for River Rch & Prof#=Clear Fork Trib4,Reach-1,7
Up Type=0
Dn Type=3
Dn Slope=0.005

--- Clear Fork Trib4.g01 (geometry) ---

Geom Title=Existing Conditions

River Reach=Clear Fork Trib4,Reach-1
Reach XY= 30
      1437455.00      6963088.00      1437002.00      6963032.54
      1436808.31      6962746.02      1435847.98      6962778.99
      1434760.36      6961790.70      1434604.53      6961253.16
      1434847.19      6960741.41      1434747.01      6960284.63
      1434651.40      6960195.47      1434495.34      6960377.84
      1434112.61      6959791.33      1434147.19      6959284.59
      1433906.80      6958931.89      1433812.50      6958188.00
      1433904.13      6957948.33      1433662.79      6957741.42
      1433701.39      6957239.50      1433258.41      6956895.76
      1432898.61      6956930.00      1432628.96      6956410.51
      1432284.61      6956318.32      1432012.07      6955938.00
      1432295.88      6955644.75      1432249.47      6955485.58
      1432057.44      6955243.39      1431712.48      6955191.62
      1431855.30      6954958.18      1431655.50      6954522.78
      1431655.52      6953253.22      1432005.00      6952588.00

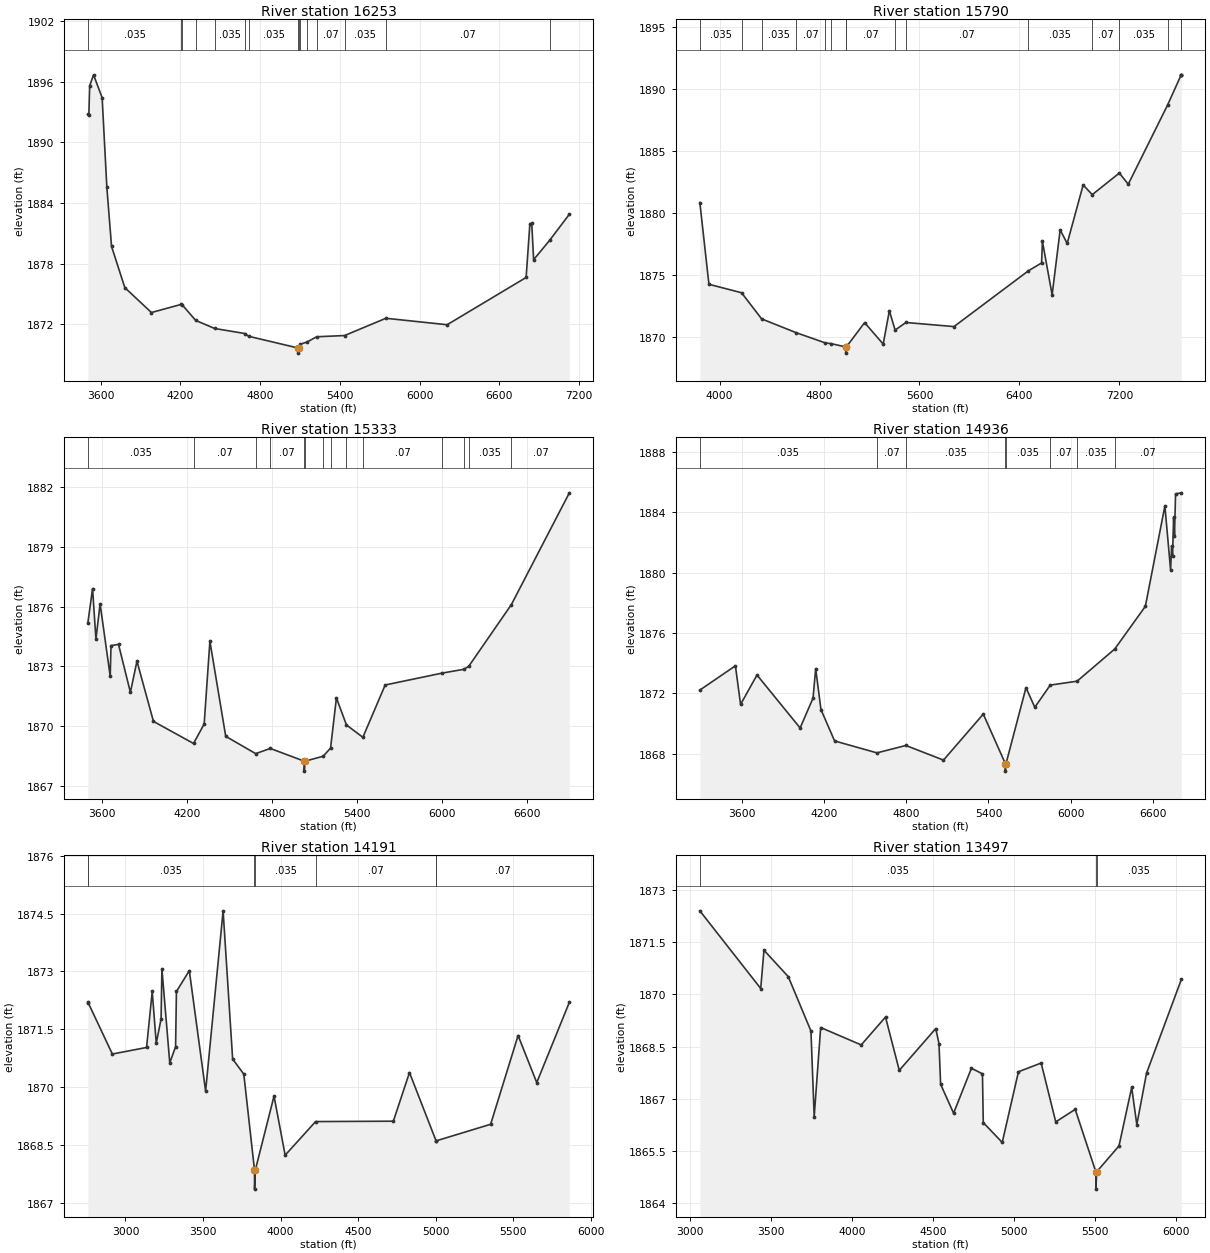
Type RM Length L Ch R = 1,16253,463,463,463
BEGIN DESCRIPTION:
Clear Fork Trib4 15.0
END DESCRIPTION:
XS GIS Cut Line= 3
      1438455.01      6962187.99      1437255.00      6963088.00
      1435755.03      6964587.97
#Sta/Elev= 30
  3504.9 1892.77  3512.2 1892.69  3518.5 1895.60  3547.6 1896.68  3612.2 1894.42
  3647.6 1885.56  3683.0 1879.69  3783.0 1875.61  3983.0 1873.15  4205.6 1873.95
  4213.9 1873.92  4315.6 1872.37  4458.6 1871.57  4686.0 1871.07  4713.6 1870.80
  5087.8 1869.63  5088.0 1869.13  5091.8 1869.63  5103.2 1870.01  5154.8 1870.24
  5225.9 1870.75  5435.3 1870.87  5746.4 1872.58  6207.0 1871.94  6801.0 1876.62
  6829.3 1881.92  6843.4 1881.97  6857.5 1878.38  6977.5 1880.29  7126.2 1882.88
#Mann=15,-1,0
  3504.9   0.035       0  4205.6    0.07       0  4213.9   0.035       0
  4315.6    0.07       0  4458.6   0.035       0  4686.0    0.07       0
  4713.6   0.035       0  5087.8   0.035       0  5091.8   0.035       0
  5103.2    0.07       0  5154.8   0.035       0  5225.9    0.07       0
  5435.3   0.035       0  5746.4    0.07       0  6977.5   0.035       0
Bank Sta=5087.8,5091.8
Exp/Cntr=0.3,0.1

Type RM Length L Ch R = 1,15790,457,457,457
BEGIN DESCRIPTION:
Clear Fork Trib4 14.0
END DESCRIPTION:
XS GIS Cut Line= 3
      1437905.81      6962218.53      1436955.00      6962888.00
      1435154.99      6964888.02
#Sta/Elev= 30
  3842.1 1880.85  3914.8 1874.26  4175.8 1873.58  4336.8 1871.47  4612.7 1870.36
  4847.2 1869.53  4891.1 1869.48  5009.6 1869.21  5009.9 1868.71  5014.6 1869.21
  5160.8 1871.17  5309.5 1869.44  5358.9 1872.13  5404.7 1870.57  5491.5 1871.18
  5876.1 1870.85  6472.0 1875.35  6577.2 1875.98  6583.9 1877.72  6661.6 1873.41
  6725.9 1878.65  6782.0 1877.55  6909.8 1882.27  6982.7 1881.49  7199.4 1883.23
  7270.8 1882.33  7585.8 1888.72  7694.3 1891.15  7694.9 1891.15  7695.7 1891.15
#Mann=16,-1,0
  3842.1   0.035       0  4175.8    0.07       0  4336.8   0.035       0
  4612.7    0.07       0  4847.2   0.035       0  4891.1    0.07       0
  5009.6    0.07       0  5014.6    0.07       0  5404.7   0.035       0
  5491.5    0.07       0  6472.0   0.035       0  6982.7    0.07       0
  7199.4   0.035       0  7585.8    0.07       0  7694.3   0.035       0
  7694.9    0.07       0
Bank Sta=5009.6,5014.6
Exp/Cntr=0.3,0.1

Type RM Length L Ch R = 1,15333,397,397,397
BEGIN DESCRIPTION:
Clear Fork Trib4 13.0
END DESCRIPTION:
XS GIS Cut Line= 5
      1437811.79      6962110.77      1436671.10      6962586.58
      1436605.00      6962838.00      1436485.19      6963144.32
      1435382.80      6964262.29
#Sta/Elev= 30
  3503.2 1875.18  3536.3 1876.91  3560.1 1874.36  3589.4 1876.14  3660.8 1872.50
  3666.3 1874.04  3719.3 1874.10  3803.1 1871.69  3849.3 1873.26  3965.6 1870.23
  4248.3 1869.12  4323.2 1870.10  4363.6 1874.26  4475.2 1869.48  4686.3 1868.61
  4789.8 1868.87  5028.8 1868.23  5029.2 1867.73  5033.9 1868.23  5162.6 1868.48
  5214.4 1868.89  5255.7 1871.41  5326.5 1870.05  5442.2 1869.43  5599.5 1872.06
  6002.8 1872.66  6155.1 1872.85  6188.7 1873.00  6489.1 1876.10  6898.1 1881.72
#Mann=14,-1,0
  3503.2   0.035       0  4248.3    0.07       0  4686.3   0.035       0
  4789.8    0.07       0  5028.8    0.07       0  5033.9    0.07       0
  5162.6   0.035       0  5214.4    0.07       0  5326.5   0.035       0
  5442.2    0.07       0  6002.8   0.035       0  6155.1    0.07       0
  6188.7   0.035       0  6489.1    0.07       0
Bank Sta=5028.8,5033.9
Exp/Cntr=0.3,0.1

Type RM Length L Ch R = 1,14936,745,745,745
BEGIN DESCRIPTION:
Clear Fork Trib4 12.0
END DESCRIPTION:
XS GIS Cut Line= 4
      1437836.96      6962060.37      1436507.24      6962507.80
      1436284.99      6962717.15      1435104.97      6964088.03
#Sta/Elev= 30
  3291.7 1872.21  3551.5 1873.82  3589.2 1871.26  3709.1 1873.21  4024.1 1869.70
  4118.6 1871.68  4137.8 1873.63  4176.3 1870.92  4276.1 1868.84  4585.3 1868.05
  4796.8 1868.54  5071.3 1867.57  5362.1 1870.62  5523.0 1867.34  5523.4 1866.84
  5528.2 1867.34  5674.0 1872.37  5738.4 1871.07  5851.1 1872.54  6047.3 1872.80
  6322.1 1874.93  6546.0 1877.76  6688.6 1884.41  6730.3 1880.17  6738.0 1881.78
  6744.6 1881.07  6752.2 1883.65  6758.8 1882.43  6766.5 1885.21  6808.8 1885.28
#Mann=8,-1,0
  3291.7   0.035       0  4585.3    0.07       0  4796.8   0.035       0
  5523.0   0.035       0  5528.2   0.035       0  5851.1    0.07       0
  6047.3   0.035       0  6322.1    0.07       0
Bank Sta=5523,5528.2
Exp/Cntr=0.3,0.1

Type RM Length L Ch R = 1,14191,694,694,694
BEGIN DESCRIPTION:
Mapping XS efd06c7e
END DESCRIPTION:
XS GIS Cut Line= 4
      1437884.23      6961978.43      1437215.25      6962209.00
      1435719.63      6962551.33      1435081.64      6963132.03
#Sta/Elev= 30
  2757.7 1872.21  2760.9 1872.18  2915.5 1870.86  3136.2 1871.03  3172.7 1872.48
  3198.6 1871.14  3229.8 1871.77  3235.1 1873.07  3285.8 1870.63  3323.4 1871.05
  3328.7 1872.48  3411.8 1873.02  3516.9 1869.90  3629.7 1874.57  3691.2 1870.73
  3763.1 1870.34  3832.0 1867.86  3832.5 1867.36  3837.8 1867.86  3958.0 1869.77
  4029.8 1868.24  4226.1 1869.11  4727.4 1869.12  4831.4 1870.38  5002.9 1868.61
  5003.0 1868.61  5354.7 1869.04  5531.7 1871.34  5652.0 1870.12  5862.3 1872.20
#Mann=7,-1,0
  2757.7    0.07       0  2760.9   0.035       0  3832.0    0.07       0
  3837.8   0.035       0  4226.1    0.07       0  5002.9   0.035       0
  5003.0    0.07       0
Bank Sta=3832,3837.8
Exp/Cntr=0.3,0.1

Type RM Length L Ch R = 1,13497,276,276,276
BEGIN DESCRIPTION:
Mapping XS a482a60e
END DESCRIPTION:
XS GIS Cut Line= 4
      1437210.68      6962197.93      1435979.91      6962182.37
      1435263.90      6962155.49      1434240.43      6962194.56
#Sta/Elev= 30
  3062.0 1872.40  3437.7 1870.17  3457.7 1871.27  3607.7 1870.51  3747.7 1868.95
  3767.7 1866.49  3807.7 1869.05  4057.8 1868.55  4207.8 1869.35  4292.8 1867.82
  4517.9 1869.02  4537.8 1868.59  4548.0 1867.42  4628.0 1866.59  4738.1 1867.88
  4806.2 1867.72  4811.2 1866.32  4928.2 1865.75  5028.3 1867.78  5168.4 1868.03
  5258.5 1866.34  5378.6 1866.70  5505.7 1864.91  5506.2 1864.41  5511.5 1864.91
  5648.8 1865.65  5727.2 1867.33  5758.8 1866.26  5818.9 1867.74  6033.6 1870.43
#Mann=3,-1,0
  3062.0   0.035       0  5505.7   0.035       0  5511.5   0.035       0
Bank Sta=5505.7,5511.5
Exp/Cntr=0.3,0.1

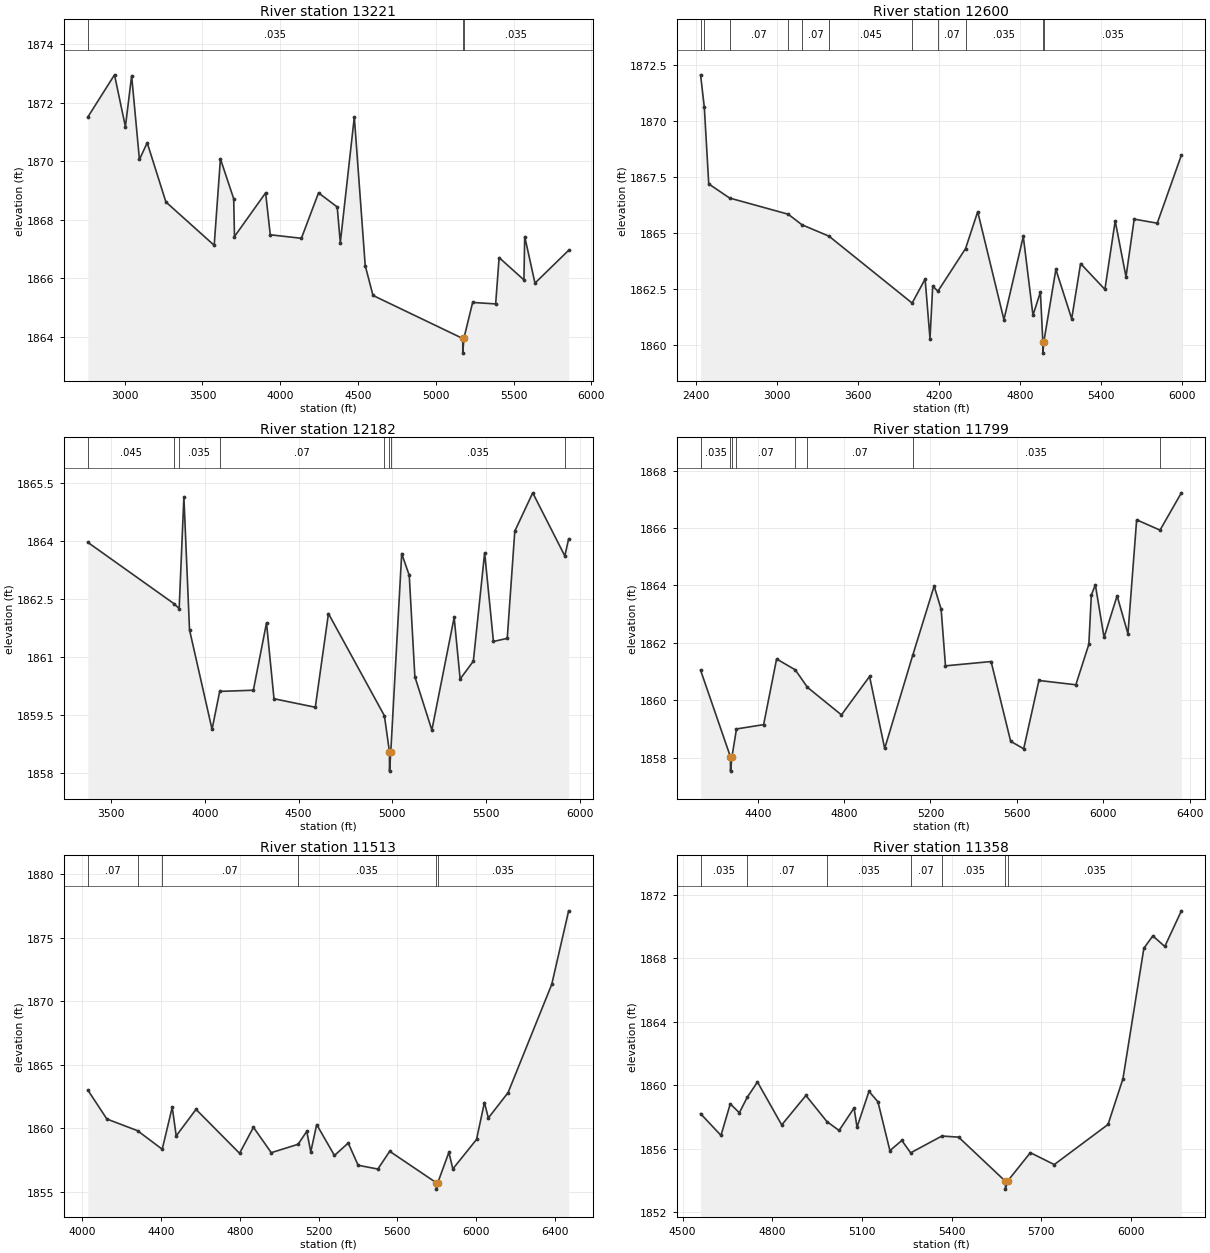
Type RM Length L Ch R = 1,13221,621,621,621
BEGIN DESCRIPTION:
Mapping XS c1f49c1a
END DESCRIPTION:
XS GIS Cut Line= 4
      1437266.24      6962124.37      1435962.82      6962066.81
      1435034.74      6962064.35      1434178.99      6962017.53
#Sta/Elev= 30
  2763.5 1871.51  2934.9 1872.95  3005.0 1871.18  3045.0 1872.92  3095.1 1870.06
  3145.1 1870.63  3265.2 1868.61  3575.5 1867.13  3615.6 1870.08  3700.9 1868.72
  3705.9 1867.43  3905.9 1868.92  3935.9 1867.49  4136.0 1867.37  4246.0 1868.92
  4366.0 1868.44  4386.0 1867.22  4476.0 1871.51  4546.0 1866.44  4596.0 1865.42
  5172.7 1863.95  5173.2 1863.45  5179.9 1863.95  5236.4 1865.18  5384.3 1865.13
  5406.6 1866.71  5566.0 1865.95  5571.0 1867.43  5637.0 1865.84  5853.3 1866.96
#Mann=3,-1,0
  2763.5   0.035       0  5172.7   0.035       0  5179.9   0.035       0
Bank Sta=5172.7,5179.9
Exp/Cntr=0.3,0.1

Type RM Length L Ch R = 1,12600,418,418,418
BEGIN DESCRIPTION:
Mapping XS 3d1d691f
END DESCRIPTION:
XS GIS Cut Line= 3
      1437288.17      6961224.41      1434745.68      6961577.37
      1433814.64      6961926.44
#Sta/Elev= 30
  2431.6 1872.04  2459.5 1870.59  2492.2 1867.18  2646.8 1866.55  3080.5 1865.83
  3182.3 1865.36  3383.1 1864.85  3998.6 1861.87  4094.8 1862.94  4130.9 1860.29
  4151.1 1862.62  4189.7 1862.40  4394.4 1864.30  4484.3 1865.94  4678.5 1861.13
  4821.9 1864.84  4893.6 1861.33  4948.7 1862.36  4966.7 1860.14  4967.2 1859.64
  4973.9 1860.14  5063.3 1863.37  5180.4 1861.17  5246.3 1863.63  5426.4 1862.48
  5502.6 1865.53  5582.7 1863.04  5643.3 1865.61  5814.1 1865.43  5992.8 1868.46
#Mann=11,-1,0
  2431.6    0.07       0  2459.5   0.045       0  2646.8    0.07       0
  3080.5   0.045       0  3182.3    0.07       0  3383.1   0.045       0
  3998.6   0.035       0  4189.7    0.07       0  4394.4   0.035       0
  4966.7   0.035       0  4973.9   0.035       0
Bank Sta=4966.7,4973.9
Exp/Cntr=0.3,0.1

Type RM Length L Ch R = 1,12182,383,383,383
BEGIN DESCRIPTION:
Mapping XS 1af03642
END DESCRIPTION:
XS GIS Cut Line= 3
      1436226.70      6961154.73      1434612.86      6961210.18
      1433669.35      6961301.40
#Sta/Elev= 30
  3376.9 1863.96  3835.0 1862.38  3863.7 1862.25  3888.9 1865.14  3918.9 1861.70
  4039.0 1859.13  4079.7 1860.11  4259.1 1860.14  4329.2 1861.88  4369.2 1859.92
  4589.3 1859.70  4659.4 1862.12  4957.7 1859.48  4984.5 1858.55  4985.0 1858.05
  4991.7 1858.55  5049.8 1863.67  5090.0 1863.11  5120.0 1860.49  5210.6 1859.11
  5329.4 1862.02  5361.3 1860.43  5431.6 1860.89  5491.9 1863.69  5538.8 1861.40
  5612.4 1861.48  5652.6 1864.25  5748.2 1865.24  5919.2 1863.61  5939.6 1864.05
#Mann=8,-1,0
  3376.9   0.045       0  3835.0    0.07       0  3863.7   0.035       0
  4079.7    0.07       0  4957.7   0.035       0  4984.5   0.035       0
  4991.7   0.035       0  5919.2    0.07       0
Bank Sta=4984.5,4991.7
Exp/Cntr=0.3,0.1

Type RM Length L Ch R = 1,11799,286,286,286
BEGIN DESCRIPTION:
Mapping XS 61ae88a0
END DESCRIPTION:
XS GIS Cut Line= 3
      1435616.66      6960926.45      1434745.68      6960879.45
      1433399.07      6961029.62
#Sta/Elev= 30
  4135.0 1861.05  4273.3 1858.03  4273.8 1857.53  4280.5 1858.03  4301.3 1859.00
  4427.1 1859.15  4487.2 1861.44  4573.7 1861.06  4630.3 1860.45  4787.6 1859.49
  4917.8 1860.83  4987.9 1858.32  5117.8 1861.57  5217.0 1863.98  5249.4 1863.17
  5269.5 1861.20  5480.8 1861.35  5571.4 1858.57  5631.8 1858.31  5702.2 1860.69
  5873.3 1860.54  5933.6 1861.95  5945.1 1863.67  5963.8 1864.02  6004.1 1862.19
  6064.4 1863.64  6114.7 1862.32  6155.0 1866.29  6263.3 1865.93  6362.2 1867.23
#Mann=8,-1,0
  4135.0   0.035       0  4273.3    0.07       0  4280.5   0.035       0
  4301.3    0.07       0  4573.7   0.035       0  4630.3    0.07       0
  5117.8   0.035       0  6263.3    0.07       0
Bank Sta=4273.3,4280.5
Exp/Cntr=0.3,0.1

Type RM Length L Ch R = 1,11513,155,155,155
BEGIN DESCRIPTION:
Mapping XS fa0a20fb
END DESCRIPTION:
XS GIS Cut Line= 3
      1435771.17      6960747.61      1434807.64      6960643.44
      1433338.17      6960738.81
#Sta/Elev= 30
  4027.9 1862.99  4124.6 1860.71  4280.3 1859.79  4405.7 1858.33  4456.6 1861.64
  4476.7 1859.38  4577.3 1861.47  4798.5 1858.01  4868.9 1860.06  4959.5 1858.06
  5095.5 1858.72  5139.8 1859.74  5160.0 1858.12  5190.1 1860.27  5280.3 1857.84
  5350.4 1858.82  5400.5 1857.07  5500.7 1856.77  5560.9 1858.17  5797.8 1855.69
  5798.3 1855.19  5805.0 1855.69  5861.5 1858.09  5881.5 1856.78  6001.8 1859.10
  6041.9 1862.01  6061.9 1860.79  6162.1 1862.79  6383.8 1871.31  6469.6 1877.10
#Mann=6,-1,0
  4027.9    0.07       0  4280.3   0.035       0  4405.7    0.07       0
  5095.5   0.035       0  5797.8    0.07       0  5805.0   0.035       0
Bank Sta=5797.8,5805
Exp/Cntr=0.3,0.1

Type RM Length L Ch R = 1,11358,864,864,864
BEGIN DESCRIPTION:
Mapping XS a474945a
END DESCRIPTION:
XS GIS Cut Line= 3
      1435203.16      6960431.53      1434763.04      6960501.85
      1433599.46      6960507.05
#Sta/Elev= 30
  4560.0 1858.20  4628.3 1856.83  4659.4 1858.82  4689.8 1858.26  4716.1 1859.23
  4750.5 1860.20  4831.6 1857.49  4912.6 1859.35  4983.0 1857.70  5023.7 1857.14
  5073.7 1858.56  5083.7 1857.35  5123.7 1859.61  5153.7 1858.95  5193.7 1855.87
  5233.7 1856.51  5263.2 1855.73  5367.7 1856.79  5423.7 1856.72  5580.1 1853.94
  5580.6 1853.44  5587.4 1853.94  5663.8 1855.74  5743.8 1854.99  5923.8 1857.52
  5973.8 1860.41  6043.8 1868.64  6073.8 1869.42  6113.8 1868.75  6169.3 1871.00
#Mann=7,-1,0
  4560.0   0.035       0  4716.1    0.07       0  4983.0   0.035       0
  5263.2    0.07       0  5367.7   0.035       0  5580.1   0.035       0
  5587.4   0.035       0
Bank Sta=5580.1,5587.4
Exp/Cntr=0.3,0.1

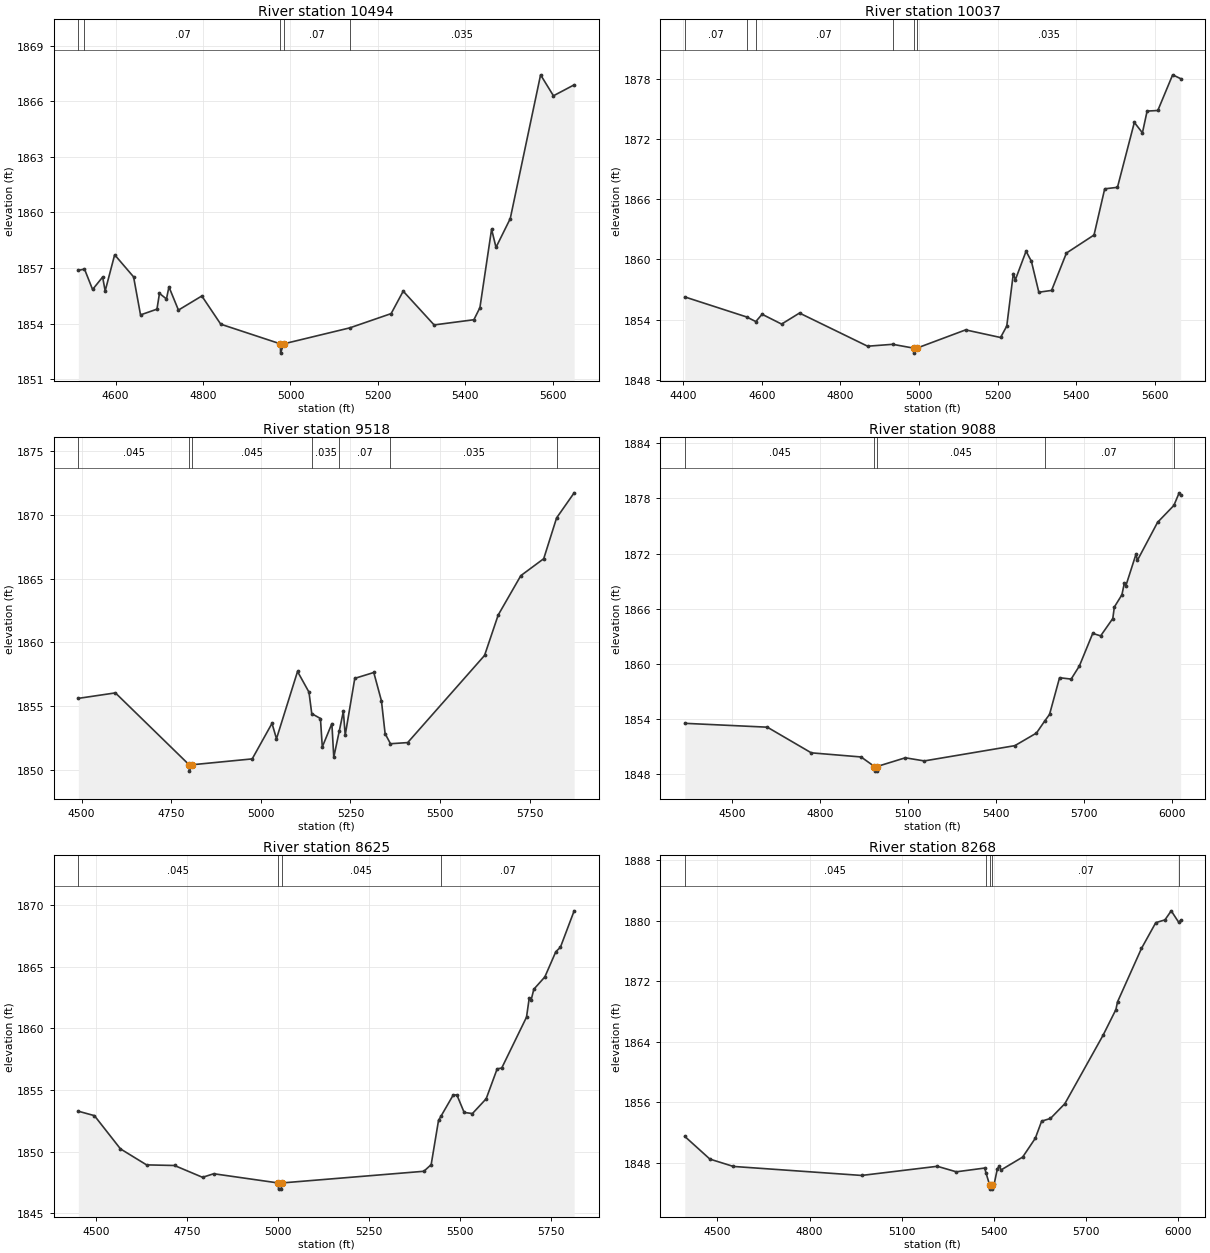
Type RM Length L Ch R = 1,10494,457,457,457
BEGIN DESCRIPTION:
Mapping XS 88305e7f
END DESCRIPTION:
XS GIS Cut Line= 3
      1434783.40      6960002.82      1434364.60      6960238.83
      1433718.12      6960334.89
#Sta/Elev= 30
  4514.7 1856.88  4528.8 1856.95  4547.3 1855.85  4570.3 1856.52  4576.1 1855.77
  4597.8 1857.72  4641.1 1856.53  4657.0 1854.48  4694.6 1854.79  4700.3 1855.64
  4716.3 1855.34  4722.0 1855.99  4743.7 1854.74  4797.2 1855.50  4840.5 1853.98
  4976.9 1852.92  4977.4 1852.42  4984.4 1852.92  5135.5 1853.78  5230.3 1854.55
  5257.9 1855.76  5328.6 1853.94  5419.6 1854.22  5433.4 1854.87  5460.1 1859.10
  5470.2 1858.12  5502.8 1859.67  5572.2 1867.42  5601.6 1866.29  5649.0 1866.88
#Mann=5,-1,0
  4514.7   0.035       0  4528.8    0.07       0  4976.9    0.07       0
  4984.4    0.07       0  5135.5   0.035       0
Bank Sta=4976.9,4984.4
Exp/Cntr=0.3,0.1

Type RM Length L Ch R = 1,10037,519,519,519
BEGIN DESCRIPTION:
Mapping XS 89d47e72
END DESCRIPTION:
XS GIS Cut Line= 3
      1434765.50      6959719.75      1434195.33      6959869.03
      1433552.15      6960069.54
#Sta/Elev= 30
  4403.4 1856.26  4561.0 1854.26  4584.3 1853.80  4600.3 1854.53  4650.0 1853.55
  4695.6 1854.65  4869.1 1851.34  4932.9 1851.53  4986.2 1851.15  4986.7 1850.65
  4994.6 1851.15  5118.8 1852.97  5207.8 1852.21  5223.6 1853.35  5240.3 1858.59
  5245.5 1857.97  5272.8 1860.83  5286.4 1859.81  5305.3 1856.73  5337.8 1856.91
  5375.6 1860.64  5445.9 1862.44  5473.1 1867.05  5505.6 1867.20  5548.6 1873.68
  5569.2 1872.64  5581.1 1874.81  5608.4 1874.87  5646.2 1878.43  5666.5 1878.05
#Mann=6,-1,0
  4403.4    0.07       0  4561.0   0.035       0  4584.3    0.07       0
  4932.9   0.035       0  4986.2   0.035       0  4994.6   0.035       0
Bank Sta=4986.2,4994.6
Exp/Cntr=0.3,0.1

Type RM Length L Ch R = 1,9518,430,430,430
BEGIN DESCRIPTION:
Mapping XS 6ead269a
END DESCRIPTION:
XS GIS Cut Line= 3
      1434581.99      6959273.67      1434098.97      6959452.37
      1433273.47      6959720.59
#Sta/Elev= 30
  4490.9 1855.60  4594.3 1856.03  4799.9 1850.39  4800.4 1849.89  4808.3 1850.39
  4975.9 1850.85  5031.1 1853.64  5043.6 1852.43  5102.3 1857.71  5134.2 1856.09
  5142.0 1854.40  5166.2 1854.02  5171.4 1851.79  5198.1 1853.62  5203.4 1850.98
  5219.0 1853.07  5230.1 1854.58  5235.3 1852.71  5262.0 1857.17  5315.0 1857.63
  5336.4 1855.40  5346.6 1852.83  5361.6 1852.04  5409.6 1852.13  5624.0 1858.97
  5662.0 1862.14  5725.1 1865.23  5789.0 1866.56  5824.9 1869.76  5873.9 1871.73
#Mann=7,-1,0
  4490.9   0.045       0  4799.9    0.07       0  4808.3   0.045       0
  5142.0   0.035       0  5219.0    0.07       0  5361.6   0.035       0
  5824.9    0.07       0
Bank Sta=4799.9,4808.3
Exp/Cntr=0.3,0.1

Type RM Length L Ch R = 1,9088,463,463,463
BEGIN DESCRIPTION:
Clear Fork Trib4 8.0
END DESCRIPTION:
XS GIS Cut Line= 3
      1434666.68      6959092.99      1434005.00      6959088.00
      1433011.88      6959363.42
#Sta/Elev= 30
  4338.3 1853.53  4620.0 1853.11  4770.0 1850.32  4940.0 1849.87  4985.7 1848.83
  4986.2 1848.33  4993.7 1848.33  4994.2 1848.83  5090.9 1849.78  5155.7 1849.44
  5464.8 1851.10  5538.5 1852.47  5566.5 1853.77  5583.2 1854.50  5617.4 1858.49
  5656.9 1858.34  5684.9 1859.76  5730.6 1863.31  5757.6 1863.04  5799.1 1864.93
  5804.4 1866.18  5830.2 1867.51  5838.7 1868.81  5843.8 1868.50  5878.1 1871.91
  5883.3 1871.27  5951.9 1875.39  6007.6 1877.23  6025.6 1878.60  6030.6 1878.33
#Mann=5,-1,0
  4338.3   0.045       0  4985.7   0.045       0  4994.2   0.045       0
  5566.5    0.07       0  6007.6   0.035       0
Bank Sta=4985.7,4994.2
Exp/Cntr=0.3,0.1

Type RM Length L Ch R = 1,8625,357,357,357
BEGIN DESCRIPTION:
Clear Fork Trib4 7.0
END DESCRIPTION:
XS GIS Cut Line= 3
      1434447.92      6958811.74      1433905.00      6958688.00
      1433104.97      6958788.00
#Sta/Elev= 30
  4451.2 1853.28  4495.4 1852.92  4567.0 1850.22  4638.8 1848.92  4715.6 1848.87
  4792.7 1847.91  4823.4 1848.20  5001.2 1847.45  5001.7 1846.95  5009.3 1846.95
  5009.8 1847.45  5401.1 1848.40  5421.2 1848.94  5441.4 1852.53  5447.9 1852.86
  5481.7 1854.59  5491.8 1854.61  5511.9 1853.18  5534.6 1853.09  5572.4 1854.29
  5602.6 1856.72  5615.2 1856.79  5683.3 1860.92  5690.8 1862.47  5695.9 1862.30
  5703.4 1863.19  5733.7 1864.19  5763.9 1866.24  5776.5 1866.60  5814.3 1869.56
#Mann=4,-1,0
  4451.2   0.045       0  5001.2   0.045       0  5009.8   0.045       0
  5447.9    0.07       0
Bank Sta=5001.2,5009.8
Exp/Cntr=0.3,0.1

Type RM Length L Ch R = 1,8268,314,314,314
BEGIN DESCRIPTION:
Clear Fork Trib4 6.0
END DESCRIPTION:
XS GIS Cut Line= 3
      1434485.71      6958537.30      1433905.01      6958363.00
      1432925.33      6958603.20
#Sta/Elev= 30
  4393.7 1851.47  4475.5 1848.47  4552.0 1847.50  4969.6 1846.31  5216.2 1847.52
  5278.0 1846.79  5370.7 1847.29  5374.4 1846.69  5387.0 1845.00  5387.5 1844.50
  5395.1 1844.50  5395.6 1845.00  5401.6 1845.22  5411.9 1847.21  5418.5 1847.53
  5423.6 1847.03  5494.2 1848.74  5535.4 1851.23  5556.0 1853.49  5584.8 1853.85
  5631.6 1855.80  5756.3 1864.87  5797.9 1868.25  5803.1 1869.26  5881.1 1876.33
  5927.8 1879.75  5957.6 1880.11  5978.1 1881.31  6002.8 1879.77  6008.7 1880.06
#Mann=5,-1,0
  4393.7   0.045       0  5374.4    0.07       0  5387.0   0.045       0
  5395.6    0.07       0  6002.8   0.045       0
Bank Sta=5387,5395.6
Exp/Cntr=0.3,0.1

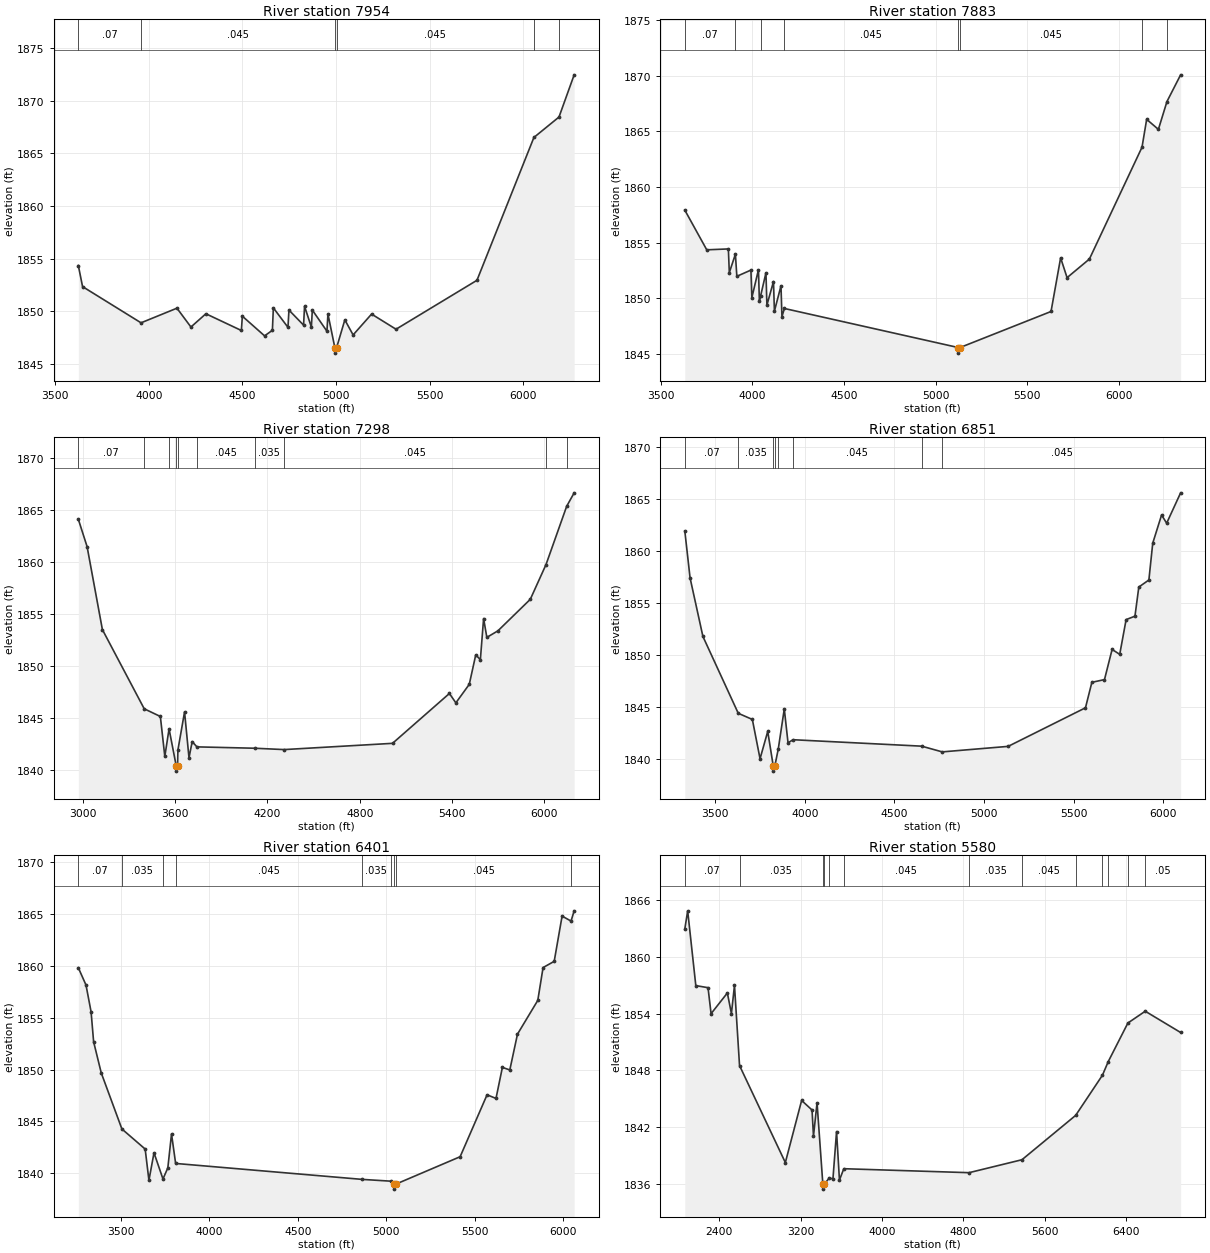
Type RM Length L Ch R = 1,7954,71,71,71
BEGIN DESCRIPTION:
Mapping XS 35ca6248
END DESCRIPTION:
XS GIS Cut Line= 5
      1435190.11      6958439.34      1434328.14      6958207.58
      1433848.97      6958090.39      1433245.52      6957960.55
      1432763.13      6958388.82
#Sta/Elev= 30
  3623.6 1854.33  3646.2 1852.33  3958.5 1848.89  4150.3 1850.28  4225.0 1848.49
  4304.9 1849.75  4494.4 1848.16  4499.6 1849.52  4618.4 1847.65  4660.1 1848.18
  4665.2 1850.31  4743.3 1848.46  4748.5 1850.10  4826.6 1848.67  4831.8 1850.46
  4868.2 1848.49  4873.4 1850.10  4951.5 1848.09  4956.7 1849.73  4993.9 1846.51
  4994.4 1846.01  5002.7 1846.51  5047.0 1849.17  5091.2 1847.74  5189.9 1849.72
  5320.4 1848.28  5752.7 1852.93  6056.8 1866.50  6190.8 1868.44  6271.8 1872.45
#Mann=6,-1,0
  3623.6    0.07       0  3958.5   0.045       0  4993.9   0.045       0
  5002.7   0.045       0  6056.8   0.035       0  6190.8   0.045       0
Bank Sta=4993.9,5002.7
Exp/Cntr=0.3,0.1

Type RM Length L Ch R = 1,7883,585,585,585
BEGIN DESCRIPTION:
Clear Fork Trib4 5.0
END DESCRIPTION:
XS GIS Cut Line= 4
      1435229.17      6958371.63      1433901.33      6958036.41
      1433268.04      6957909.35      1432724.34      6958337.90
#Sta/Elev= 30
  3630.5 1857.94  3750.4 1854.37  3868.4 1854.45  3873.6 1852.32  3906.8 1853.98
  3914.7 1851.99  3991.6 1852.55  3996.8 1850.08  4032.7 1852.58  4037.8 1849.79
  4044.8 1850.25  4073.7 1852.31  4078.9 1849.40  4114.8 1851.52  4119.9 1848.86
  4155.8 1851.14  4161.0 1848.37  4174.6 1849.10  5124.4 1845.59  5124.9 1845.09
  5133.2 1845.59  5630.5 1848.83  5682.9 1853.65  5718.1 1851.87  5840.0 1853.54
  6127.4 1863.59  6152.7 1866.09  6216.8 1865.19  6263.6 1867.69  6338.2 1870.09
#Mann=8,-1,0
  3630.5    0.07       0  3906.8   0.045       0  4044.8    0.07       0
  4174.6   0.045       0  5124.4   0.045       0  5133.2   0.045       0
  6127.4   0.035       0  6263.6   0.045       0
Bank Sta=5124.4,5133.2
Exp/Cntr=0.3,0.1

Type RM Length L Ch R = 1,7298,447,447,447
BEGIN DESCRIPTION:
Clear Fork Trib4 4.0
END DESCRIPTION:
XS GIS Cut Line= 3
      1434955.02      6955987.98      1433705.00      6957588.00
      1432709.16      6958248.70
#Sta/Elev= 30
  2969.7 1864.08  3026.7 1861.45  3126.2 1853.48  3398.3 1845.87  3503.3 1845.13
  3532.3 1841.29  3559.9 1843.94  3606.6 1840.38  3607.1 1839.88  3615.4 1840.38
  3617.3 1841.89  3660.7 1845.57  3689.6 1841.16  3710.4 1842.72  3741.0 1842.21
  4115.8 1842.08  4308.7 1841.95  5013.6 1842.55  5383.6 1847.34  5425.7 1846.44
  5512.9 1848.22  5555.0 1851.05  5585.1 1850.59  5606.1 1854.54  5627.2 1852.73
  5699.3 1853.36  5909.9 1856.39  6012.2 1859.73  6146.6 1865.33  6195.2 1866.62
#Mann=10,-1,0
  2969.7    0.07       0  3398.3   0.035       0  3559.9    0.07       0
  3606.6   0.045       0  3615.4    0.07       0  3741.0   0.045       0
  4115.8   0.035       0  4308.7   0.045       0  6012.2   0.035       0
  6146.6   0.045       0
Bank Sta=3606.6,3615.4
Exp/Cntr=0.3,0.1

Type RM Length L Ch R = 1,6851,450,450,450
BEGIN DESCRIPTION:
Clear Fork Trib4 3.0
END DESCRIPTION:
XS GIS Cut Line= 3
      1434729.19      6955910.69      1433655.00      6957188.00
      1432855.03      6957937.97
#Sta/Elev= 30
  3331.3 1861.92  3360.8 1857.39  3432.3 1851.77  3629.5 1844.38  3708.1 1843.79
  3751.0 1840.01  3793.9 1842.64  3824.6 1839.32  3825.1 1838.82  3833.5 1839.32
  3852.6 1840.94  3886.2 1844.80  3907.1 1841.54  3934.9 1841.84  4652.4 1841.22
  4767.3 1840.67  5134.8 1841.20  5566.1 1844.91  5601.8 1847.36  5672.1 1847.62
  5714.6 1850.52  5757.1 1850.05  5792.8 1853.39  5842.1 1853.72  5863.6 1856.52
  5919.8 1857.20  5941.3 1860.74  5990.6 1863.45  6018.9 1862.66  6096.8 1865.58
#Mann=8,-1,0
  3331.3    0.07       0  3629.5   0.035       0  3824.6   0.045       0
  3833.5   0.035       0  3852.6    0.07       0  3934.9   0.045       0
  4652.4   0.035       0  4767.3   0.045       0
Bank Sta=3824.6,3833.5
Exp/Cntr=0.3,0.1

Type RM Length L Ch R = 1,6401,821,821,821
BEGIN DESCRIPTION:
Clear Fork Trib4 2.0
END DESCRIPTION:
XS GIS Cut Line= 3
      1434645.87      6955827.35      1433305.00      6956938.00
      1432703.14      6957811.75
#Sta/Elev= 30
  3259.1 1859.83  3302.5 1858.16  3331.2 1855.57  3345.5 1852.68  3388.5 1849.68
  3505.3 1844.26  3636.8 1842.32  3658.1 1839.30  3686.7 1841.96  3737.4 1839.43
  3764.9 1840.50  3785.7 1843.78  3809.0 1840.93  4863.8 1839.39  5023.4 1839.22
  5043.1 1838.95  5043.6 1838.45  5056.0 1838.95  5416.8 1841.58  5569.0 1847.56
  5619.5 1847.21  5655.6 1850.21  5697.5 1849.96  5740.9 1853.42  5855.7 1856.68
  5885.5 1859.85  5948.4 1860.45  5993.0 1864.82  6043.6 1864.34  6061.2 1865.33
#Mann=9,-1,0
  3259.1    0.07       0  3505.3   0.035       0  3737.4    0.07       0
  3809.0   0.045       0  4863.8   0.035       0  5023.4   0.045       0
  5043.1   0.035       0  5056.0   0.045       0  6043.6    0.07       0
Bank Sta=5043.1,5056
Exp/Cntr=0.3,0.1

Type RM Length L Ch R = 1,5580,920,920,920
BEGIN DESCRIPTION:
Mapping XS bdf6d353
END DESCRIPTION:
XS GIS Cut Line= 4
      1435113.25      6955320.34      1433941.38      6955283.45
      1432796.89      6956598.20      1431764.00      6958263.89
#Sta/Elev= 30
  2062.3 1862.96  2090.6 1864.89  2170.6 1856.98  2290.7 1856.76  2320.7 1854.01
  2480.8 1856.20  2520.8 1854.02  2550.8 1857.00  2600.6 1848.52  3051.0 1838.26
  3211.1 1844.83  3313.4 1843.82  3327.6 1841.06  3362.7 1844.59  3419.9 1835.95
  3420.4 1835.45  3432.9 1835.95  3481.1 1836.61  3519.2 1836.55  3554.5 1841.54
  3583.0 1836.41  3625.9 1837.61  4857.4 1837.19  5377.8 1838.56  5905.6 1843.25
  6169.0 1847.50  6226.5 1848.95  6419.2 1853.02  6589.8 1854.27  6937.8 1852.02
#Mann=13,-1,0
  2062.3    0.07       0  2600.6   0.035       0  3419.9   0.035       0
  3432.9   0.035       0  3481.1    0.07       0  3625.9   0.045       0
  4857.4   0.035       0  5377.8   0.045       0  5905.6    0.07       0
  6169.0   0.045       0  6226.5    0.05       0  6419.2   0.045       0
  6589.8    0.05       0
Bank Sta=3419.9,3432.9
Exp/Cntr=0.3,0.1

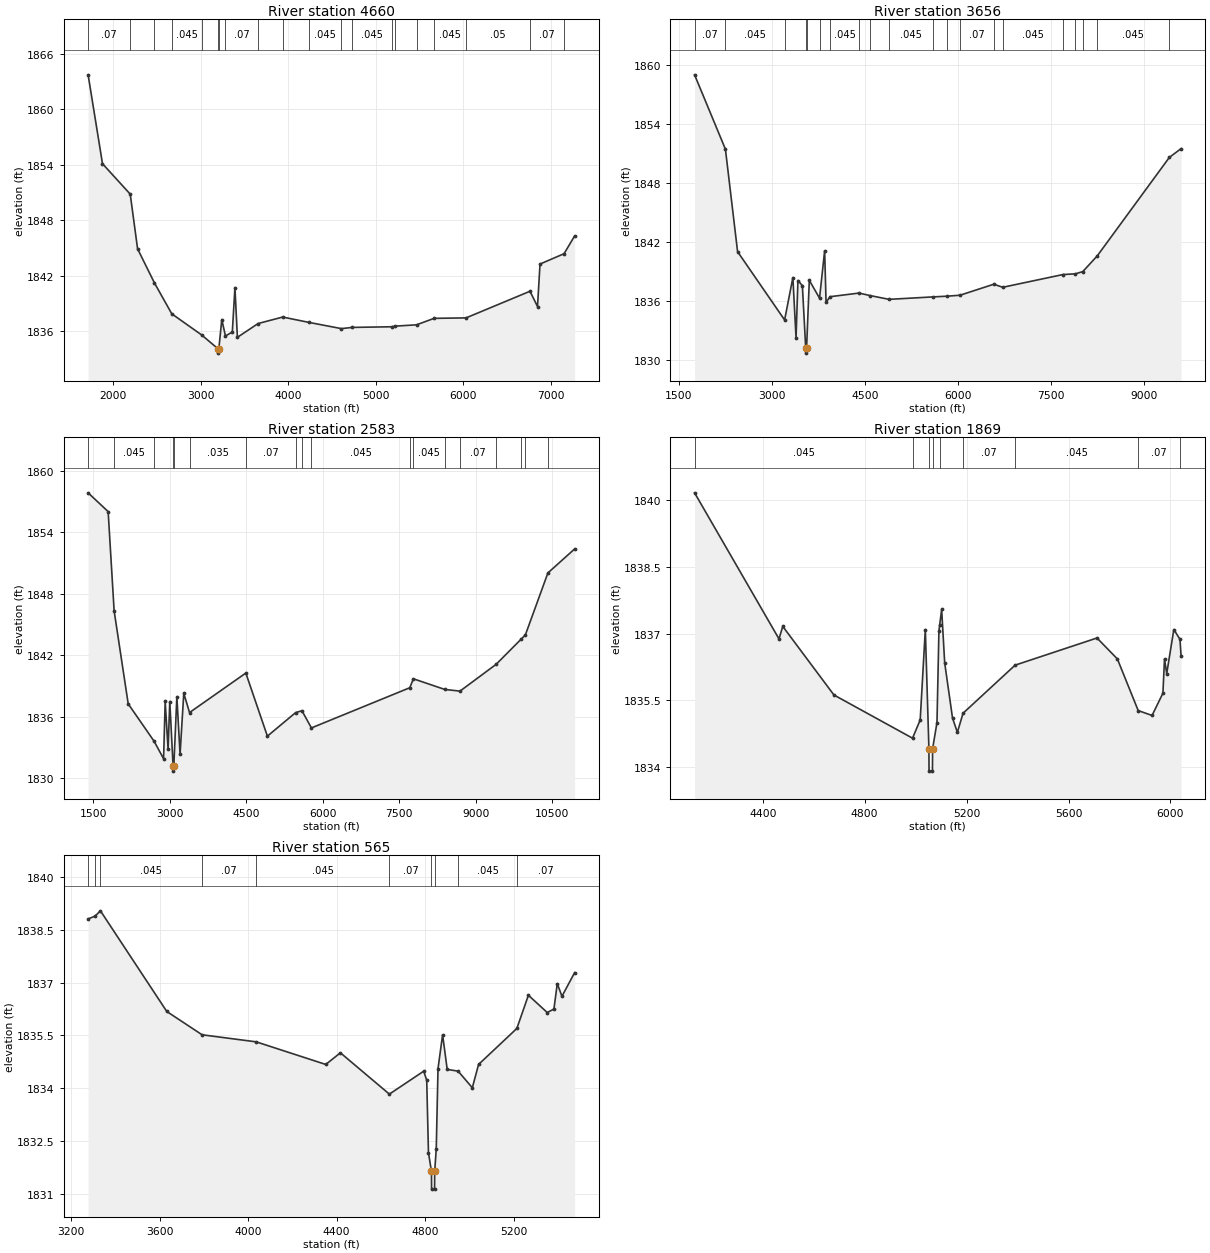
Type RM Length L Ch R = 1,4660,1004,1004,1004
BEGIN DESCRIPTION:
Mapping XS 0e6b2a02
END DESCRIPTION:
XS GIS Cut Line= 4
      1435098.94      6955246.16      1433409.23      6955145.06
      1432229.18      6956197.16      1430849.27      6958015.57
#Sta/Elev= 30
  1715.9 1863.71  1880.1 1854.10  2196.8 1850.81  2280.8 1844.90  2473.4 1841.21
  2671.4 1837.87  3013.3 1835.58  3195.6 1834.12  3196.1 1833.62  3209.3 1834.12
  3242.6 1837.24  3284.5 1835.48  3362.8 1835.90  3392.8 1840.71  3420.8 1835.33
  3657.4 1836.82  3938.2 1837.52  4239.3 1836.94  4608.9 1836.27  4731.3 1836.40
  5182.0 1836.47  5226.1 1836.54  5466.8 1836.68  5667.3 1837.38  6032.2 1837.43
  6762.5 1840.31  6848.5 1838.66  6877.0 1843.25  7151.7 1844.37  7272.3 1846.29
#Mann=20,-1,0
  1715.9    0.07       0  2196.8   0.035       0  2473.4    0.07       0
  2671.4   0.045       0  3013.3   0.035       0  3195.6   0.045       0
  3209.3   0.035       0  3284.5    0.07       0  3657.4   0.045       0
  3938.2   0.035       0  4239.3   0.045       0  4608.9    0.07       0
  4731.3   0.045       0  5182.0    0.07       0  5226.1   0.045       0
  5466.8   0.035       0  5667.3   0.045       0  6032.2    0.05       0
  6762.5    0.07       0  7151.7    0.05       0
Bank Sta=3195.6,3209.3
Exp/Cntr=0.3,0.1

Type RM Length L Ch R = 1,3656,1073,1073,1073
BEGIN DESCRIPTION:
Mapping XS dbcacff2
END DESCRIPTION:
XS GIS Cut Line= 5
      1435230.87      6955162.83      1433265.61      6954787.83
      1432213.56      6955441.95      1430841.69      6956455.57
      1430185.26      6959274.19
#Sta/Elev= 30
  1757.3 1859.03  2254.3 1851.45  2450.2 1841.01  3208.0 1834.05  3341.2 1838.37
  3392.1 1832.23  3422.7 1838.07  3494.0 1837.55  3548.1 1831.17  3548.6 1830.67
  3561.9 1831.17  3605.9 1838.09  3770.9 1836.27  3852.9 1841.10  3876.0 1835.84
  3939.0 1836.42  4407.1 1836.79  4589.5 1836.53  4891.1 1836.15  5598.3 1836.40
  5819.8 1836.47  6034.4 1836.57  6578.0 1837.69  6723.2 1837.38  7694.6 1838.68
  7894.3 1838.75  8013.0 1838.98  8244.5 1840.57  9408.0 1850.62  9596.6 1851.51
#Mann=20,-1,0
  1757.3    0.07       0  2254.3   0.045       0  3208.0    0.07       0
  3548.1   0.045       0  3561.9   0.035       0  3770.9    0.07       0
  3939.0   0.045       0  4407.1   0.045       0  4589.5   0.045       0
  4891.1   0.045       0  5598.3    0.07       0  5819.8   0.045       0
  6034.4    0.07       0  6578.0   0.035       0  6723.2   0.045       0
  7694.6    0.07       0  7894.3   0.045       0  8013.0    0.07       0
  8244.5   0.045       0  9408.0    0.05       0
Bank Sta=3548.1,3561.9
Exp/Cntr=0.3,0.1

Type RM Length L Ch R = 1,2583,714,714,714
BEGIN DESCRIPTION:
Mapping XS 16281155
END DESCRIPTION:
XS GIS Cut Line= 5
      1435235.09      6955114.03      1432943.41      6954442.15
      1431791.68      6954842.99      1430308.83      6955053.18
      1429538.87      6959420.53
#Sta/Elev= 30
  1402.1 1857.83  1794.9 1856.00  1912.2 1846.32  2188.3 1837.26  2697.6 1833.60
  2882.0 1831.91  2913.2 1837.49  2970.1 1832.84  3003.5 1837.48  3068.3 1831.20
  3068.8 1830.70  3082.7 1831.20  3142.3 1837.96  3205.0 1832.34  3278.0 1838.29
  3390.7 1836.41  4494.6 1840.26  4917.3 1834.11  5470.0 1836.40  5594.8 1836.59
  5780.7 1834.91  7709.9 1838.83  7780.4 1839.70  8397.8 1838.66  8694.5 1838.50
  9402.6 1841.11  9890.1 1843.55  9976.6 1843.98 10417.9 1850.02 10942.1 1852.36
#Mann=18,-1,0
  1402.1    0.07       0  1912.2   0.045       0  2697.6    0.07       0
  3068.3    0.07       0  3082.7    0.07       0  3390.7   0.035       0
  4494.6    0.07       0  5470.0   0.045       0  5594.8    0.07       0
  5780.7   0.045       0  7709.9   0.035       0  7780.4   0.045       0
  8397.8   0.035       0  8694.5    0.07       0  9402.6   0.045       0
  9890.1   0.035       0  9976.6   0.045       0 10417.9    0.05       0
Bank Sta=3068.3,3082.7
Exp/Cntr=0.3,0.1

Type RM Length L Ch R = 1,1869,1304,1304,1304
BEGIN DESCRIPTION:
Mapping XS d8ebc7e2
END DESCRIPTION:
XS GIS Cut Line= 5
      1432484.42      6954520.10      1432138.40      6954280.47
      1431687.52      6954186.74      1430966.52      6953915.89
      1430819.19      6953704.59
#Sta/Elev= 30
  4132.6 1840.16  4463.8 1836.88  4478.7 1837.16  4679.5 1835.62  4987.9 1834.65
  5018.0 1835.06  5038.1 1837.09  5052.2 1834.41  5052.7 1833.91  5066.1 1833.91
  5066.6 1834.41  5083.8 1835.00  5091.5 1837.06  5094.6 1837.20  5102.2 1837.54
  5114.1 1836.34  5144.9 1835.10  5163.9 1834.78  5186.1 1835.21  5390.5 1836.29
  5711.8 1836.90  5791.7 1836.43  5873.5 1835.27  5927.9 1835.16  5970.5 1835.66
  5976.7 1836.43  5985.4 1836.10  6013.3 1837.09  6037.4 1836.87  6041.8 1836.49
#Mann=9,-1,0
  4132.6   0.045       0  4987.9    0.07       0  5052.2    0.07       0
  5066.6    0.07       0  5094.6   0.045       0  5186.1    0.07       0
  5390.5   0.045       0  5873.5    0.07       0  6037.4    0.16       0
Bank Sta=5052.2,5066.6
Exp/Cntr=0.3,0.1

Type RM Length L Ch R = 1,565,0,0,0
BEGIN DESCRIPTION:
Mapping XS 4905ba9d
END DESCRIPTION:
XS GIS Cut Line= 4
      1432619.79      6954462.76      1431929.53      6953147.93
      1431710.78      6952969.07      1431350.27      6952732.80
#Sta/Elev= 30
  3276.8 1838.80  3308.0 1838.88  3332.5 1839.03  3632.3 1836.18  3791.9 1835.52
  4036.5 1835.32  4350.8 1834.68  4416.9 1835.01  4638.2 1833.84  4793.5 1834.49
  4807.0 1834.23  4814.9 1832.18  4828.5 1831.65  4829.0 1831.15  4842.5 1831.15
  4843.0 1831.65  4850.1 1832.29  4858.0 1834.56  4878.8 1835.52  4899.6 1834.54
  4949.0 1834.49  5013.1 1834.02  5041.3 1834.68  5214.4 1835.70  5266.5 1836.64
  5351.7 1836.15  5381.9 1836.25  5397.0 1836.97  5418.1 1836.61  5475.4 1837.28
#Mann=10,-1,0
  3276.8   0.035       0  3308.0    0.07       0  3332.5   0.045       0
  3791.9    0.07       0  4036.5   0.045       0  4638.2    0.07       0
  4828.5   0.045       0  4843.0    0.07       0  4949.0   0.045       0
  5214.4    0.07       0
Bank Sta=4828.5,4843
Exp/Cntr=0.3,0.1

Chan Stop Cuts=-1