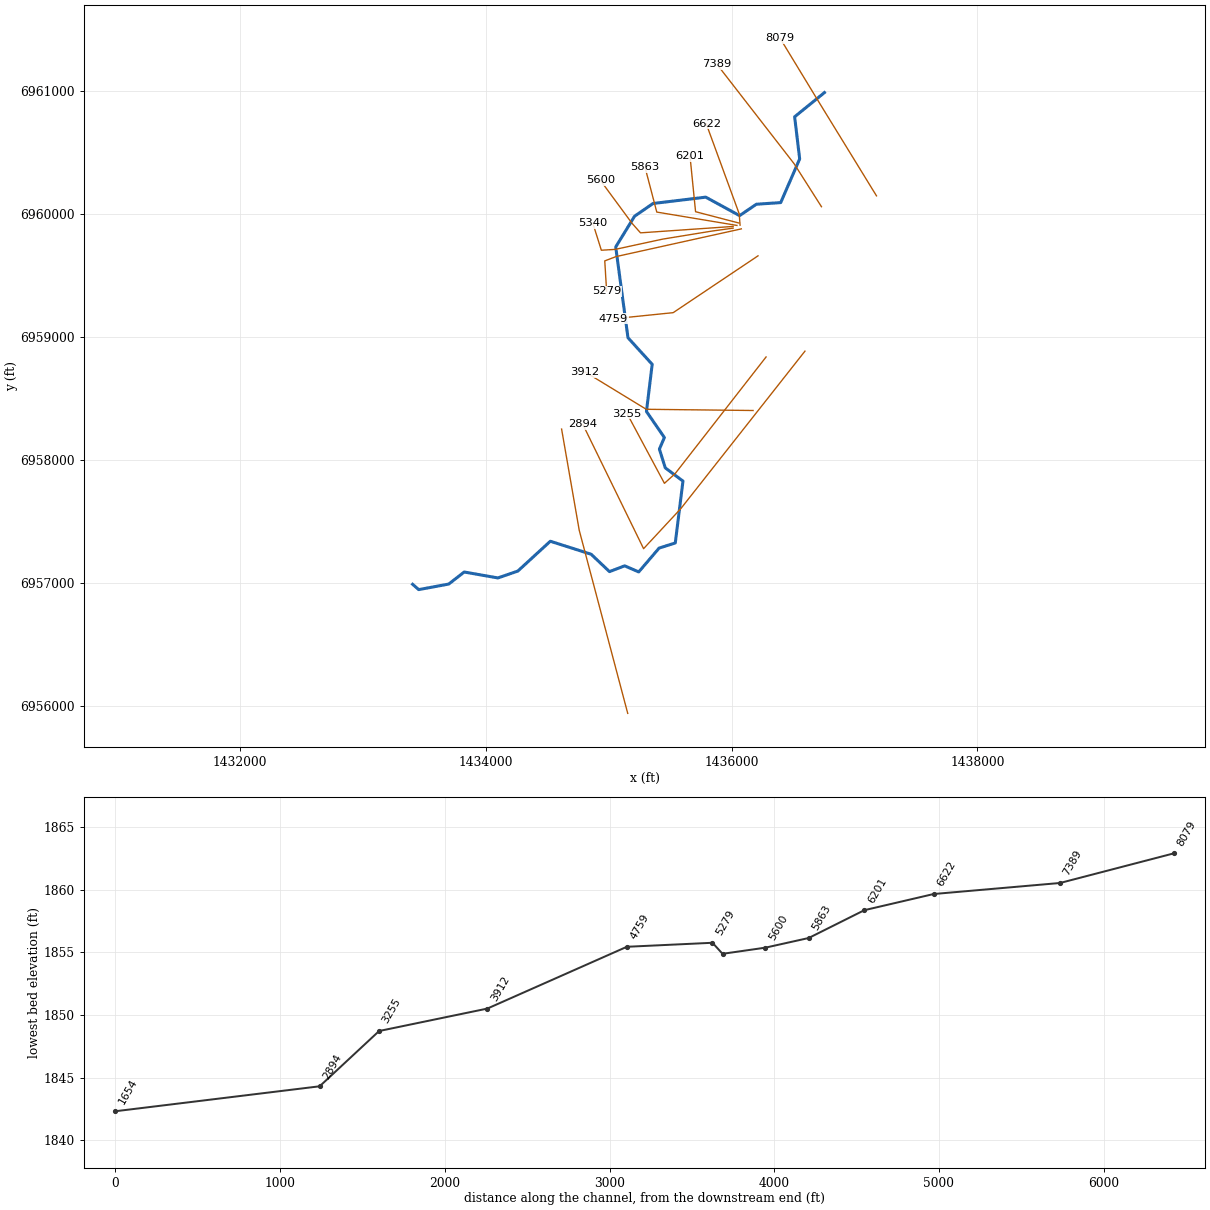
--- Clear Fork Trib4_1.prj (project) ---

Proj Title=Clear Fork Trib4_1 Base Level Engineering
Current Plan=p01
Default Exp/Contr=0.3,0.1
English Units
Geom File=g01
Flow File=f01
Plan File=p01
BEGIN DESCRIPTION:
Clear Fork Trib4_1
END DESCRIPTION:

--- Clear Fork Trib4_1.p01 (plan) ---

Plan Title=Multiple Run
Short Identifier=Multiple
Geom File=g01
Flow File=f01
Subcritical Flow
K Sum by GR= 0
Std Step Tol= 0.01
Critical Tol= 0.01
Num of Std Step Trials= 20
Max Error Tol= 0.3
Flow Tol Ratio= 0.001
Split Flow NTrial= 30
Split Flow Tol= 0.02
Split Flow Ratio= 0.02
Log Output Level= 0
Friction Slope Method= 1
Unsteady Friction Slope Method= 2
Unsteady Bridges Friction Slope Method= 1
Parabolic Critical Depth
Global Vel Dist=  1 , 1 , 1
Global Log Level= 0
CheckData=True
Encroach Param= -1, 0, 0, 0
BEGIN DESCRIPTION:
Multiple Run
END DESCRIPTION:

--- Clear Fork Trib4_1.f01 (steady flow) ---

Flow Title=Multiple
Number of Profiles=7
Profile Names=10-year,25-year,50-year,1pct_min,100-year,1pct_plu,500-year
River Rch & RM= Clear Fork Trib4,Reach-1,8079
     234     322     395     241     480     958     718
River Rch & RM= Clear Fork Trib4,Reach-1,6201
     380     537     669     414     825    1647    1272
Boundary for River Rch & Prof#=Clear Fork Trib4,Reach-1,1
Up Type=0
Dn Type=3
Dn Slope=0.005
Boundary for River Rch & Prof#=Clear Fork Trib4,Reach-1,2
Up Type=0
Dn Type=3
Dn Slope=0.005
Boundary for River Rch & Prof#=Clear Fork Trib4,Reach-1,3
Up Type=0
Dn Type=3
Dn Slope=0.005
Boundary for River Rch & Prof#=Clear Fork Trib4,Reach-1,4
Up Type=0
Dn Type=3
Dn Slope=0.005
Boundary for River Rch & Prof#=Clear Fork Trib4,Reach-1,5
Up Type=0
Dn Type=3
Dn Slope=0.005
Boundary for River Rch & Prof#=Clear Fork Trib4,Reach-1,6
Up Type=0
Dn Type=3
Dn Slope=0.005
Boundary for River Rch & Prof#=Clear Fork Trib4,Reach-1,7
Up Type=0
Dn Type=3
Dn Slope=0.005

--- Clear Fork Trib4_1.g01 (geometry) ---

Geom Title=Existing Conditions

River Reach=Clear Fork Trib4,Reach-1
Reach XY= 30
      1436755.00      6960988.00      1436512.82      6960791.41
      1436553.81      6960448.50      1436399.53      6960093.26
      1436201.67      6960079.99      1436065.07      6959987.16
      1435789.79      6960137.49      1435360.86      6960085.93
      1435210.62      6959982.38      1435057.24      6959732.07
      1435157.07      6958993.86      1435353.96      6958777.56
      1435307.24      6958393.93      1435453.34      6958181.95
      1435412.59      6958088.01      1435460.42      6957935.33
      1435604.42      6957827.51      1435541.76      6957324.28
      1435410.48      6957282.74      1435244.38      6957088.60
      1435130.00      6957138.38      1435006.63      6957091.13
      1434857.45      6957232.53      1434525.35      6957338.31
      1434261.17      6957095.86      1434098.88      6957039.82
      1433824.99      6957088.04      1433699.14      6956990.07
      1433454.86      6956944.91      1433405.00      6956988.00

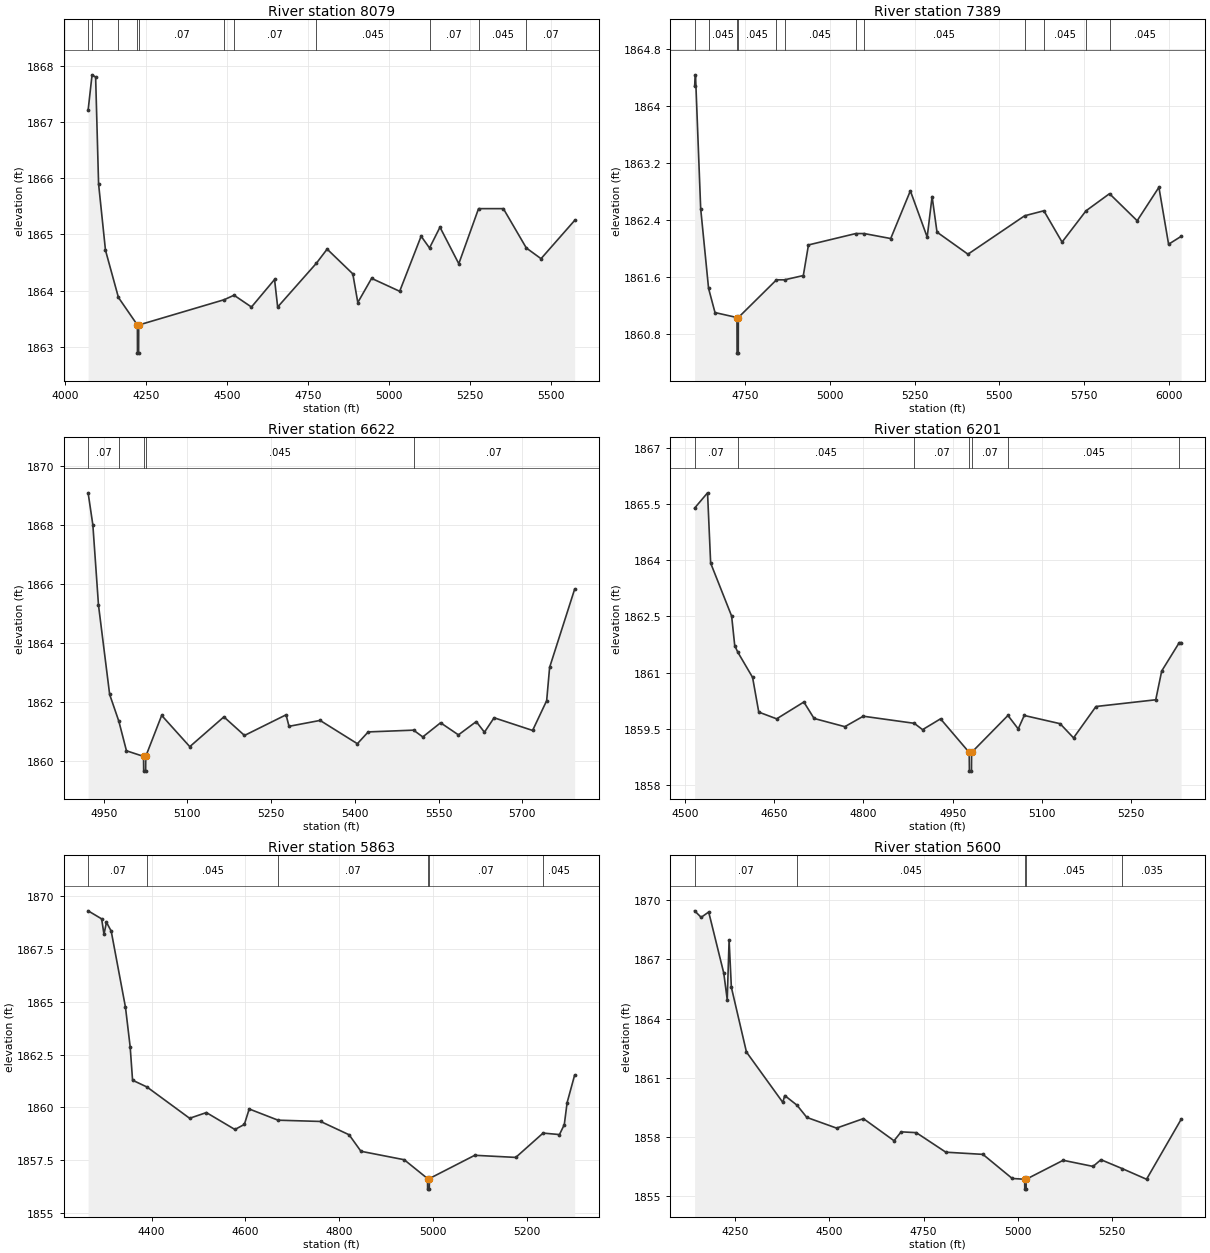
Type RM Length L Ch R = 1,8079,690,690,690
BEGIN DESCRIPTION:
Mapping XS 3cac1e21
END DESCRIPTION:
XS GIS Cut Line= 3
      1437178.57      6960148.21      1436692.46      6960939.89
      1436394.84      6961429.52
#Sta/Elev= 30
  4071.5 1867.21  4083.7 1867.84  4094.7 1867.80  4103.8 1865.90  4125.1 1864.72
  4165.1 1863.88  4223.7 1863.39  4223.9 1862.89  4227.4 1862.89  4227.7 1863.39
  4491.5 1863.84  4522.0 1863.92  4575.8 1863.71  4647.1 1864.20  4656.7 1863.71
  4776.4 1864.49  4809.4 1864.74  4888.7 1864.30  4904.1 1863.79  4946.7 1864.22
  5033.4 1863.99  5099.6 1864.97  5125.5 1864.76  5157.8 1865.13  5215.9 1864.48
  5276.9 1865.46  5353.5 1865.46  5424.4 1864.76  5469.8 1864.57  5573.5 1865.25
#Mann=11,-1,0
  4071.5    0.07       0  4083.7   0.045       0  4165.1    0.07       0
  4223.7   0.045       0  4227.7    0.07       0  4491.5   0.045       0
  4522.0    0.07       0  4776.4   0.045       0  5125.5    0.07       0
  5276.9   0.045       0  5424.4    0.07       0
Bank Sta=4223.7,4227.7
Exp/Cntr=0.3,0.1

Type RM Length L Ch R = 1,7389,767,767,767
BEGIN DESCRIPTION:
Mapping XS 9cca1bd5
END DESCRIPTION:
XS GIS Cut Line= 3
      1436730.97      6960059.90      1436508.47      6960409.65
      1435881.72      6961217.13
#Sta/Elev= 30
  4599.8 1864.28  4602.5 1864.44  4617.8 1862.56  4641.1 1861.44  4660.1 1861.10
  4725.0 1861.03  4725.3 1860.53  4728.8 1860.53  4729.0 1861.03  4841.7 1861.56
  4865.5 1861.56  4920.9 1861.62  4936.1 1862.05  5075.8 1862.21  5100.6 1862.21
  5179.0 1862.14  5237.0 1862.81  5286.7 1862.16  5301.2 1862.73  5315.7 1862.23
  5407.1 1861.92  5574.6 1862.46  5631.3 1862.53  5685.0 1862.09  5755.8 1862.53
  5825.1 1862.77  5906.8 1862.39  5971.0 1862.86  5999.6 1862.06  6036.5 1862.17
#Mann=12,-1,0
  4599.8    0.07       0  4641.1   0.045       0  4725.0   0.045       0
  4729.0   0.045       0  4841.7    0.07       0  4865.5   0.045       0
  5075.8    0.07       0  5100.6   0.045       0  5574.6    0.07       0
  5631.3   0.045       0  5755.8    0.07       0  5825.1   0.045       0
Bank Sta=4725,4729
Exp/Cntr=0.3,0.1

Type RM Length L Ch R = 1,6622,421,421,421
BEGIN DESCRIPTION:
Mapping XS 60468724
END DESCRIPTION:
XS GIS Cut Line= 3
      1436068.98      6959909.49      1436061.77      6960002.22
      1435794.04      6960733.55
#Sta/Elev= 30
  4922.1 1869.09  4930.6 1868.00  4940.7 1865.28  4960.7 1862.25  4977.2 1861.34
  4990.8 1860.34  5021.4 1860.15  5021.7 1859.65  5025.2 1859.65  5025.4 1860.15
  5053.9 1861.54  5104.3 1860.48  5165.4 1861.49  5202.3 1860.86  5276.8 1861.56
  5282.1 1861.17  5337.8 1861.37  5404.6 1860.58  5424.0 1860.98  5505.3 1861.04
  5521.8 1860.81  5553.7 1861.29  5585.7 1860.88  5617.6 1861.33  5632.3 1860.97
  5649.6 1861.46  5718.6 1861.03  5743.8 1862.04  5749.1 1863.17  5793.9 1865.82
#Mann=5,-1,0
  4922.1    0.07       0  4977.2   0.045       0  5021.4   0.045       0
  5025.4   0.045       0  5505.3    0.07       0
Bank Sta=5021.4,5025.4
Exp/Cntr=0.3,0.1

Type RM Length L Ch R = 1,6201,338,338,338
BEGIN DESCRIPTION:
Mapping XS a2e42882
END DESCRIPTION:
XS GIS Cut Line= 3
      1436059.37      6959927.03      1435706.90      6960019.06
      1435661.77      6960470.42
#Sta/Elev= 30
  4516.1 1865.40  4537.9 1865.81  4543.1 1863.93  4578.4 1862.51  4583.6 1861.72
  4588.9 1861.54  4613.6 1860.87  4624.0 1859.94  4654.1 1859.76  4699.8 1860.21
  4717.0 1859.77  4768.7 1859.55  4799.7 1859.83  4885.4 1859.64  4899.4 1859.47
  4929.6 1859.76  4977.8 1858.86  4978.1 1858.36  4981.6 1858.36  4981.8 1858.86
  5042.9 1859.85  5060.2 1859.49  5070.3 1859.85  5130.6 1859.63  5153.2 1859.25
  5190.9 1860.09  5291.4 1860.27  5301.4 1861.04  5330.9 1861.80  5334.0 1861.80
#Mann=7,-1,0
  4516.1    0.07       0  4588.9   0.045       0  4885.4    0.07       0
  4977.8    0.07       0  4981.8    0.07       0  5042.9   0.045       0
  5330.9    0.07       0
Bank Sta=4977.8,4981.8
Exp/Cntr=0.3,0.1

Type RM Length L Ch R = 1,5863,263,263,263
BEGIN DESCRIPTION:
Mapping XS 9ca2707c
END DESCRIPTION:
XS GIS Cut Line= 3
      1436043.55      6959907.47      1435391.32      6960016.16
      1435296.13      6960379.26
#Sta/Elev= 30
  4264.7 1869.30  4293.5 1868.92  4298.5 1868.19  4303.8 1868.76  4313.9 1868.34
  4344.3 1864.74  4354.3 1862.87  4359.4 1861.29  4390.1 1860.97  4481.0 1859.49
  4516.7 1859.76  4577.5 1858.96  4597.6 1859.20  4607.9 1859.93  4669.4 1859.40
  4760.0 1859.34  4820.8 1858.71  4846.0 1857.93  4938.2 1857.53  4987.9 1856.64
  4988.1 1856.14  4991.6 1856.14  4991.9 1856.64  5088.5 1857.74  5175.9 1857.64
  5234.1 1858.79  5269.0 1858.72  5279.3 1859.19  5285.3 1860.23  5301.3 1861.53
#Mann=6,-1,0
  4264.7    0.07       0  4390.1   0.045       0  4669.4    0.07       0
  4987.9    0.07       0  4991.9    0.07       0  5234.1   0.045       0
Bank Sta=4987.9,4991.9
Exp/Cntr=0.3,0.1

Type RM Length L Ch R = 1,5600,260,260,260
BEGIN DESCRIPTION:
Mapping XS 73a60df3
END DESCRIPTION:
XS GIS Cut Line= 4
      1436012.44      6959899.26      1435258.99      6959847.18
      1435189.47      6959925.43      1434933.12      6960273.62
#Sta/Elev= 30
  4141.7 1869.46  4159.2 1869.13  4179.2 1869.40  4219.3 1866.30  4228.4 1864.96
  4233.4 1867.98  4239.4 1865.59  4279.5 1862.31  4376.1 1859.76  4381.1 1860.11
  4413.7 1859.62  4439.9 1859.00  4518.8 1858.46  4590.2 1858.94  4671.5 1857.82
  4690.4 1858.27  4730.5 1858.23  4809.1 1857.24  4907.6 1857.13  4985.4 1855.91
  5018.5 1855.87  5018.8 1855.37  5022.3 1855.37  5022.5 1855.87  5120.8 1856.83
  5200.2 1856.52  5221.1 1856.86  5277.5 1856.41  5342.2 1855.87  5434.0 1858.90
#Mann=5,-1,0
  4141.7    0.07       0  4413.7   0.045       0  5018.5   0.045       0
  5022.5   0.045       0  5277.5   0.035       0
Bank Sta=5018.5,5022.5
Exp/Cntr=0.3,0.1

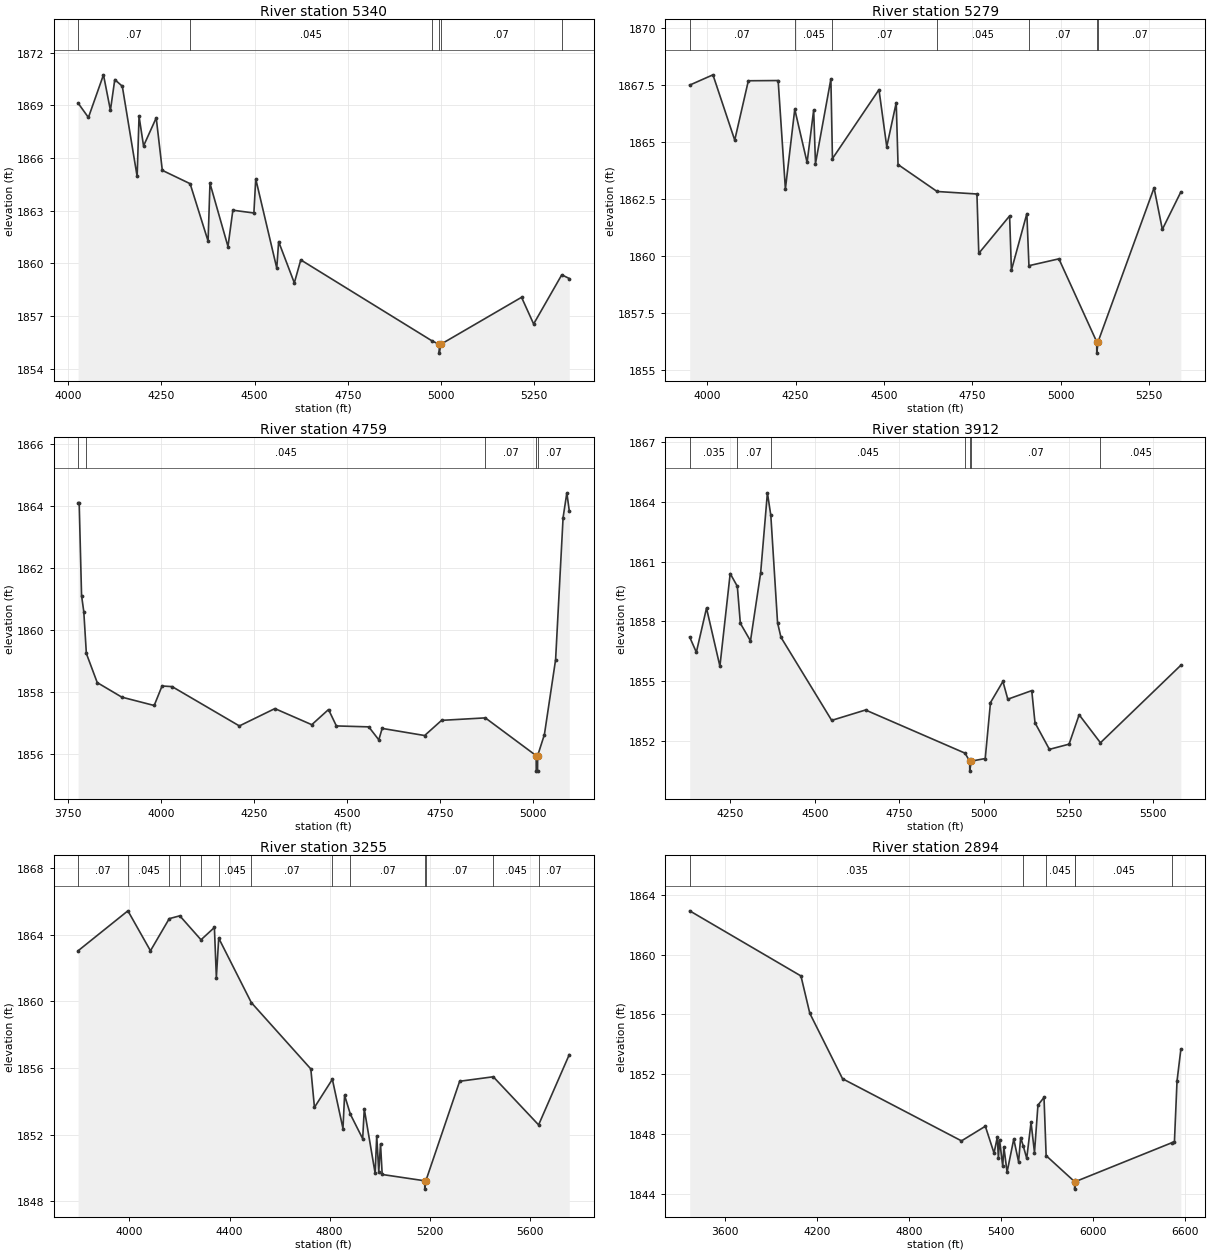
Type RM Length L Ch R = 1,5340,61,61,61
BEGIN DESCRIPTION:
Mapping XS 82c1a731
END DESCRIPTION:
XS GIS Cut Line= 6
      1436012.46      6959885.37      1435837.11      6959861.07
      1435438.64      6959795.98      1435053.22      6959712.65
      1434940.38      6959705.70      1434871.42      6959924.64
#Sta/Elev= 30
  4026.5 1869.12  4054.2 1868.30  4094.6 1870.73  4113.2 1868.71  4124.9 1870.46
  4145.1 1870.08  4184.9 1864.94  4190.0 1868.37  4202.1 1866.68  4236.1 1868.28
  4252.4 1865.29  4327.0 1864.53  4375.2 1861.26  4380.3 1864.55  4428.6 1860.95
  4441.7 1863.02  4498.1 1862.86  4503.1 1864.80  4559.5 1859.72  4564.5 1861.23
  4606.6 1858.88  4623.9 1860.19  4975.8 1855.58  4995.3 1855.38  4995.5 1854.88
  4999.3 1855.38  5216.2 1858.06  5248.6 1856.54  5324.1 1859.34  5344.2 1859.13
#Mann=6,-1,0
  4026.5    0.07       0  4327.0   0.045       0  4975.8    0.07       0
  4995.3    0.07       0  4999.3    0.07       0  5324.1   0.035       0
Bank Sta=4995.3,4999.3
Exp/Cntr=0.3,0.1

Type RM Length L Ch R = 1,5279,520,520,520
BEGIN DESCRIPTION:
Mapping XS ade377f2
END DESCRIPTION:
XS GIS Cut Line= 4
      1436079.26      6959879.45      1435059.31      6959653.76
      1434968.17      6959619.04      1434983.31      6959372.36
#Sta/Elev= 30
  3950.6 1867.50  4016.4 1867.95  4078.0 1865.09  4116.5 1867.69  4200.8 1867.70
  4221.3 1862.95  4247.8 1866.44  4282.7 1864.11  4301.3 1866.41  4306.4 1864.06
  4350.0 1867.77  4354.4 1864.28  4486.0 1867.30  4508.0 1864.80  4534.8 1866.73
  4539.9 1864.02  4650.4 1862.84  4763.1 1862.73  4768.3 1860.13  4855.5 1861.77
  4860.6 1859.39  4904.3 1861.87  4910.2 1859.59  4994.9 1859.89  5101.8 1856.26
  5102.1 1855.76  5105.8 1856.26  5264.1 1863.00  5287.5 1861.18  5339.9 1862.82
#Mann=7,-1,0
  3950.6    0.07       0  4247.8   0.045       0  4354.4    0.07       0
  4650.4   0.045       0  4910.2    0.07       0  5101.8    0.07       0
  5105.8    0.07       0
Bank Sta=5101.8,5105.8
Exp/Cntr=0.3,0.1

Type RM Length L Ch R = 1,4759,847,847,847
BEGIN DESCRIPTION:
Mapping XS cfdd2760
END DESCRIPTION:
XS GIS Cut Line= 4
      1436214.89      6959660.09      1435524.78      6959197.85
      1435134.00      6959157.90      1435038.51      6959148.31
#Sta/Elev= 30
  3777.4 1864.11  3780.3 1864.11  3786.7 1861.11  3792.7 1860.59  3799.6 1859.24
  3828.8 1858.30  3894.8 1857.83  3981.8 1857.56  4002.9 1858.19  4030.0 1858.17
  4210.6 1856.90  4306.0 1857.46  4405.1 1856.94  4450.1 1857.43  4471.2 1856.90
  4558.2 1856.87  4585.2 1856.45  4594.2 1856.82  4708.3 1856.59  4753.8 1857.08
  4871.3 1857.16  5007.9 1855.94  5008.1 1855.44  5011.6 1855.44  5011.9 1855.94
  5030.0 1856.62  5060.1 1859.04  5080.2 1863.63  5090.3 1864.43  5096.8 1863.85
#Mann=5,-1,0
  3777.4   0.035       0  3799.6   0.045       0  4871.3    0.07       0
  5007.9    0.07       0  5011.9    0.07       0
Bank Sta=5007.9,5011.9
Exp/Cntr=0.3,0.1

Type RM Length L Ch R = 1,3912,657,657,657
BEGIN DESCRIPTION:
Mapping XS 6243ff64
END DESCRIPTION:
XS GIS Cut Line= 3
      1436174.69      6958401.94      1435305.81      6958411.76
      1434808.41      6958715.40
#Sta/Elev= 30
  4129.9 1857.22  4149.6 1856.46  4179.6 1858.67  4219.2 1855.76  4249.6 1860.40
  4270.7 1859.76  4279.6 1857.91  4309.6 1857.03  4339.6 1860.43  4359.6 1864.44
  4369.7 1863.31  4389.6 1857.94  4399.6 1857.21  4549.6 1853.05  4649.6 1853.57
  4943.6 1851.41  4957.4 1851.01  4957.7 1850.51  4961.9 1851.01  5003.4 1851.14
  5018.9 1853.94  5055.7 1855.00  5070.1 1854.11  5140.9 1854.54  5150.5 1852.93
  5193.1 1851.60  5251.2 1851.86  5281.0 1853.33  5343.9 1851.93  5581.6 1855.81
#Mann=7,-1,0
  4129.9   0.035       0  4270.7    0.07       0  4369.7   0.045       0
  4943.6    0.07       0  4957.4    0.07       0  4961.9    0.07       0
  5343.9   0.045       0
Bank Sta=4957.4,4961.9
Exp/Cntr=0.3,0.1

Type RM Length L Ch R = 1,3255,361,361,361
BEGIN DESCRIPTION:
Mapping XS d02204e6
END DESCRIPTION:
XS GIS Cut Line= 4
      1436280.41      6958837.38      1435539.73      6957887.15
      1435453.51      6957809.49      1435150.86      6958374.38
#Sta/Elev= 30
  3795.2 1863.04  3994.1 1865.44  4084.2 1863.04  4159.2 1864.97  4201.4 1865.14
  4286.1 1863.70  4339.6 1864.44  4347.4 1861.43  4356.8 1863.80  4486.9 1859.93
  4724.7 1855.94  4739.2 1853.63  4810.7 1855.32  4853.1 1852.36  4859.5 1854.36
  4882.6 1853.22  4931.8 1851.75  4938.2 1853.53  4981.6 1849.67  4987.9 1851.92
  4996.1 1849.77  5003.1 1851.44  5009.7 1849.60  5179.6 1849.22  5179.9 1848.72
  5184.1 1849.22  5319.1 1855.20  5453.4 1855.47  5634.4 1852.58  5756.9 1856.80
#Mann=13,-1,0
  3795.2    0.07       0  3994.1   0.045       0  4159.2    0.07       0
  4201.4   0.045       0  4286.1    0.07       0  4356.8   0.045       0
  4486.9    0.07       0  4810.7   0.045       0  4882.6    0.07       0
  5179.6    0.07       0  5184.1    0.07       0  5453.4   0.045       0
  5634.4    0.07       0
Bank Sta=5179.6,5184.1
Exp/Cntr=0.3,0.1

Type RM Length L Ch R = 1,2894,1240,1240,1240
BEGIN DESCRIPTION:
Mapping XS 2971dd39
END DESCRIPTION:
XS GIS Cut Line= 4
      1436596.79      6958884.87      1435587.74      6957604.75
      1435284.02      6957277.81      1434790.31      6958288.08
#Sta/Elev= 30
  3370.0 1862.94  4095.0 1858.58  4152.7 1856.08  4366.0 1851.70  5141.2 1847.54
  5296.6 1848.52  5353.3 1846.72  5374.8 1847.80  5381.6 1846.38  5389.0 1847.62
  5410.0 1845.84  5417.3 1847.13  5438.3 1845.45  5481.8 1847.66  5513.2 1846.14
  5526.8 1847.76  5543.4 1847.21  5566.3 1846.37  5594.4 1848.78  5616.9 1846.76
  5639.4 1849.93  5678.9 1850.45  5692.8 1846.55  5878.2 1844.81  5878.6 1844.31
  5882.8 1844.81  6515.2 1847.43  6528.8 1847.48  6545.7 1851.54  6570.7 1853.67
#Mann=6,-1,0
  3370.0   0.035       0  5543.4    0.07       0  5692.8   0.045       0
  5878.2   0.035       0  5882.8   0.045       0  6515.2    0.07       0
Bank Sta=5878.2,5882.8
Exp/Cntr=0.3,0.1

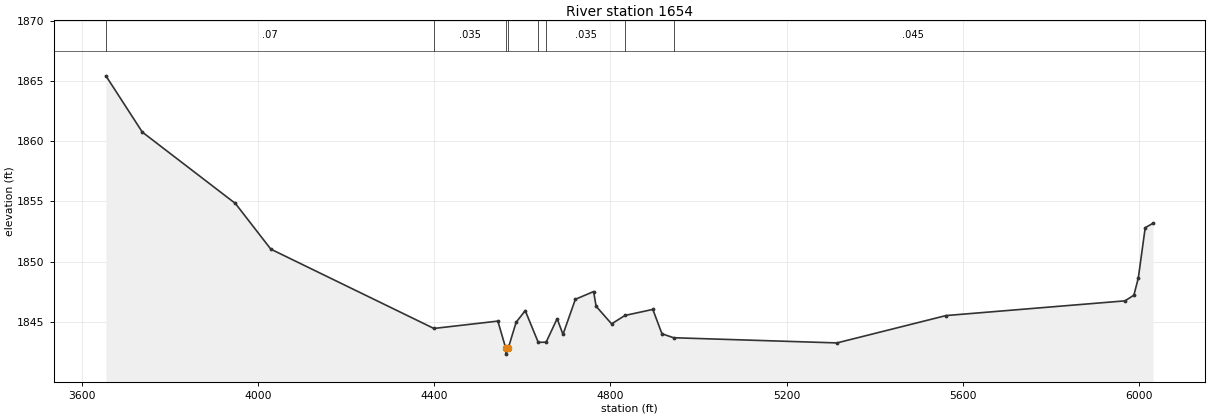
Type RM Length L Ch R = 1,1654,0,0,0
BEGIN DESCRIPTION:
Clear Fork Trib4_1 1.0
END DESCRIPTION:
XS GIS Cut Line= 3
      1435154.99      6955938.02      1434760.45      6957427.77
      1434617.01      6958250.86
#Sta/Elev= 30
  3654.8 1865.41  3737.5 1860.74  3948.7 1854.82  4029.1 1851.03  4399.2 1844.45
  4544.4 1845.06  4562.2 1842.82  4562.7 1842.32  4568.0 1842.82  4585.8 1844.96
  4606.5 1845.93  4636.0 1843.30  4653.9 1843.31  4678.9 1845.26  4692.2 1843.96
  4720.3 1846.87  4761.7 1847.51  4767.4 1846.29  4802.5 1844.83  4832.9 1845.53
  4896.1 1846.03  4916.8 1844.01  4943.2 1843.68  5314.0 1843.25  5561.6 1845.52
  5967.6 1846.74  5987.9 1847.21  5998.0 1848.65  6013.6 1852.81  6031.4 1853.18
#Mann=8,-1,0
  3654.8    0.07       0  4399.2   0.035       0  4562.2   0.045       0
  4568.0   0.035       0  4636.0    0.07       0  4653.9   0.035       0
  4832.9    0.07       0  4943.2   0.045       0
Bank Sta=4562.2,4568
Exp/Cntr=0.3,0.1

Chan Stop Cuts=-1