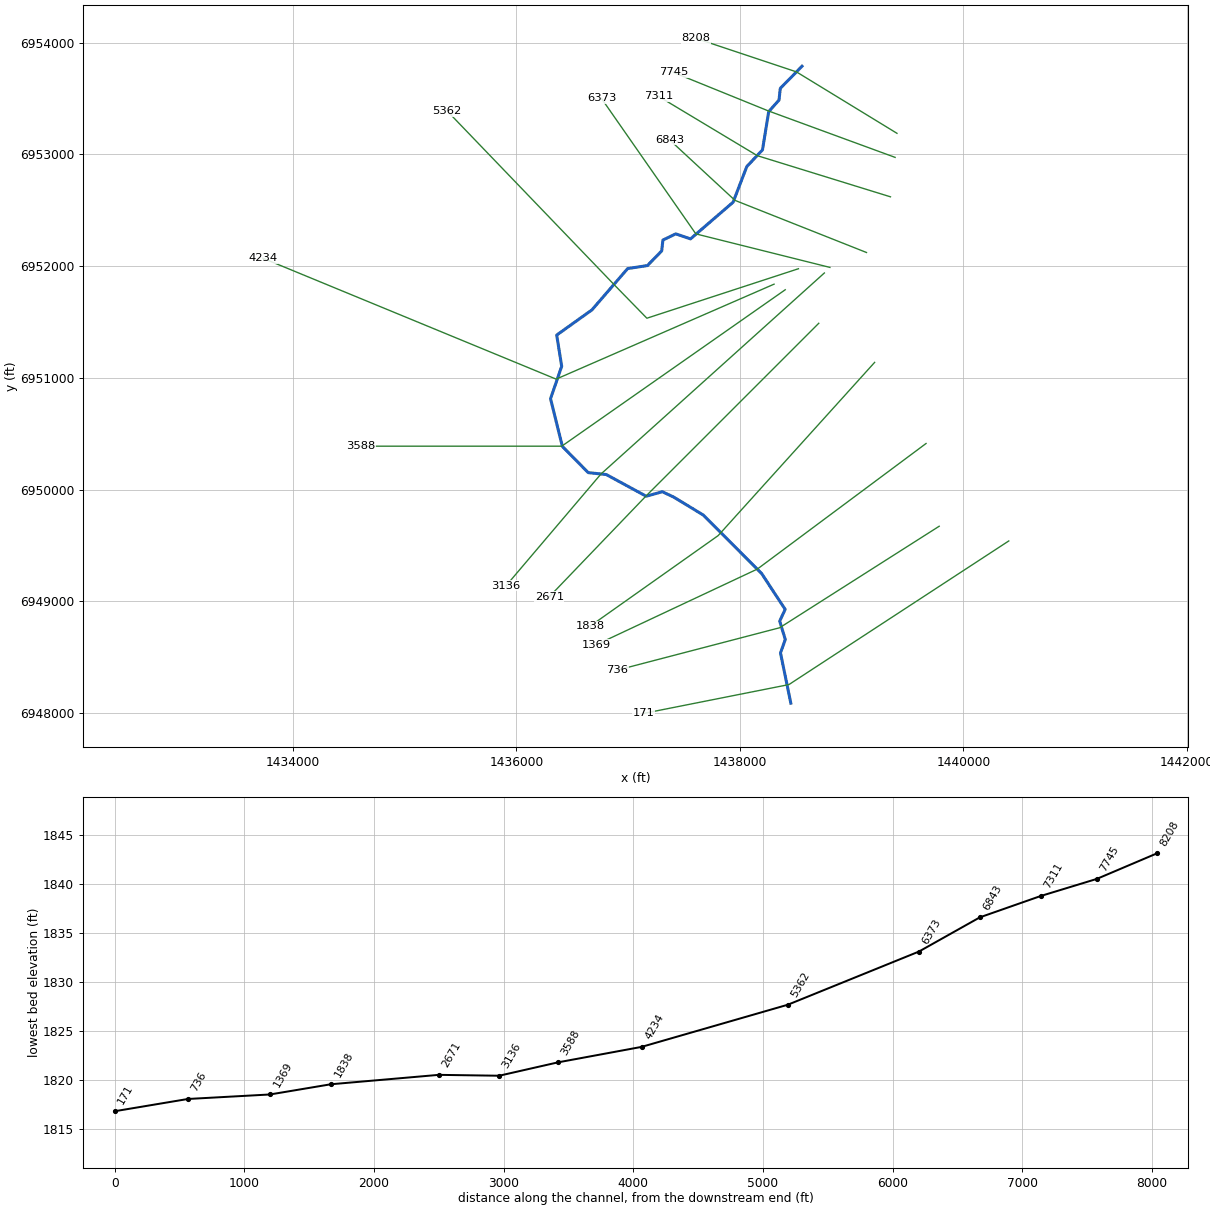
--- Clear Fork Trib5.prj (project) ---

Proj Title=Clear Fork Trib5 Base Level Engineering
Current Plan=p01
Default Exp/Contr=0.3,0.1
English Units
Geom File=g01
Flow File=f01
Plan File=p01
BEGIN DESCRIPTION:
Clear Fork Trib5
END DESCRIPTION:

--- Clear Fork Trib5.p01 (plan) ---

Plan Title=Multiple Run
Short Identifier=Multiple
Geom File=g01
Flow File=f01
Subcritical Flow
K Sum by GR= 0
Std Step Tol= 0.01
Critical Tol= 0.01
Num of Std Step Trials= 20
Max Error Tol= 0.3
Flow Tol Ratio= 0.001
Split Flow NTrial= 30
Split Flow Tol= 0.02
Split Flow Ratio= 0.02
Log Output Level= 0
Friction Slope Method= 1
Unsteady Friction Slope Method= 2
Unsteady Bridges Friction Slope Method= 1
Parabolic Critical Depth
Global Vel Dist=  1 , 1 , 1
Global Log Level= 0
CheckData=True
Encroach Param= -1, 0, 0, 0
BEGIN DESCRIPTION:
Multiple Run
END DESCRIPTION:

--- Clear Fork Trib5.f01 (steady flow) ---

Flow Title=Multiple
Number of Profiles=7
Profile Names=10-year,25-year,50-year,1pct_min,100-year,1pct_plu,500-year
River Rch & RM= Clear Fork Trib5,Reach-1,8208
     288     406     504     312     622    1241     957
River Rch & RM= Clear Fork Trib5,Reach-1,6373
     431     621     784     492     981    1958    1556
River Rch & RM= Clear Fork Trib5,Reach-1,1369
     452     654     827     519    1036    2067    1648
Boundary for River Rch & Prof#=Clear Fork Trib5,Reach-1,1
Up Type=0
Dn Type=3
Dn Slope=0.005
Boundary for River Rch & Prof#=Clear Fork Trib5,Reach-1,2
Up Type=0
Dn Type=3
Dn Slope=0.005
Boundary for River Rch & Prof#=Clear Fork Trib5,Reach-1,3
Up Type=0
Dn Type=3
Dn Slope=0.005
Boundary for River Rch & Prof#=Clear Fork Trib5,Reach-1,4
Up Type=0
Dn Type=3
Dn Slope=0.005
Boundary for River Rch & Prof#=Clear Fork Trib5,Reach-1,5
Up Type=0
Dn Type=3
Dn Slope=0.005
Boundary for River Rch & Prof#=Clear Fork Trib5,Reach-1,6
Up Type=0
Dn Type=3
Dn Slope=0.005
Boundary for River Rch & Prof#=Clear Fork Trib5,Reach-1,7
Up Type=0
Dn Type=3
Dn Slope=0.005

--- Clear Fork Trib5.g01 (geometry) ---

Geom Title=Existing Conditions

River Reach=Clear Fork Trib5,Reach-1
Reach XY= 30
      1438555.00      6953788.00      1438360.76      6953590.36
      1438349.46      6953485.58      1438257.07      6953382.14
      1438201.39      6953039.50      1438060.83      6952890.30
      1437938.36      6952571.32      1437557.30      6952243.09
      1437425.16      6952288.29      1437310.25      6952232.56
      1437299.45      6952135.63      1437171.77      6952004.43
      1436994.88      6951977.65      1436675.09      6951607.79
      1436359.77      6951382.39      1436404.48      6951103.22
      1436304.60      6950813.00      1436410.83      6950385.70
      1436641.68      6950151.37      1436803.44      6950134.24
      1437160.97      6949940.15      1437305.01      6949980.47
      1437407.28      6949932.18      1437672.05      6949771.51
      1438194.22      6949247.68      1438404.40      6948927.38
      1438355.40      6948822.73      1438405.58      6948658.04
      1438362.56      6948538.00      1438455.00      6948088.00

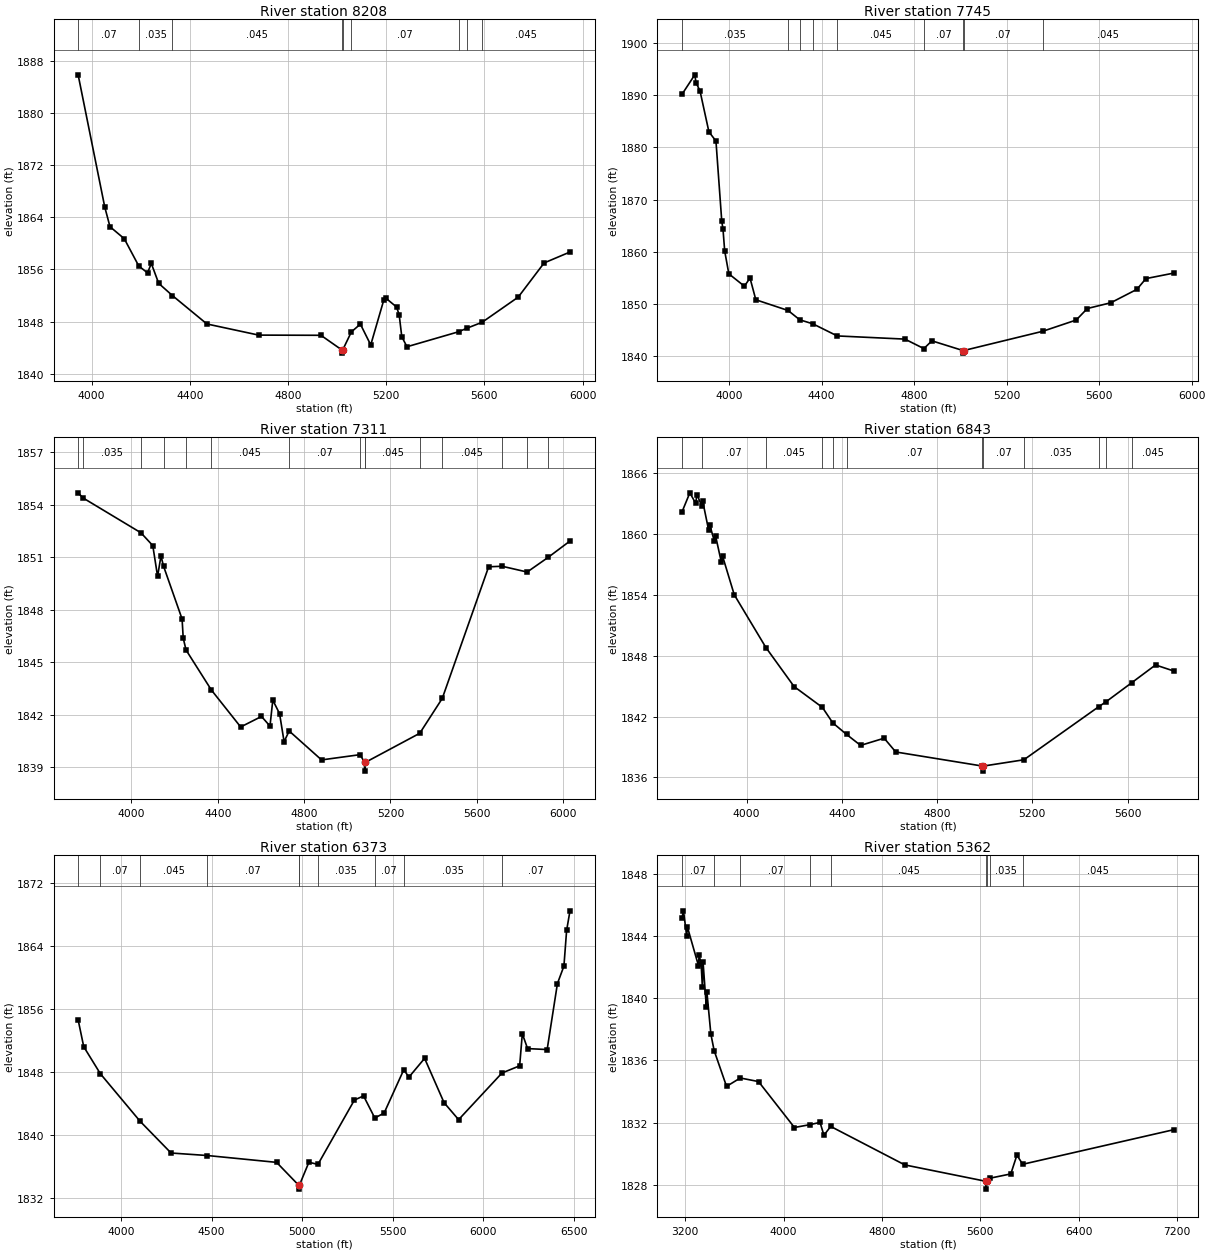
Type RM Length L Ch R = 1,8208,463,463,463
BEGIN DESCRIPTION:
Clear Fork Trib5 13.0
END DESCRIPTION:
XS GIS Cut Line= 3
      1439405.01      6953187.99      1438505.00      6953738.00
      1437605.04      6954037.99
#Sta/Elev= 30
  3945.5 1885.91  4053.9 1865.60  4075.2 1862.57  4133.3 1860.73  4192.4 1856.54
  4228.1 1855.47  4243.6 1856.92  4273.7 1853.86  4329.4 1851.99  4470.0 1847.62
  4680.9 1845.91  4934.5 1845.88  5019.3 1843.64  5019.6 1843.14  5023.3 1843.64
  5058.4 1846.40  5095.1 1847.60  5137.3 1844.40  5190.0 1851.24  5200.5 1851.54
  5242.7 1850.22  5253.2 1849.01  5263.8 1845.66  5284.9 1844.12  5494.9 1846.42
  5531.1 1847.00  5591.0 1847.88  5738.1 1851.75  5843.5 1857.00  5948.9 1858.68
#Mann=9,-1,0
  3945.5    0.07       0  4192.4   0.035       0  4329.4   0.045       0
  5019.3   0.045       0  5023.3   0.045       0  5058.4    0.07       0
  5494.9   0.045       0  5531.1    0.07       0  5591.0   0.045       0
Bank Sta=5019.3,5023.3
Exp/Cntr=0.3,0.1

Type RM Length L Ch R = 1,7745,434,434,434
BEGIN DESCRIPTION:
Clear Fork Trib5 12.0
END DESCRIPTION:
XS GIS Cut Line= 3
      1439388.33      6952972.63      1438255.00      6953388.00
      1437403.24      6953733.44
#Sta/Elev= 30
  3796.8 1890.19  3852.1 1893.94  3857.5 1892.46  3874.9 1890.82  3913.2 1883.01
  3943.7 1881.23  3968.8 1865.84  3974.2 1864.28  3981.4 1860.15  3999.3 1855.76
  4066.6 1853.38  4090.9 1854.95  4116.0 1850.78  4255.6 1848.72  4306.0 1846.93
  4362.2 1846.17  4468.0 1843.84  4760.5 1843.23  4842.5 1841.41  4877.2 1842.90
  5011.2 1841.04  5011.5 1840.54  5015.2 1841.04  5356.1 1844.73  5500.9 1846.89
  5549.1 1849.10  5650.8 1850.21  5763.4 1852.78  5802.4 1854.84  5923.0 1855.90
#Mann=9,-1,0
  3796.8   0.035       0  4255.6    0.07       0  4306.0   0.045       0
  4362.2    0.07       0  4468.0   0.045       0  4842.5    0.07       0
  5011.2    0.07       0  5015.2    0.07       0  5356.1   0.045       0
Bank Sta=5011.2,5015.2
Exp/Cntr=0.3,0.1

Type RM Length L Ch R = 1,7311,468,468,468
BEGIN DESCRIPTION:
Clear Fork Trib5 11.0
END DESCRIPTION:
XS GIS Cut Line= 3
      1439346.75      6952619.70      1438155.00      6952988.00
      1437270.62      6953519.36
#Sta/Elev= 30
  3752.9 1854.67  3775.3 1854.38  4043.9 1852.39  4098.8 1851.66  4121.1 1849.90
  4136.7 1851.07  4148.5 1850.49  4234.6 1847.47  4239.8 1846.38  4253.0 1845.70
  4370.2 1843.42  4506.1 1841.31  4602.5 1841.91  4641.9 1841.36  4654.9 1842.84
  4686.3 1842.07  4707.2 1840.47  4730.8 1841.08  4880.8 1839.43  5059.6 1839.73
  5079.9 1839.29  5080.1 1838.79  5083.9 1839.29  5335.9 1840.95  5440.2 1842.94
  5655.1 1850.45  5717.5 1850.48  5833.6 1850.15  5931.1 1850.99  6032.0 1851.92
#Mann=15,-1,0
  3752.9    0.07       0  3775.3   0.035       0  4043.9    0.07       0
  4148.5   0.035       0  4253.0    0.07       0  4370.2   0.045       0
  4730.8    0.07       0  5059.6   0.045       0  5079.9    0.07       0
  5083.9   0.045       0  5335.9    0.07       0  5440.2   0.045       0
  5717.5   0.035       0  5833.6   0.045       0  5931.1   0.035       0
Bank Sta=5079.9,5083.9
Exp/Cntr=0.3,0.1

Type RM Length L Ch R = 1,6843,470,470,470
BEGIN DESCRIPTION:
Clear Fork Trib5 10.0
END DESCRIPTION:
XS GIS Cut Line= 3
      1439132.23      6952121.42      1437955.00      6952588.00
      1437368.73      6953130.68
#Sta/Elev= 30
  3729.0 1862.20  3762.0 1864.09  3786.4 1863.06  3791.8 1863.91  3813.0 1862.76
  3816.1 1863.26  3840.4 1860.47  3845.8 1860.92  3864.7 1859.34  3870.1 1859.84
  3894.4 1857.23  3899.8 1857.81  3948.5 1854.03  4081.4 1848.82  4199.7 1844.97
  4318.6 1842.91  4362.3 1841.38  4420.2 1840.24  4479.0 1839.16  4577.9 1839.87
  4626.6 1838.51  4990.6 1837.12  4990.9 1836.62  4994.6 1837.12  5164.6 1837.74
  5478.3 1842.97  5510.9 1843.49  5618.2 1845.36  5717.4 1847.10  5794.2 1846.50
#Mann=12,-1,0
  3729.0   0.035       0  3813.0    0.07       0  4081.4   0.045       0
  4318.6    0.07       0  4362.3   0.045       0  4420.2    0.07       0
  4990.6    0.07       0  4994.6    0.07       0  5164.6   0.035       0
  5478.3    0.07       0  5510.9   0.035       0  5618.2   0.045       0
Bank Sta=4990.6,4994.6
Exp/Cntr=0.3,0.1

Type RM Length L Ch R = 1,6373,1011,1011,1011
BEGIN DESCRIPTION:
Clear Fork Trib5 9.0
END DESCRIPTION:
XS GIS Cut Line= 3
      1438804.97      6951988.01      1437605.00      6952288.00
      1436760.56      6953500.03
#Sta/Elev= 30
  3763.4 1854.65  3794.3 1851.23  3886.2 1847.79  4105.5 1841.75  4276.2 1837.72
  4476.8 1837.40  4858.6 1836.53  4980.2 1833.63  4980.5 1833.13  4984.3 1833.63
  5036.9 1836.55  5086.6 1836.27  5287.8 1844.45  5338.4 1844.98  5400.4 1842.17
  5451.9 1842.80  5560.2 1848.30  5588.9 1847.37  5675.3 1849.75  5782.6 1844.12
  5862.9 1841.96  6102.3 1847.89  6199.7 1848.80  6214.5 1852.88  6243.5 1850.99
  6351.5 1850.87  6408.2 1859.26  6444.0 1861.47  6458.9 1866.00  6477.5 1868.50
#Mann=10,-1,0
  3763.4   0.035       0  3886.2    0.07       0  4105.5   0.045       0
  4476.8    0.07       0  4980.2    0.07       0  4984.3    0.07       0
  5086.6   0.035       0  5400.4    0.07       0  5560.2   0.035       0
  6102.3    0.07       0
Bank Sta=4980.2,4984.3
Exp/Cntr=0.3,0.1

Type RM Length L Ch R = 1,5362,1128,1128,1128
BEGIN DESCRIPTION:
Mapping XS 61057836
END DESCRIPTION:
XS GIS Cut Line= 4
      1438523.21      6951976.07      1437166.82      6951533.17
      1436883.08      6951823.83      1435379.30      6953388.21
#Sta/Elev= 30
  3172.5 1845.18  3184.4 1845.64  3211.0 1844.03  3216.3 1844.61  3306.7 1842.11
  3311.9 1842.78  3328.4 1842.24  3338.6 1840.71  3343.8 1842.37  3370.5 1839.46
  3375.7 1840.38  3407.6 1837.70  3434.1 1836.64  3535.2 1834.33  3647.2 1834.87
  3795.5 1834.64  4087.8 1831.68  4217.7 1831.87  4296.2 1832.01  4327.8 1831.18
  4382.8 1831.75  4985.9 1829.27  5648.6 1828.21  5648.8 1827.71  5652.7 1828.21
  5676.1 1828.41  5848.7 1828.69  5898.4 1829.90  5945.4 1829.31  7175.5 1831.54
#Mann=9,-1,0
  3172.5    0.07       0  3434.1   0.045       0  3647.2    0.07       0
  4217.7   0.035       0  4382.8   0.045       0  5648.6   0.045       0
  5652.7   0.045       0  5676.1   0.035       0  5945.4   0.045       0
Bank Sta=5648.6,5652.7
Exp/Cntr=0.3,0.1

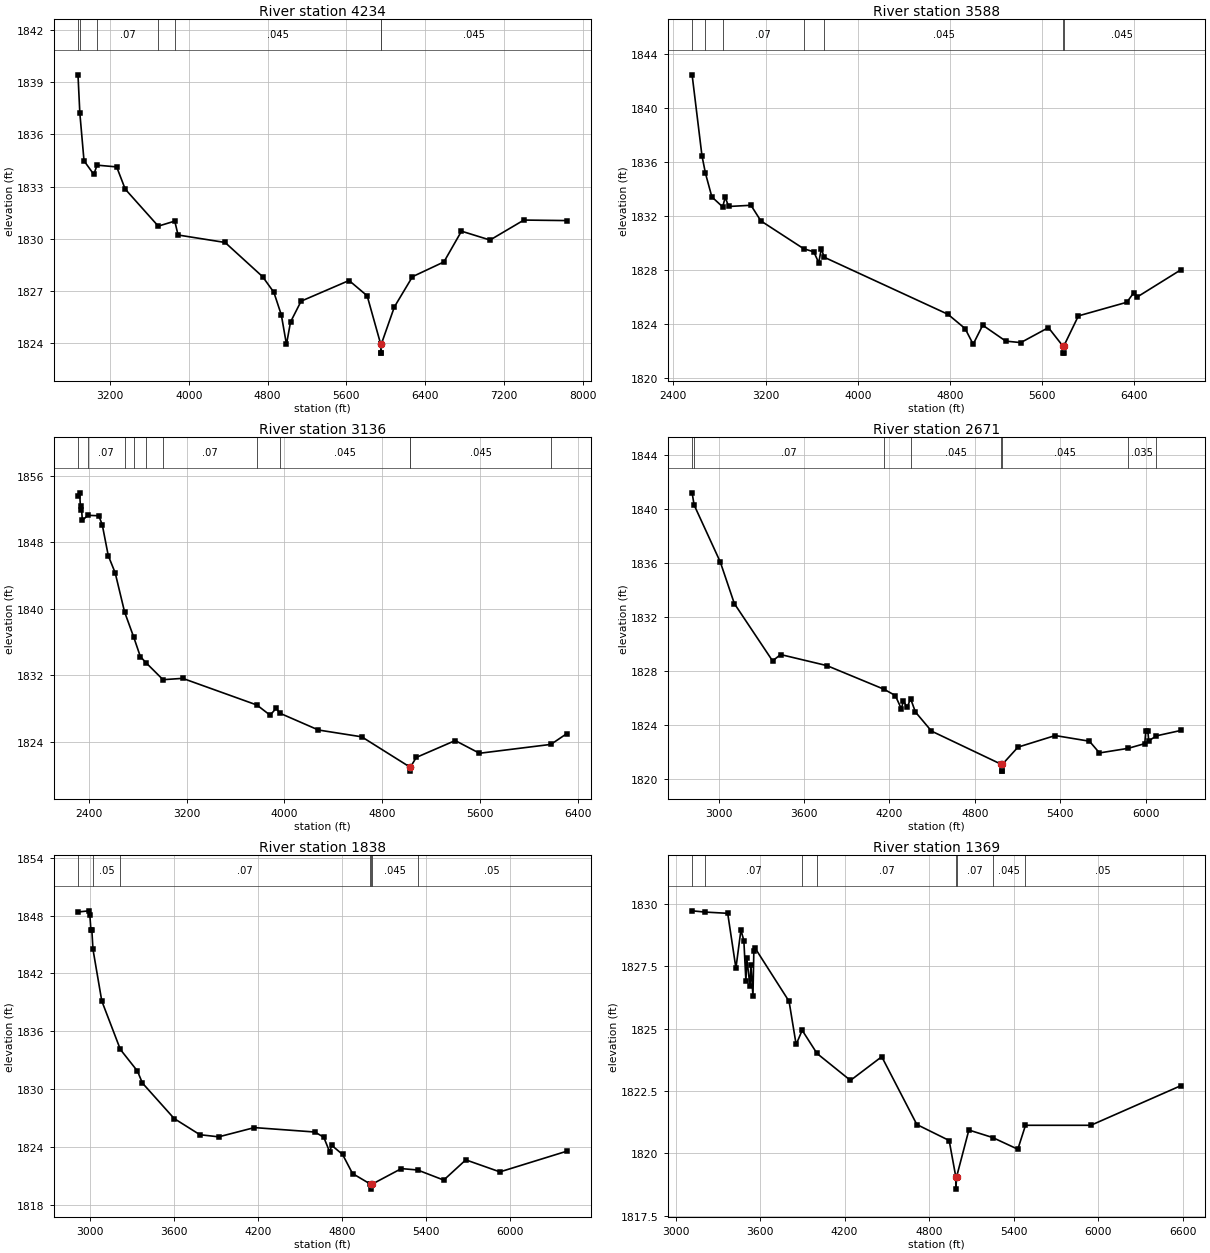
Type RM Length L Ch R = 1,4234,646,646,646
BEGIN DESCRIPTION:
Clear Fork Trib5 8.0
END DESCRIPTION:
XS GIS Cut Line= 3
      1438305.04      6951838.02      1436354.67      6950988.14
      1433729.09      6952070.71
#Sta/Elev= 30
  2872.5 1839.43  2891.4 1837.22  2933.8 1834.48  3033.0 1833.70  3066.6 1834.23
  3265.6 1834.13  3352.5 1832.85  3688.3 1830.72  3855.8 1831.01  3889.4 1830.21
  4367.2 1829.78  4748.7 1827.81  4863.0 1826.91  4938.7 1825.61  4991.0 1823.91
  5032.1 1825.20  5139.4 1826.40  5627.0 1827.59  5810.9 1826.71  5949.3 1823.91
  5949.6 1823.41  5953.4 1823.41  5953.7 1823.91  6087.5 1826.07  6271.3 1827.81
  6590.9 1828.66  6769.3 1830.43  7059.6 1829.92  7403.2 1831.07  7840.0 1831.04
#Mann=7,-1,0
  2872.5    0.07       0  2891.4   0.045       0  3066.6    0.07       0
  3688.3   0.035       0  3855.8   0.045       0  5949.3   0.045       0
  5953.7   0.045       0
Bank Sta=5949.3,5953.7
Exp/Cntr=0.3,0.1

Type RM Length L Ch R = 1,3588,452,452,452
BEGIN DESCRIPTION:
Clear Fork Trib5 7.0
END DESCRIPTION:
XS GIS Cut Line= 3
      1438405.03      6951788.02      1436405.00      6950388.00
      1434605.05      6950388.00
#Sta/Elev= 30
  2563.1 1842.46  2648.6 1836.46  2679.2 1835.15  2734.5 1833.41  2828.3 1832.67
  2850.4 1833.38  2880.1 1832.70  3073.6 1832.79  3159.9 1831.63  3530.9 1829.57
  3618.6 1829.34  3661.7 1828.53  3684.0 1829.57  3708.9 1828.94  4782.5 1824.71
  4931.6 1823.65  5001.4 1822.49  5084.4 1823.90  5284.4 1822.72  5414.4 1822.61
  5654.4 1823.72  5782.2 1822.33  5782.5 1821.83  5786.3 1821.83  5786.6 1822.33
  5914.4 1824.59  6334.4 1825.60  6394.4 1826.30  6424.4 1825.99  6804.4 1828.01
#Mann=7,-1,0
  2563.1    0.07       0  2679.2   0.045       0  2828.3    0.07       0
  3530.9   0.035       0  3708.9   0.045       0  5782.2   0.045       0
  5786.6   0.045       0
Bank Sta=5782.2,5786.6
Exp/Cntr=0.3,0.1

Type RM Length L Ch R = 1,3136,465,465,465
BEGIN DESCRIPTION:
Clear Fork Trib5 6.0
END DESCRIPTION:
XS GIS Cut Line= 3
      1438755.03      6951938.03      1436755.00      6950138.00
      1435906.38      6949138.94
#Sta/Elev= 30
  2309.7 1853.56  2323.6 1853.98  2331.0 1851.87  2337.8 1852.35  2345.2 1850.67
  2391.3 1851.27  2479.8 1851.22  2508.2 1850.15  2557.5 1846.42  2614.3 1844.34
  2691.0 1839.64  2766.3 1836.59  2819.9 1834.27  2866.0 1833.53  3005.8 1831.48
  3166.7 1831.64  3774.3 1828.43  3882.0 1827.21  3931.3 1828.02  3963.1 1827.44
  4278.1 1825.42  4632.4 1824.60  5025.6 1820.97  5026.0 1820.47  5031.4 1820.97
  5079.0 1822.12  5397.5 1824.15  5596.3 1822.62  6180.8 1823.69  6311.3 1824.99
#Mann=11,-1,0
  2309.7   0.035       0  2391.3    0.07       0  2691.0   0.035       0
  2766.3    0.07       0  2866.0   0.045       0  3005.8    0.07       0
  3774.3   0.035       0  3963.1   0.045       0  5025.6   0.045       0
  5031.4   0.045       0  6180.8   0.035       0
Bank Sta=5025.6,5031.4
Exp/Cntr=0.3,0.1

Type RM Length L Ch R = 1,2671,833,833,833
BEGIN DESCRIPTION:
Clear Fork Trib5 5.0
END DESCRIPTION:
XS GIS Cut Line= 3
      1438705.00      6951488.00      1437155.00      6949938.00
      1436293.06      6949039.94
#Sta/Elev= 30
  2812.4 1841.21  2826.4 1840.31  3010.4 1836.08  3109.4 1832.99  3378.1 1828.74
  3434.7 1829.21  3759.9 1828.39  4162.7 1826.63  4240.8 1826.17  4283.2 1825.19
  4297.3 1825.73  4325.6 1825.32  4348.2 1825.94  4382.2 1824.95  4495.3 1823.53
  4987.3 1821.06  4987.8 1820.56  4992.7 1820.56  4993.2 1821.06  5103.3 1822.34
  5365.0 1823.20  5605.6 1822.78  5676.3 1821.91  5877.5 1822.25  5994.6 1822.60
  6001.8 1823.54  6015.9 1823.56  6022.9 1822.81  6077.1 1823.18  6249.2 1823.58
#Mann=8,-1,0
  2812.4   0.035       0  2826.4    0.07       0  4162.7   0.035       0
  4348.2   0.045       0  4987.3   0.045       0  4993.2   0.045       0
  5877.5   0.035       0  6077.1    0.05       0
Bank Sta=4987.3,4993.2
Exp/Cntr=0.3,0.1

Type RM Length L Ch R = 1,1838,469,469,469
BEGIN DESCRIPTION:
Clear Fork Trib5 4.0
END DESCRIPTION:
XS GIS Cut Line= 3
      1439205.00      6951138.01      1437805.00      6949588.00
      1436658.87      6948777.36
#Sta/Elev= 30
  2911.3 1848.38  2989.4 1848.50  2996.1 1848.05  3003.6 1846.52  3010.3 1846.50
  3018.4 1844.50  3081.3 1839.14  3213.8 1834.11  3336.1 1831.86  3371.3 1830.62
  3598.4 1826.93  3782.3 1825.25  3916.8 1825.03  4171.6 1825.99  4603.5 1825.53
  4667.1 1824.99  4709.6 1823.46  4723.8 1824.15  4801.6 1823.20  4872.6 1821.22
  4999.4 1820.13  5004.3 1820.10  5004.8 1819.60  5010.4 1820.10  5221.5 1821.73
  5336.9 1821.59  5524.3 1820.54  5681.9 1822.64  5925.6 1821.39  6403.8 1823.54
#Mann=7,-1,0
  2911.3   0.035       0  3018.4    0.05       0  3213.8    0.07       0
  4999.4   0.045       0  5004.3   0.045       0  5010.4   0.045       0
  5336.9    0.05       0
Bank Sta=5004.3,5010.4
Exp/Cntr=0.3,0.1

Type RM Length L Ch R = 1,1369,633,633,633
BEGIN DESCRIPTION:
Clear Fork Trib5 3.0
END DESCRIPTION:
XS GIS Cut Line= 3
      1439665.12      6950412.03      1438155.00      6949288.00
      1436716.99      6948612.71
#Sta/Elev= 30
  3117.7 1829.72  3210.1 1829.67  3370.4 1829.62  3428.8 1827.42  3464.2 1828.95
  3485.1 1828.53  3499.7 1826.90  3505.9 1827.81  3528.9 1826.70  3535.1 1827.55
  3549.7 1826.30  3556.0 1828.10  3564.3 1828.23  3806.2 1826.09  3856.3 1824.36
  3899.3 1824.93  4004.6 1824.00  4242.1 1822.92  4464.2 1823.87  4713.5 1821.15
  4942.9 1820.51  4989.9 1819.06  4990.4 1818.56  4996.0 1819.06  5082.8 1820.93
  5251.2 1820.63  5430.5 1820.16  5484.9 1821.12  5948.9 1821.12  6588.9 1822.71
#Mann=8,-1,0
  3117.7    0.05       0  3210.1    0.07       0  3899.3   0.035       0
  4004.6    0.07       0  4989.9    0.07       0  4996.0    0.07       0
  5251.2   0.045       0  5484.9    0.05       0
Bank Sta=4989.9,4996
Exp/Cntr=0.3,0.1

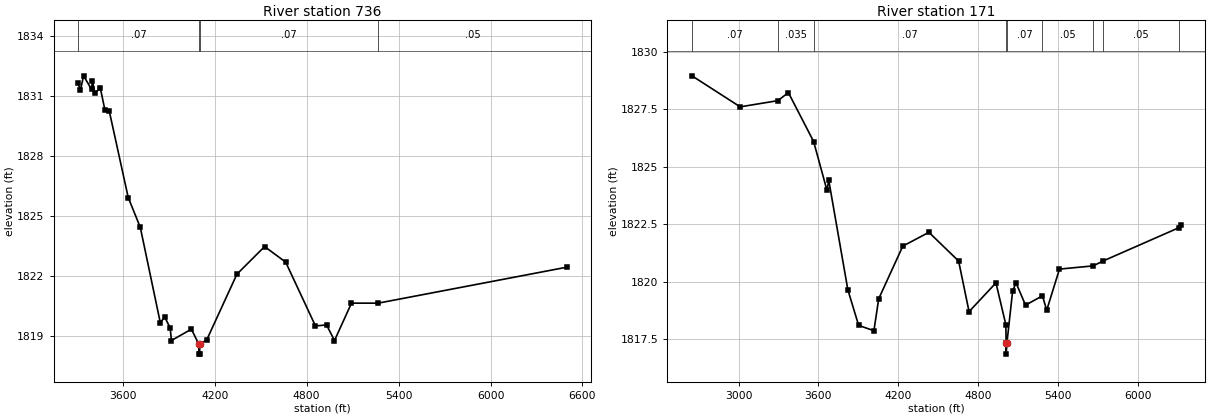
Type RM Length L Ch R = 1,736,565,565,565
BEGIN DESCRIPTION:
Clear Fork Trib5 2.0
END DESCRIPTION:
XS GIS Cut Line= 3
      1439782.80      6949671.56      1438354.60      6948763.00
      1436903.81      6948384.32
#Sta/Elev= 30
  3307.3 1831.65  3322.9 1831.30  3344.0 1832.02  3395.7 1831.34  3401.6 1831.78
  3416.8 1831.15  3453.2 1831.40  3482.5 1830.33  3510.8 1830.28  3635.3 1825.93
  3714.0 1824.44  3844.4 1819.68  3873.6 1819.95  3909.1 1819.41  3917.2 1818.78
  4047.6 1819.35  4095.6 1818.60  4096.1 1818.10  4101.5 1818.10  4102.0 1818.60
  4147.5 1818.81  4344.8 1822.10  4525.4 1823.48  4663.2 1822.70  4857.3 1819.51
  4929.9 1819.56  4981.6 1818.78  5092.6 1820.65  5266.8 1820.65  6499.4 1822.45
#Mann=4,-1,0
  3307.3    0.07       0  4095.6    0.07       0  4102.0    0.07       0
  5266.8    0.05       0
Bank Sta=4095.6,4102
Exp/Cntr=0.3,0.1

Type RM Length L Ch R = 1,171,0,0,0
BEGIN DESCRIPTION:
Clear Fork Trib5 1.0
END DESCRIPTION:
XS GIS Cut Line= 3
      1440405.60      6949540.03      1438438.10      6948254.57
      1437139.53      6947996.85
#Sta/Elev= 30
  2649.8 1828.96  3012.4 1827.61  3295.2 1827.88  3374.4 1828.23  3564.1 1826.10
  3664.0 1823.98  3677.8 1824.41  3821.1 1819.65  3902.3 1818.10  4016.9 1817.87
  4053.1 1819.26  4234.1 1821.55  4430.2 1822.15  4653.4 1820.90  4731.8 1818.70
  4933.9 1819.95  5008.2 1818.13  5010.2 1817.35  5010.7 1816.85  5016.6 1817.35
  5059.3 1819.60  5084.7 1819.95  5156.1 1818.98  5283.3 1819.39  5315.2 1818.76
  5411.0 1820.55  5664.2 1820.69  5737.7 1820.90  6312.0 1822.36  6323.9 1822.47
#Mann=9,-1,0
  2649.8    0.07       0  3295.2   0.035       0  3564.1    0.07       0
  5010.2    0.07       0  5016.6    0.07       0  5283.3    0.05       0
  5664.2   0.045       0  5737.7    0.05       0  6312.0   0.045       0
Bank Sta=5010.2,5016.6
Exp/Cntr=0.3,0.1

Chan Stop Cuts=-1