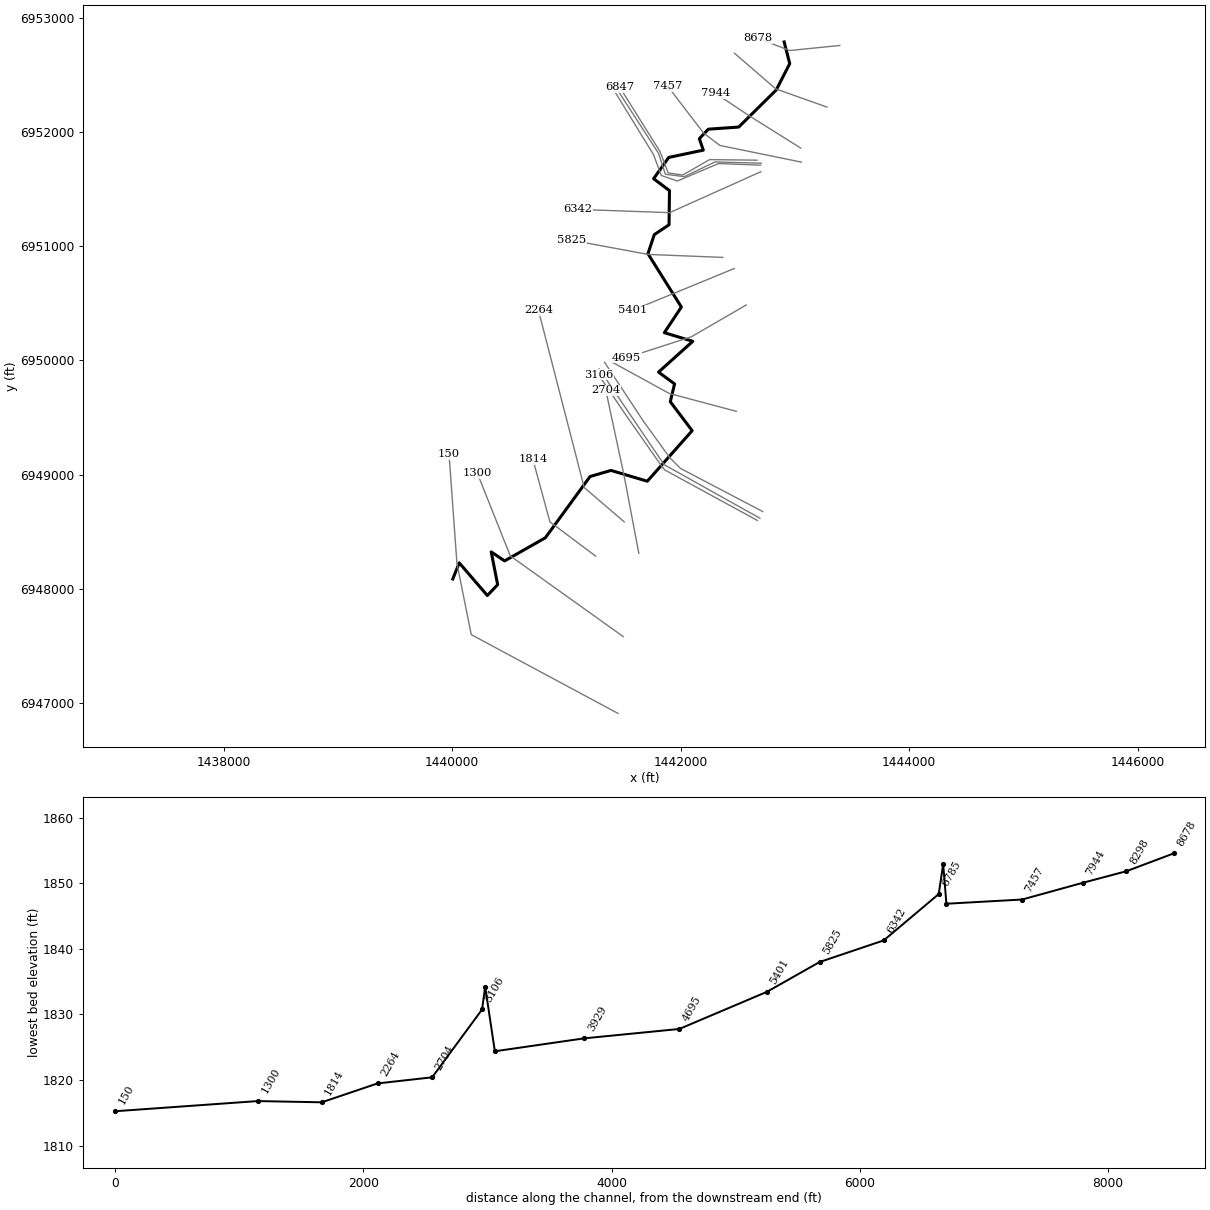
--- Clear Fork Trib6.prj (project) ---

Proj Title=Clear Fork Trib6 Base Level Engineering
Current Plan=p01
Default Exp/Contr=0.3,0.1
English Units
Geom File=g01
Flow File=f01
Plan File=p01
BEGIN DESCRIPTION:
Clear Fork Trib6
END DESCRIPTION:

--- Clear Fork Trib6.p01 (plan) ---

Plan Title=Multiple Run
Short Identifier=Multiple
Geom File=g01
Flow File=f01
Subcritical Flow
K Sum by GR= 0
Std Step Tol= 0.01
Critical Tol= 0.01
Num of Std Step Trials= 20
Max Error Tol= 0.3
Flow Tol Ratio= 0.001
Split Flow NTrial= 30
Split Flow Tol= 0.02
Split Flow Ratio= 0.02
Log Output Level= 0
Friction Slope Method= 1
Unsteady Friction Slope Method= 2
Unsteady Bridges Friction Slope Method= 1
Parabolic Critical Depth
Global Vel Dist=  1 , 1 , 1
Global Log Level= 0
CheckData=True
Encroach Param= -1, 0, 0, 0
BEGIN DESCRIPTION:
Multiple Run
END DESCRIPTION:

--- Clear Fork Trib6.f01 (steady flow) ---

Flow Title=Multiple
Number of Profiles=7
Profile Names=10-year,25-year,50-year,1pct_min,100-year,1pct_plu,500-year
River Rch & RM= Clear Fork Trib6,Reach-1,8678
     247     343     423     259     517    1032     782
River Rch & RM= Clear Fork Trib6,Reach-1,7944
     375     533     666     413     824    1645    1280
Boundary for River Rch & Prof#=Clear Fork Trib6,Reach-1,1
Up Type=0
Dn Type=3
Dn Slope=0.005
Boundary for River Rch & Prof#=Clear Fork Trib6,Reach-1,2
Up Type=0
Dn Type=3
Dn Slope=0.005
Boundary for River Rch & Prof#=Clear Fork Trib6,Reach-1,3
Up Type=0
Dn Type=3
Dn Slope=0.005
Boundary for River Rch & Prof#=Clear Fork Trib6,Reach-1,4
Up Type=0
Dn Type=3
Dn Slope=0.005
Boundary for River Rch & Prof#=Clear Fork Trib6,Reach-1,5
Up Type=0
Dn Type=3
Dn Slope=0.005
Boundary for River Rch & Prof#=Clear Fork Trib6,Reach-1,6
Up Type=0
Dn Type=3
Dn Slope=0.005
Boundary for River Rch & Prof#=Clear Fork Trib6,Reach-1,7
Up Type=0
Dn Type=3
Dn Slope=0.005

--- Clear Fork Trib6.g01 (geometry) ---

Geom Title=Existing Conditions

River Reach=Clear Fork Trib6,Reach-1
Reach XY= 30
      1442905.00      6952788.00      1442953.96      6952598.44
      1442835.53      6952367.46      1442507.29      6952043.11
      1442241.64      6952024.60      1442162.82      6951941.40
      1442197.43      6951841.07      1441895.00      6951777.37
      1441762.53      6951591.15      1441901.55      6951486.75
      1441897.54      6951187.78      1441768.51      6951101.68
      1441712.89      6950934.78      1442005.47      6950467.84
      1441856.57      6950243.65      1442105.55      6950167.89
      1441805.49      6949898.49      1441945.98      6949795.02
      1441908.46      6949639.50      1442099.94      6949385.71
      1441707.43      6948943.40      1441389.61      6949037.91
      1441206.28      6948984.48      1440815.16      6948448.36
      1440458.23      6948245.85      1440341.17      6948324.73
      1440397.69      6948037.89      1440307.29      6947943.05
      1440061.38      6948228.85      1440005.00      6948088.00

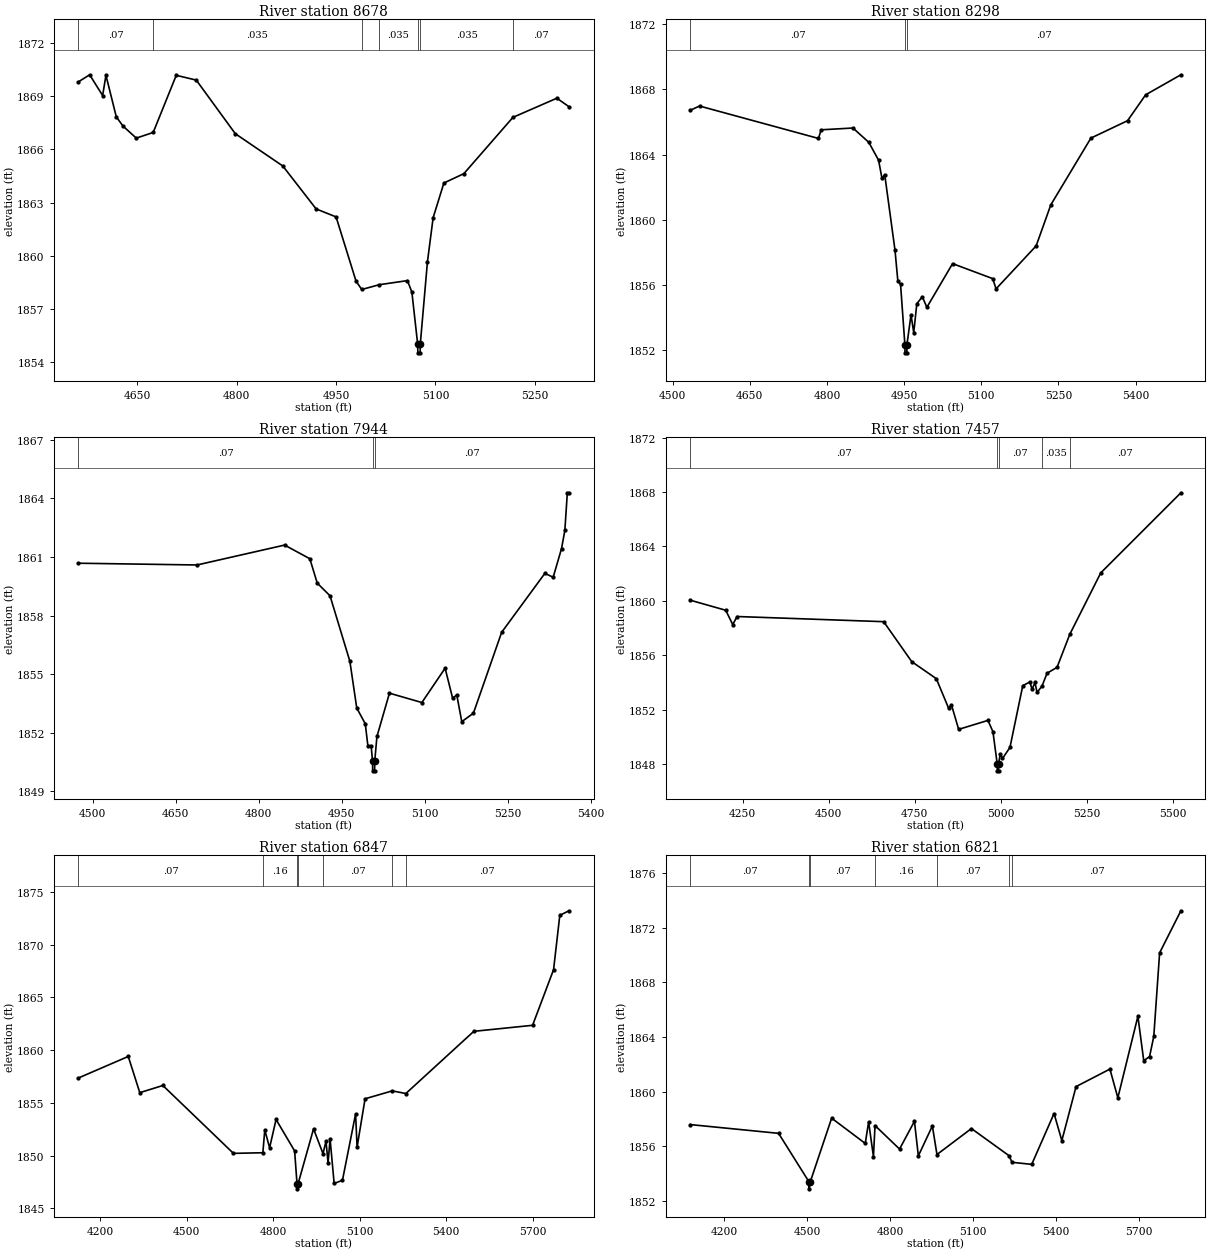
Type RM Length L Ch R = 1,8678,380,380,380
BEGIN DESCRIPTION:
Clear Fork Trib6 16.0
END DESCRIPTION:
XS GIS Cut Line= 3
      1443391.96      6952757.12      1442955.27      6952713.09
      1442673.22      6952819.62
#Sta/Elev= 30
  4561.1 1869.80  4578.1 1870.20  4597.7 1869.03  4602.7 1870.17  4618.3 1867.83
  4628.4 1867.31  4648.5 1866.63  4674.0 1866.95  4708.8 1870.17  4739.0 1869.90
  4797.9 1866.88  4869.6 1865.06  4919.9 1862.64  4950.0 1862.19  4980.2 1858.56
  4988.8 1858.10  5015.2 1858.37  5057.7 1858.60  5064.4 1857.95  5073.1 1855.03
  5073.4 1854.53  5076.9 1854.53  5077.1 1855.03  5087.9 1859.67  5096.5 1862.15
  5112.7 1864.10  5142.9 1864.63  5216.9 1867.80  5283.2 1868.88  5301.5 1868.40
#Mann=7,-1,0
  4561.1    0.07       0  4674.0   0.035       0  4988.8    0.07       0
  5015.2   0.035       0  5073.1    0.07       0  5077.1   0.035       0
  5216.9    0.07       0
Bank Sta=5073.1,5077.1
Exp/Cntr=0.3,0.1

Type RM Length L Ch R = 1,8298,354,354,354
BEGIN DESCRIPTION:
Mapping XS 3b5eedae
END DESCRIPTION:
XS GIS Cut Line= 3
      1443279.99      6952218.06      1442832.07      6952376.92
      1442470.06      6952689.44
#Sta/Elev= 30
  4534.4 1866.72  4552.4 1866.98  4783.5 1864.99  4788.8 1865.52  4850.5 1865.63
  4881.4 1864.75  4900.4 1863.65  4907.0 1862.53  4912.3 1862.77  4932.3 1858.12
  4937.8 1856.24  4943.1 1856.02  4951.5 1852.32  4951.7 1851.82  4955.2 1851.82
  4955.5 1852.32  4963.4 1854.16  4968.7 1853.06  4974.7 1854.84  4985.3 1855.26
  4994.3 1854.62  5044.2 1857.30  5122.1 1856.38  5128.7 1855.75  5206.6 1858.39
  5235.1 1860.91  5313.0 1865.01  5384.3 1866.08  5419.4 1867.67  5487.9 1868.90
#Mann=3,-1,0
  4534.4    0.07       0  4951.5    0.07       0  4955.5    0.07       0
Bank Sta=4951.5,4955.5
Exp/Cntr=0.3,0.1

Type RM Length L Ch R = 1,7944,487,487,487
BEGIN DESCRIPTION:
Clear Fork Trib6 15.0
END DESCRIPTION:
XS GIS Cut Line= 3
      1443050.85      6951858.67      1442605.00      6952138.00
      1442304.98      6952338.01
#Sta/Elev= 30
  4474.1 1860.68  4688.5 1860.59  4846.8 1861.61  4892.4 1860.91  4905.8 1859.66
  4928.9 1859.01  4964.8 1855.65  4977.2 1853.26  4992.6 1852.45  4997.3 1851.33
  5003.2 1851.33  5005.7 1850.54  5006.0 1850.04  5009.5 1850.04  5009.7 1850.54
  5013.7 1851.80  5036.3 1854.02  5094.9 1853.54  5136.9 1855.30  5150.5 1853.76
  5158.0 1853.93  5167.0 1852.56  5188.0 1852.99  5239.1 1857.14  5317.2 1860.16
  5332.2 1859.96  5347.3 1861.43  5353.3 1862.36  5357.8 1864.29  5360.8 1864.29
#Mann=3,-1,0
  4474.1    0.07       0  5005.7    0.07       0  5009.7    0.07       0
Bank Sta=5005.7,5009.7
Exp/Cntr=0.3,0.1

Type RM Length L Ch R = 1,7457,610,610,610
BEGIN DESCRIPTION:
Mapping XS 5e589c27
END DESCRIPTION:
XS GIS Cut Line= 4
      1443056.02      6951736.29      1442342.48      6951882.12
      1442199.25      6951991.50      1441884.13      6952402.99
#Sta/Elev= 30
  4097.5 1860.05  4200.6 1859.31  4221.0 1858.26  4233.6 1858.85  4659.9 1858.47
  4741.6 1855.53  4813.0 1854.28  4848.9 1852.10  4857.1 1852.35  4878.0 1850.55
  4963.2 1851.21  4977.7 1850.38  4990.2 1848.00  4990.5 1847.50  4994.0 1847.50
  4994.2 1848.00  4998.8 1848.74  5005.5 1848.41  5027.2 1849.22  5064.4 1853.76
  5085.2 1854.04  5091.5 1853.49  5099.8 1854.00  5106.1 1853.27  5120.4 1853.73
  5135.1 1854.68  5164.1 1855.11  5201.2 1857.54  5291.3 1862.06  5524.3 1867.95
#Mann=5,-1,0
  4097.5    0.07       0  4990.2    0.07       0  4994.2    0.07       0
  5120.4   0.035       0  5201.2    0.07       0
Bank Sta=4990.2,4994.2
Exp/Cntr=0.3,0.1

Type RM Length L Ch R = 1,6847,26,26,26
BEGIN DESCRIPTION:
Mapping XS c24e5217
END DESCRIPTION:
XS GIS Cut Line= 6
      1442667.99      6951753.13      1442253.07      6951758.34
      1442016.96      6951622.92      1441890.23      6951642.02
      1441819.05      6951827.78      1441465.12      6952393.37
#Sta/Elev= 30
  4124.9 1857.36  4297.9 1859.40  4337.9 1855.97  4417.9 1856.65  4662.7 1850.22
  4764.7 1850.28  4771.4 1852.44  4788.1 1850.75  4810.5 1853.43  4874.9 1850.45
  4883.1 1847.36  4883.3 1846.86  4887.1 1847.36  4940.5 1852.54  4973.3 1850.20
  4983.7 1851.37  4990.8 1849.32  4997.9 1851.57  5012.0 1847.37  5040.8 1847.67
  5086.4 1853.96  5091.5 1850.81  5119.2 1855.39  5213.5 1856.14  5260.7 1855.89
  5496.3 1861.78  5700.2 1862.35  5773.0 1867.62  5794.6 1872.77  5826.5 1873.20
#Mann=7,-1,0
  4124.9    0.07       0  4764.7    0.16       0  4883.1    0.07       0
  4887.1    0.16       0  4973.3    0.07       0  5213.5   0.035       0
  5260.7    0.07       0
Bank Sta=4883.1,4887.1
Exp/Cntr=0.3,0.1

Type RM Length L Ch R = 1,6821,36,36,36
BEGIN DESCRIPTION:
Mapping XS cb6bef7d
END DESCRIPTION:
XS GIS Cut Line= 6
      1442704.50      6951727.09      1442298.21      6951737.51
      1442032.59      6951609.03      1441865.92      6951629.87
      1441805.16      6951813.90      1441436.01      6952384.08
#Sta/Elev= 30
  4077.3 1857.60  4396.9 1856.96  4507.4 1853.40  4507.7 1852.90  4511.4 1853.40
  4589.0 1858.07  4710.7 1856.22  4722.8 1857.80  4740.3 1855.26  4746.0 1857.53
  4834.8 1855.81  4888.7 1857.84  4902.8 1855.31  4953.6 1857.50  4970.2 1855.41
  5094.9 1857.31  5230.7 1855.33  5242.2 1854.84  5313.2 1854.69  5394.0 1858.41
  5422.2 1856.43  5473.7 1860.38  5596.2 1861.66  5624.9 1859.56  5697.5 1865.52
  5718.7 1862.27  5739.8 1862.58  5755.0 1864.05  5776.1 1870.16  5853.1 1873.24
#Mann=7,-1,0
  4077.3    0.07       0  4507.4    0.07       0  4511.4    0.07       0
  4746.0    0.16       0  4970.2    0.07       0  5230.7   0.035       0
  5242.2    0.07       0
Bank Sta=4507.4,4511.4
Exp/Cntr=0.3,0.1

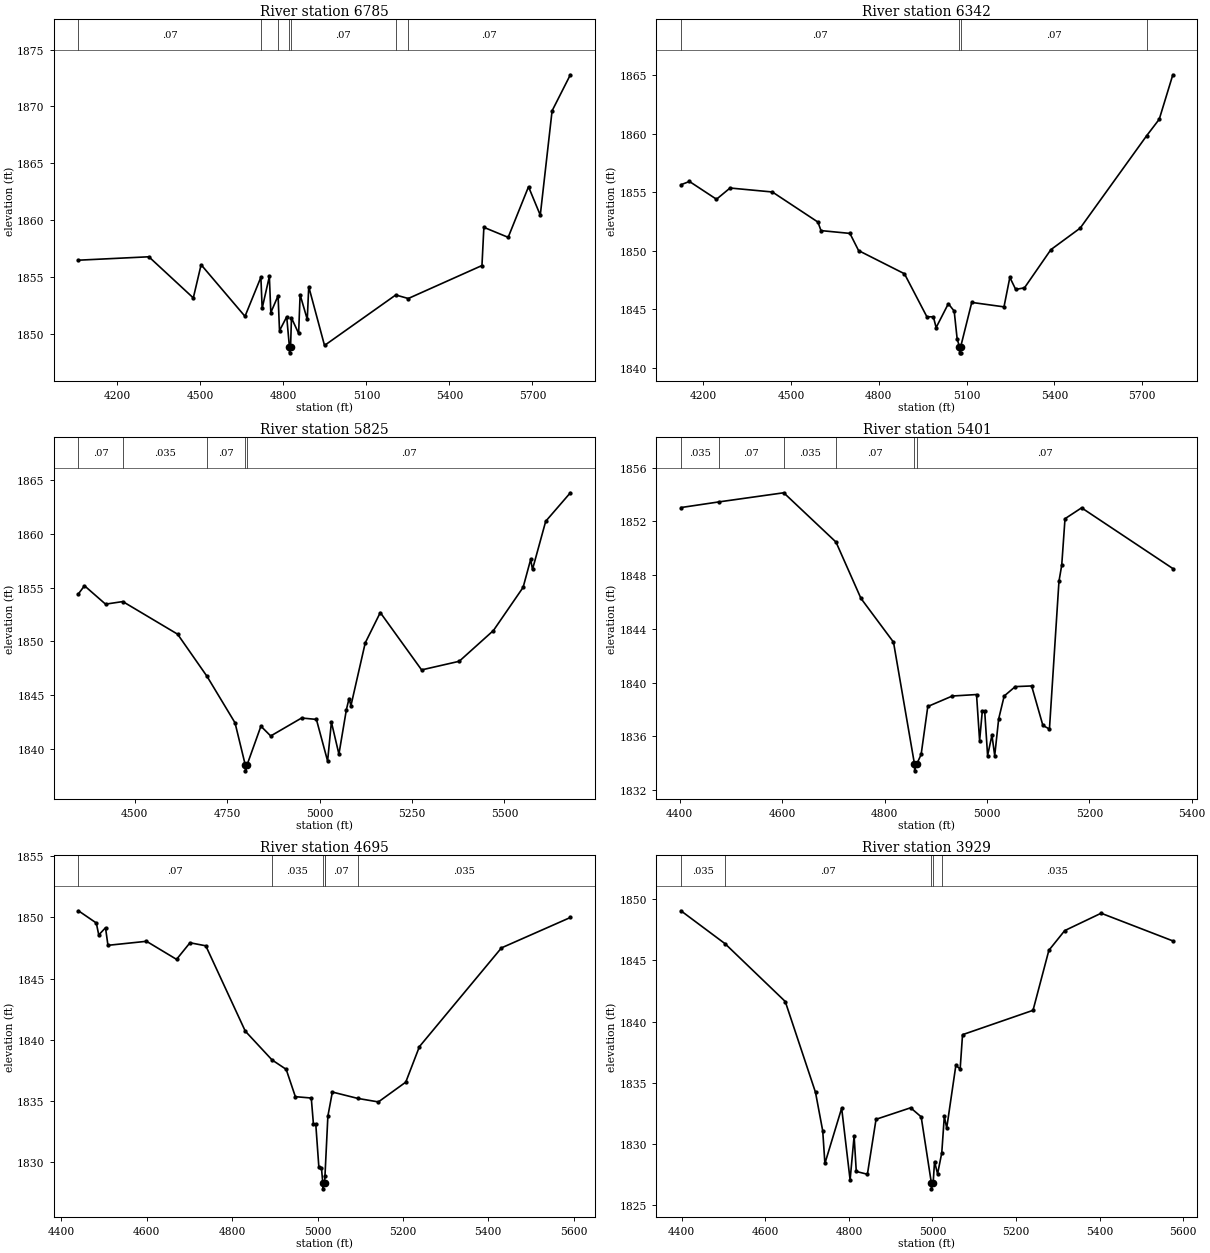
Type RM Length L Ch R = 1,6785,443,443,443
BEGIN DESCRIPTION:
Mapping XS 7cabcea7
END DESCRIPTION:
XS GIS Cut Line= 6
      1442699.27      6951709.73      1442331.20      6951723.62
      1441970.09      6951570.84      1441829.46      6951619.45
      1441761.75      6951801.74      1441422.29      6952354.24
#Sta/Elev= 30
  4059.4 1856.48  4313.8 1856.78  4474.4 1853.16  4502.6 1856.08  4661.2 1851.54
  4718.6 1854.98  4723.2 1852.25  4749.2 1855.05  4754.5 1851.87  4780.7 1853.35
  4785.9 1850.28  4811.9 1851.50  4821.8 1848.83  4822.1 1848.33  4825.8 1848.83
  4829.1 1851.40  4855.0 1850.04  4860.3 1853.44  4886.2 1851.27  4891.5 1854.15
  4948.5 1848.98  5205.9 1853.42  5251.1 1853.11  5517.4 1856.01  5524.3 1859.37
  5612.1 1858.49  5685.6 1862.94  5728.1 1860.44  5770.8 1869.62  5836.8 1872.79
#Mann=7,-1,0
  4059.4    0.07       0  4718.6    0.16       0  4780.7    0.07       0
  4821.8    0.07       0  4825.8    0.07       0  5205.9   0.035       0
  5251.1    0.07       0
Bank Sta=4821.8,4825.8
Exp/Cntr=0.3,0.1

Type RM Length L Ch R = 1,6342,517,517,517
BEGIN DESCRIPTION:
Clear Fork Trib6 11.0
END DESCRIPTION:
XS GIS Cut Line= 3
      1442701.58      6951652.44      1441902.55      6951293.85
      1441098.66      6951322.53
#Sta/Elev= 30
  4124.2 1855.64  4153.3 1855.92  4245.7 1854.40  4292.1 1855.36  4436.6 1855.02
  4592.1 1852.45  4602.7 1851.72  4701.4 1851.48  4731.1 1850.01  4887.7 1848.03
  4964.4 1844.35  4986.4 1844.35  4995.9 1843.43  5037.6 1845.47  5057.6 1844.84
  5067.6 1842.49  5075.6 1841.77  5075.9 1841.27  5079.4 1841.27  5079.6 1841.77
  5117.6 1845.58  5227.7 1845.20  5247.7 1847.72  5267.7 1846.69  5297.7 1846.83
  5387.8 1850.09  5487.9 1851.93  5715.0 1859.83  5758.0 1861.24  5804.4 1865.04
#Mann=4,-1,0
  4124.2    0.07       0  5075.6    0.07       0  5079.6    0.07       0
  5715.0   0.035       0
Bank Sta=5075.6,5079.6
Exp/Cntr=0.3,0.1

Type RM Length L Ch R = 1,5825,424,424,424
BEGIN DESCRIPTION:
Clear Fork Trib6 10.0
END DESCRIPTION:
XS GIS Cut Line= 3
      1442368.23      6950902.44      1441716.34      6950928.15
      1441049.37      6951051.64
#Sta/Elev= 30
  4347.6 1854.42  4363.9 1855.17  4420.9 1853.46  4467.6 1853.70  4615.8 1850.67
  4695.6 1846.74  4771.2 1842.43  4799.2 1838.47  4799.4 1837.97  4803.2 1838.47
  4841.2 1842.12  4867.7 1841.21  4951.3 1842.88  4991.3 1842.75  5021.6 1838.88
  5031.9 1842.50  5052.2 1839.52  5072.5 1843.67  5079.6 1844.69  5084.7 1844.02
  5123.4 1849.86  5164.1 1852.68  5275.9 1847.35  5377.6 1848.15  5470.2 1851.01
  5550.5 1855.02  5570.9 1857.61  5575.9 1856.69  5611.6 1861.16  5678.3 1863.81
#Mann=5,-1,0
  4347.6    0.07       0  4467.6   0.035       0  4695.6    0.07       0
  4799.2    0.07       0  4803.2    0.07       0
Bank Sta=4799.2,4803.2
Exp/Cntr=0.3,0.1

Type RM Length L Ch R = 1,5401,706,706,706
BEGIN DESCRIPTION:
Mapping XS 1429472a
END DESCRIPTION:
XS GIS Cut Line= 3
      1442468.96      6950805.23      1441920.32      6950579.52
      1441580.03      6950440.63
#Sta/Elev= 30
  4402.3 1853.03  4476.3 1853.45  4603.1 1854.13  4705.2 1850.46  4753.9 1846.27
  4817.5 1843.01  4858.5 1833.93  4858.8 1833.43  4862.9 1833.93  4871.5 1834.65
  4884.5 1838.22  4932.4 1839.00  4979.7 1839.11  4985.7 1835.67  4991.0 1837.89
  4995.6 1837.89  5001.3 1834.57  5009.8 1836.08  5015.2 1834.56  5022.9 1837.29
  5033.7 1839.00  5055.3 1839.70  5087.3 1839.75  5109.3 1836.81  5122.1 1836.54
  5140.7 1847.54  5146.1 1848.74  5152.5 1852.20  5184.9 1853.01  5363.1 1848.49
#Mann=6,-1,0
  4402.3   0.035       0  4476.3    0.07       0  4603.1   0.035       0
  4705.2    0.07       0  4858.5    0.07       0  4862.9    0.07       0
Bank Sta=4858.5,4862.9
Exp/Cntr=0.3,0.1

Type RM Length L Ch R = 1,4695,766,766,766
BEGIN DESCRIPTION:
Mapping XS 2e287a22
END DESCRIPTION:
XS GIS Cut Line= 3
      1442573.10      6950485.77      1442093.93      6950207.99
      1441524.49      6950023.97
#Sta/Elev= 30
  4440.0 1850.55  4481.8 1849.55  4487.6 1848.57  4503.4 1849.16  4509.1 1847.72
  4599.4 1848.05  4669.8 1846.57  4701.3 1847.93  4738.3 1847.68  4830.8 1840.69
  4893.5 1838.33  4926.6 1837.56  4948.1 1835.32  4985.4 1835.21  4990.4 1833.09
  4995.9 1833.09  5003.2 1829.53  5009.3 1829.47  5012.3 1828.27  5012.6 1827.77
  5016.7 1828.27  5017.5 1828.84  5024.3 1833.73  5034.8 1835.70  5094.1 1835.18
  5142.6 1834.89  5206.7 1836.51  5238.7 1839.42  5430.9 1847.51  5592.3 1850.00
#Mann=6,-1,0
  4440.0    0.07       0  4893.5   0.035       0  5012.3   0.035       0
  5016.7   0.035       0  5017.5    0.07       0  5094.1   0.035       0
Bank Sta=5012.3,5016.7
Exp/Cntr=0.3,0.1

Type RM Length L Ch R = 1,3929,720,720,720
BEGIN DESCRIPTION:
Mapping XS eb33c639
END DESCRIPTION:
XS GIS Cut Line= 3
      1442486.29      6949555.22      1441899.49      6949711.46
      1441399.70      6949985.65
#Sta/Elev= 30
  4398.0 1849.05  4503.7 1846.36  4647.7 1841.64  4720.1 1834.22  4737.4 1831.07
  4742.6 1828.41  4782.7 1832.93  4802.9 1827.07  4812.5 1830.64  4817.7 1827.76
  4844.3 1827.53  4865.0 1832.02  4947.8 1832.96  4973.0 1832.22  4997.3 1826.84
  4997.6 1826.34  5001.7 1826.84  5005.0 1828.56  5012.3 1827.56  5022.3 1829.28
  5028.4 1832.27  5034.1 1831.30  5056.0 1836.42  5066.3 1836.13  5072.0 1838.93
  5240.7 1840.92  5278.6 1845.82  5316.5 1847.43  5403.7 1848.85  5575.3 1846.59
#Mann=5,-1,0
  4398.0   0.035       0  4503.7    0.07       0  4997.3    0.07       0
  5001.7    0.07       0  5022.3   0.035       0
Bank Sta=4997.3,5001.7
Exp/Cntr=0.3,0.1

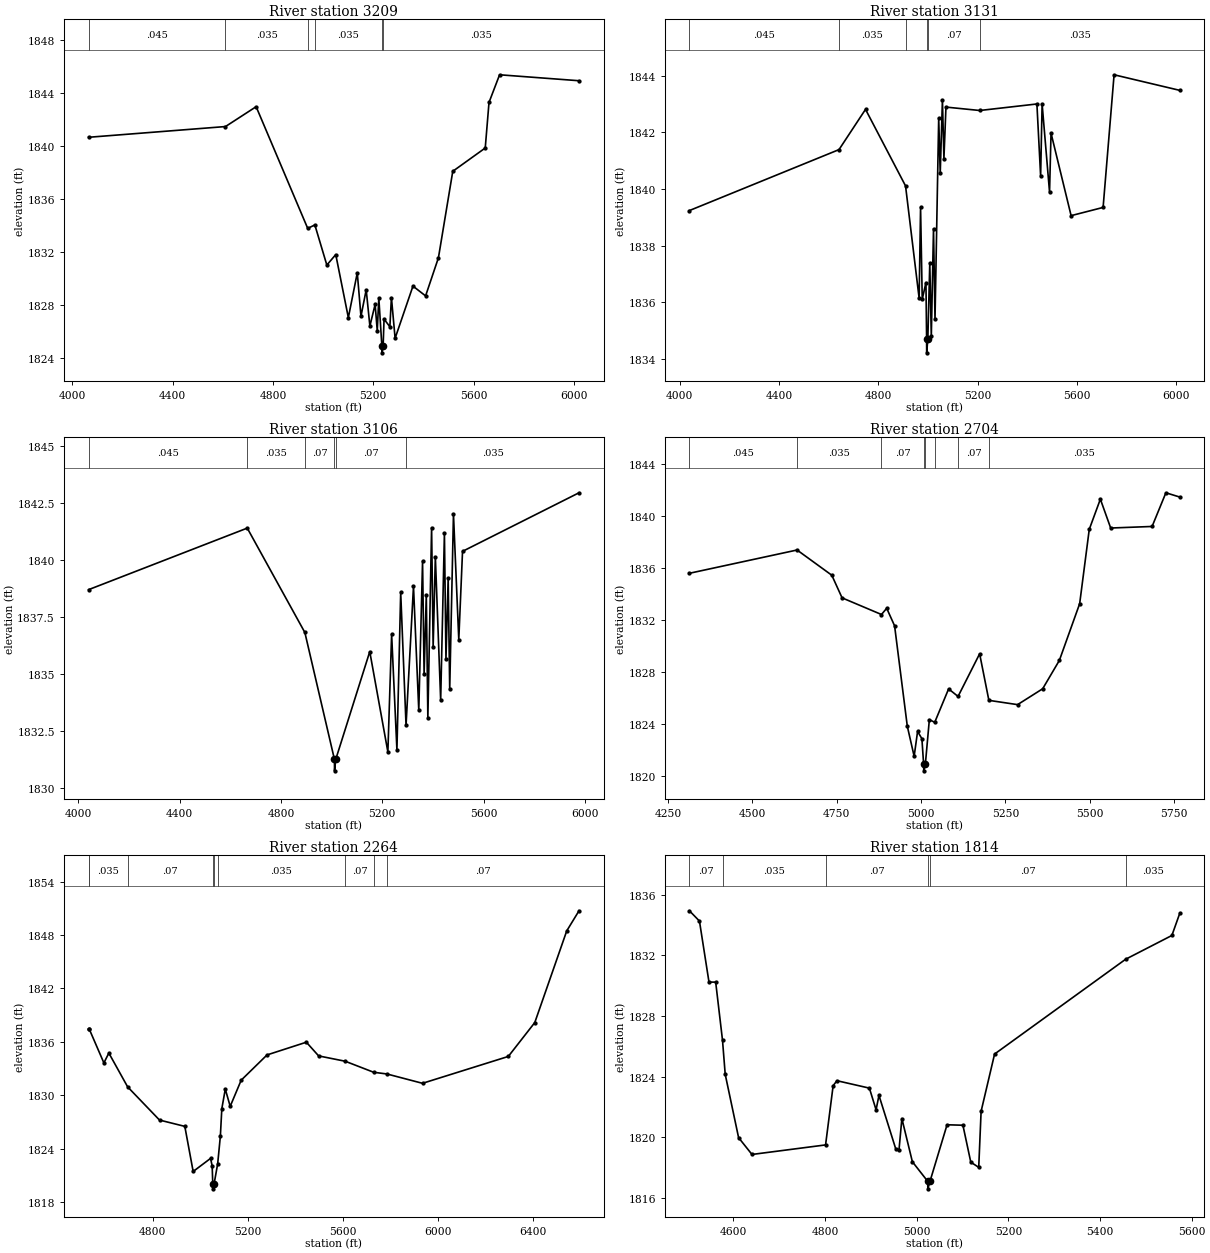
Type RM Length L Ch R = 1,3209,78,78,78
BEGIN DESCRIPTION:
Mapping XS 8ae254dd
END DESCRIPTION:
XS GIS Cut Line= 5
      1442716.59      6948678.37      1441998.13      6949055.26
      1441903.91      6949149.49      1441674.22      6949467.51
      1441333.56      6949984.38
#Sta/Elev= 30
  4064.6 1840.65  4610.5 1841.46  4732.7 1842.96  4938.4 1833.77  4966.9 1834.03
  5014.7 1831.00  5050.3 1831.79  5100.5 1827.03  5136.1 1830.41  5150.8 1827.13
  5171.7 1829.13  5186.4 1826.39  5207.3 1828.03  5215.8 1826.04  5222.0 1828.53
  5234.2 1824.87  5234.6 1824.37  5239.2 1824.87  5242.9 1826.92  5266.1 1826.34
  5272.3 1828.54  5287.0 1825.47  5358.2 1829.41  5408.6 1828.67  5459.8 1831.55
  5517.0 1838.08  5646.5 1839.84  5661.5 1843.28  5703.7 1845.37  6020.5 1844.92
#Mann=6,-1,0
  4064.6   0.045       0  4610.5   0.035       0  4938.4    0.07       0
  4966.9   0.035       0  5234.2   0.035       0  5239.2   0.035       0
Bank Sta=5234.2,5239.2
Exp/Cntr=0.3,0.1

Type RM Length L Ch R = 1,3131,25,25,25
BEGIN DESCRIPTION:
Clear Fork Trib6 6.0
END DESCRIPTION:
XS GIS Cut Line= 3
      1442693.06      6948619.46      1441855.00      6949088.00
      1441285.50      6949926.92
#Sta/Elev= 30
  4039.9 1839.24  4642.1 1841.39  4748.8 1842.81  4909.9 1840.11  4964.6 1836.15
  4970.4 1839.35  4977.1 1836.11  4992.1 1836.70  4994.7 1834.72  4995.0 1834.22
  4999.7 1834.72  5007.5 1837.39  5013.6 1834.80  5022.5 1838.60  5028.5 1835.40
  5043.4 1842.51  5049.5 1840.55  5058.4 1843.14  5064.4 1841.07  5072.6 1842.89
  5208.7 1842.77  5438.7 1843.00  5453.7 1840.46  5459.7 1843.00  5489.6 1839.89
  5495.6 1841.97  5576.4 1839.06  5705.2 1839.35  5749.4 1844.03  6014.0 1843.48
#Mann=6,-1,0
  4039.9   0.045       0  4642.1   0.035       0  4909.9    0.07       0
  4994.7    0.07       0  4999.7    0.07       0  5208.7   0.035       0
Bank Sta=4994.7,4999.7
Exp/Cntr=0.3,0.1

Type RM Length L Ch R = 1,3106,402,402,402
BEGIN DESCRIPTION:
Mapping XS 8a024f8b
END DESCRIPTION:
XS GIS Cut Line= 5
      1442670.31      6948600.36      1441861.29      6949041.33
      1441830.04      6949079.52      1441514.07      6949530.91
      1441281.99      6949873.83
#Sta/Elev= 30
  4041.0 1838.69  4667.2 1841.39  4894.6 1836.81  5011.4 1831.24  5011.7 1830.74
  5016.4 1831.24  5150.8 1835.97  5222.3 1831.57  5237.1 1836.73  5258.0 1831.66
  5272.9 1838.57  5294.0 1832.74  5323.4 1838.84  5344.3 1833.39  5359.2 1839.94
  5365.3 1834.98  5374.0 1838.47  5380.1 1833.06  5394.9 1841.41  5401.0 1836.17
  5409.7 1840.13  5430.7 1833.84  5445.5 1841.17  5451.6 1835.65  5460.3 1839.19
  5466.4 1834.31  5481.2 1842.01  5502.2 1836.50  5517.0 1840.37  5976.8 1842.94
#Mann=6,-1,0
  4041.0   0.045       0  4667.2   0.035       0  4894.6    0.07       0
  5011.4    0.07       0  5016.4    0.07       0  5294.0   0.035       0
Bank Sta=5011.4,5016.4
Exp/Cntr=0.3,0.1

Type RM Length L Ch R = 1,2704,440,440,440
BEGIN DESCRIPTION:
Clear Fork Trib6 5.0
END DESCRIPTION:
XS GIS Cut Line= 3
      1441632.99      6948313.24      1441505.00      6948988.00
      1441344.42      6949738.42
#Sta/Elev= 30
  4313.2 1835.59  4632.4 1837.38  4735.4 1835.44  4765.9 1833.70  4882.7 1832.42
  4898.2 1832.90  4921.6 1831.55  4959.3 1823.83  4979.6 1821.52  4989.8 1823.43
  5002.6 1822.87  5007.7 1820.90  5008.1 1820.40  5012.8 1820.90  5024.7 1824.34
  5040.6 1824.13  5081.8 1826.70  5109.8 1826.12  5173.8 1829.40  5201.2 1825.82
  5286.3 1825.49  5360.7 1826.71  5410.2 1828.89  5470.4 1833.25  5498.9 1838.97
  5531.8 1841.29  5562.4 1839.07  5685.2 1839.19  5726.1 1841.78  5767.4 1841.45
#Mann=8,-1,0
  4313.2   0.045       0  4632.4   0.035       0  4882.7    0.07       0
  5007.7    0.07       0  5012.8    0.07       0  5040.6   0.035       0
  5109.8    0.07       0  5201.2   0.035       0
Bank Sta=5007.7,5012.8
Exp/Cntr=0.3,0.1

Type RM Length L Ch R = 1,2264,450,450,450
BEGIN DESCRIPTION:
Clear Fork Trib6 4.0
END DESCRIPTION:
XS GIS Cut Line= 3
      1441504.98      6948588.02      1441155.00      6948888.00
      1440755.01      6950437.97
#Sta/Elev= 30
  4530.6 1837.44  4533.0 1837.44  4594.8 1833.62  4615.6 1834.73  4694.6 1830.93
  4828.6 1827.20  4935.0 1826.49  4970.1 1821.42  5043.2 1822.89  5050.0 1822.06
  5052.6 1819.97  5053.0 1819.47  5057.7 1819.97  5073.2 1822.29  5084.5 1825.41
  5090.6 1828.48  5105.2 1830.68  5125.8 1828.74  5172.0 1831.68  5280.7 1834.52
  5446.0 1835.95  5497.6 1834.41  5609.3 1833.81  5729.1 1832.57  5784.6 1832.38
  5934.3 1831.33  6295.1 1834.35  6406.4 1838.16  6540.7 1848.46  6592.3 1850.72
#Mann=9,-1,0
  4530.6   0.045       0  4533.0   0.035       0  4694.6    0.07       0
  5052.6    0.07       0  5057.7    0.07       0  5073.2   0.035       0
  5609.3    0.07       0  5729.1   0.035       0  5784.6    0.07       0
Bank Sta=5052.6,5057.7
Exp/Cntr=0.3,0.1

Type RM Length L Ch R = 1,1814,514,514,514
BEGIN DESCRIPTION:
Clear Fork Trib6 3.0
END DESCRIPTION:
XS GIS Cut Line= 3
      1441255.01      6948287.99      1440855.00      6948588.00
      1440705.00      6949138.00
#Sta/Elev= 30
  4504.1 1834.95  4526.0 1834.27  4546.8 1830.24  4561.4 1830.24  4576.3 1826.40
  4582.2 1824.15  4611.4 1819.97  4640.6 1818.86  4801.2 1819.49  4817.7 1823.40
  4826.0 1823.73  4896.8 1823.24  4911.4 1821.81  4917.7 1822.76  4954.1 1819.25
  4961.4 1819.15  4967.7 1821.23  4990.6 1818.38  5024.0 1817.09  5024.4 1816.59
  5029.1 1817.09  5066.3 1820.82  5100.9 1820.79  5118.1 1818.35  5135.4 1818.01
  5140.6 1821.71  5170.0 1825.49  5456.0 1831.75  5556.9 1833.32  5574.2 1834.79
#Mann=6,-1,0
  4504.1    0.07       0  4576.3   0.035       0  4801.2    0.07       0
  5024.0    0.07       0  5029.1    0.07       0  5456.0   0.035       0
Bank Sta=5024,5029.1
Exp/Cntr=0.3,0.1

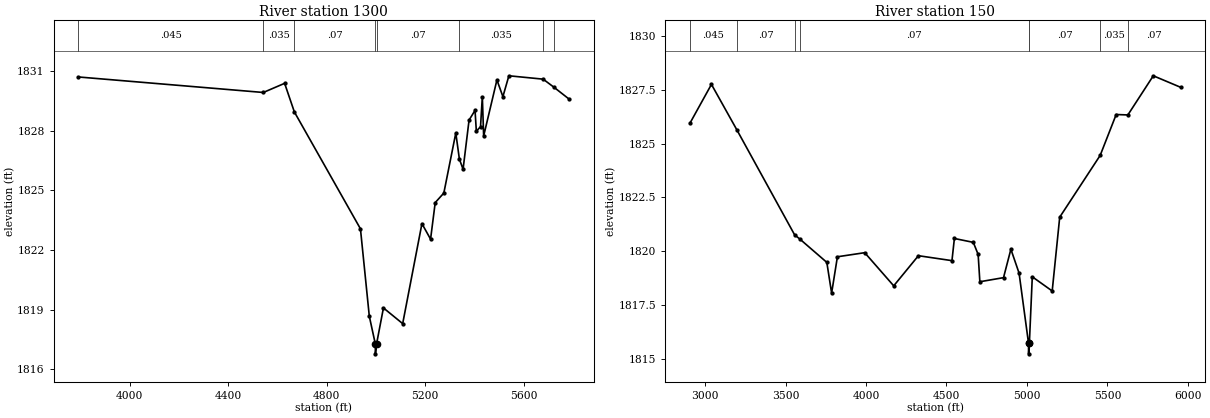
Type RM Length L Ch R = 1,1300,1150,1150,1150
BEGIN DESCRIPTION:
Mapping XS fba27955
END DESCRIPTION:
XS GIS Cut Line= 3
      1441497.53      6947582.95      1440508.15      6948289.66
      1440219.98      6949013.01
#Sta/Elev= 30
  3791.0 1830.71  4542.3 1829.93  4628.9 1830.39  4668.5 1828.95  4937.0 1823.07
  4973.0 1818.67  4997.4 1817.28  4997.8 1816.78  5002.5 1817.28  5030.4 1819.09
  5108.6 1818.30  5186.8 1823.33  5221.9 1822.55  5240.8 1824.39  5275.8 1824.87
  5324.4 1827.89  5339.1 1826.57  5354.0 1826.07  5378.3 1828.54  5402.6 1829.03
  5407.9 1827.98  5424.9 1828.21  5432.2 1829.71  5437.6 1827.74  5491.5 1830.56
  5515.8 1829.72  5540.1 1830.77  5679.3 1830.60  5722.5 1830.20  5785.5 1829.59
#Mann=8,-1,0
  3791.0   0.045       0  4542.3   0.035       0  4668.5    0.07       0
  4997.4    0.07       0  5002.5    0.07       0  5339.1   0.035       0
  5679.3    0.07       0  5722.5   0.035       0
Bank Sta=4997.4,5002.5
Exp/Cntr=0.3,0.1

Type RM Length L Ch R = 1,150,0,0,0
BEGIN DESCRIPTION:
Clear Fork Trib6 1.0
END DESCRIPTION:
XS GIS Cut Line= 4
      1441450.47      6946911.54      1440166.57      6947600.61
      1440041.22      6948224.72      1439972.22      6949178.93
#Sta/Elev= 30
  2906.3 1825.95  3039.6 1827.75  3196.6 1825.65  3556.4 1820.76  3587.9 1820.57
  3756.6 1819.48  3786.4 1818.05  3822.4 1819.74  3992.1 1819.93  4172.3 1818.39
  4325.8 1819.79  4534.2 1819.56  4549.3 1820.59  4666.8 1820.41  4696.9 1819.85
  4707.6 1818.58  4854.6 1818.77  4900.4 1820.09  4951.3 1818.98  5009.9 1815.73
  5010.4 1815.23  5015.3 1815.73  5033.4 1818.81  5157.1 1818.15  5203.8 1821.58
  5455.2 1824.45  5554.7 1826.35  5627.3 1826.33  5785.3 1828.15  5956.7 1827.61
#Mann=8,-1,0
  2906.3   0.045       0  3196.6    0.07       0  3556.4   0.045       0
  3587.9    0.07       0  5009.9    0.07       0  5015.3    0.07       0
  5455.2   0.035       0  5627.3    0.07       0
Bank Sta=5009.9,5015.3
Exp/Cntr=0.3,0.1

Chan Stop Cuts=-1