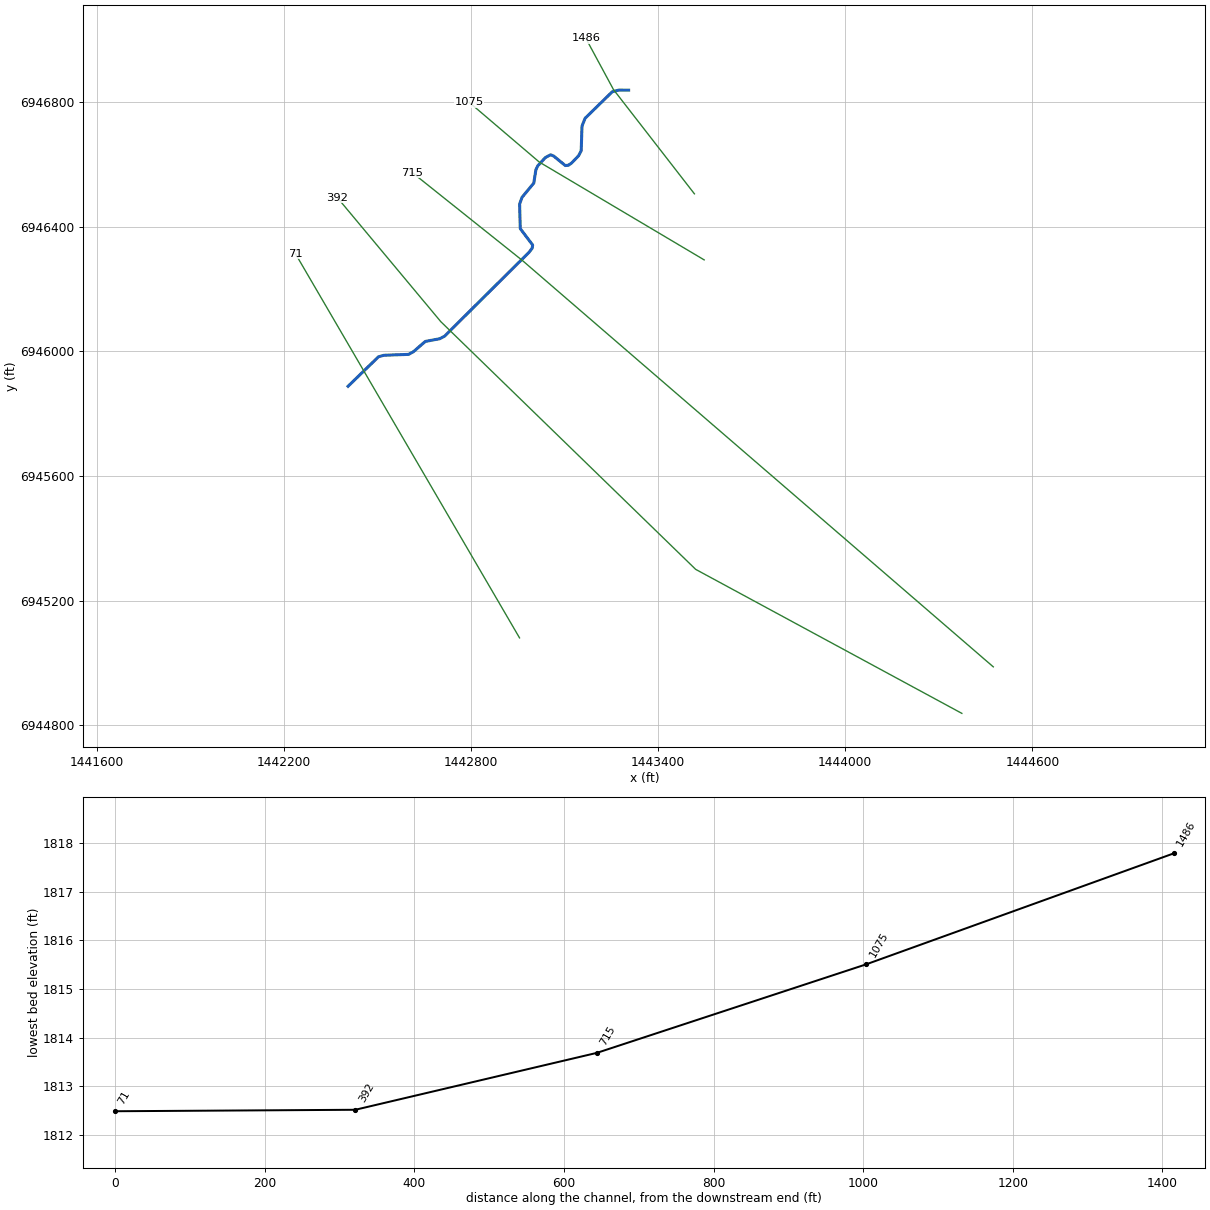
--- Clear Fork Trib7.prj (project) ---

Proj Title=Clear Fork Trib7 Base Level Engineering
Current Plan=p01
Default Exp/Contr=0.3,0.1
English Units
Geom File=g01
Flow File=f01
Plan File=p01
BEGIN DESCRIPTION:
Clear Fork Trib7
END DESCRIPTION:

--- Clear Fork Trib7.p01 (plan) ---

Plan Title=Multiple Run
Short Identifier=Multiple
Geom File=g01
Flow File=f01
Subcritical Flow
K Sum by GR= 0
Std Step Tol= 0.01
Critical Tol= 0.01
Num of Std Step Trials= 20
Max Error Tol= 0.3
Flow Tol Ratio= 0.001
Split Flow NTrial= 30
Split Flow Tol= 0.02
Split Flow Ratio= 0.02
Log Output Level= 0
Friction Slope Method= 1
Unsteady Friction Slope Method= 2
Unsteady Bridges Friction Slope Method= 1
Parabolic Critical Depth
Global Vel Dist=  1 , 1 , 1
Global Log Level= 0
CheckData=True
Encroach Param= -1, 0, 0, 0
BEGIN DESCRIPTION:
Multiple Run
END DESCRIPTION:

--- Clear Fork Trib7.f01 (steady flow) ---

Flow Title=Multiple
Number of Profiles=7
Profile Names=10-year,25-year,50-year,1pct_min,100-year,1pct_plu,500-year
River Rch & RM= Clear Fork Trib7,Reach-1,1486
     257     359     443     272     543    1084     827
Boundary for River Rch & Prof#=Clear Fork Trib7,Reach-1,1
Up Type=0
Dn Type=3
Dn Slope=0.005
Boundary for River Rch & Prof#=Clear Fork Trib7,Reach-1,2
Up Type=0
Dn Type=3
Dn Slope=0.005
Boundary for River Rch & Prof#=Clear Fork Trib7,Reach-1,3
Up Type=0
Dn Type=3
Dn Slope=0.005
Boundary for River Rch & Prof#=Clear Fork Trib7,Reach-1,4
Up Type=0
Dn Type=3
Dn Slope=0.005
Boundary for River Rch & Prof#=Clear Fork Trib7,Reach-1,5
Up Type=0
Dn Type=3
Dn Slope=0.005
Boundary for River Rch & Prof#=Clear Fork Trib7,Reach-1,6
Up Type=0
Dn Type=3
Dn Slope=0.005
Boundary for River Rch & Prof#=Clear Fork Trib7,Reach-1,7
Up Type=0
Dn Type=3
Dn Slope=0.005

--- Clear Fork Trib7.g01 (geometry) ---

Geom Title=Existing Conditions

River Reach=Clear Fork Trib7,Reach-1
Reach XY= 30
      1443305.00      6946838.00      1443273.11      6946838.08
      1443252.46      6946832.70      1443165.50      6946747.81
      1443155.52      6946722.78      1443152.85      6946643.50
      1443144.48      6946627.51      1443122.12      6946604.21
      1443111.99      6946597.17      1443101.86      6946596.08
      1443064.89      6946626.34      1443054.80      6946630.52
      1443037.96      6946621.76      1443013.14      6946594.68
      1443007.50      6946582.36      1443000.78      6946539.81
      1442963.04      6946494.06      1442955.37      6946472.73
      1442957.37      6946393.89      1442997.12      6946341.22
      1442995.87      6946331.26      1442985.71      6946317.97
      1442714.68      6946048.76      1442698.97      6946040.50
      1442652.83      6946031.86      1442614.65      6945998.84
      1442599.03      6945990.33      1442520.21      6945987.49
      1442502.55      6945982.54      1442405.00      6945888.00

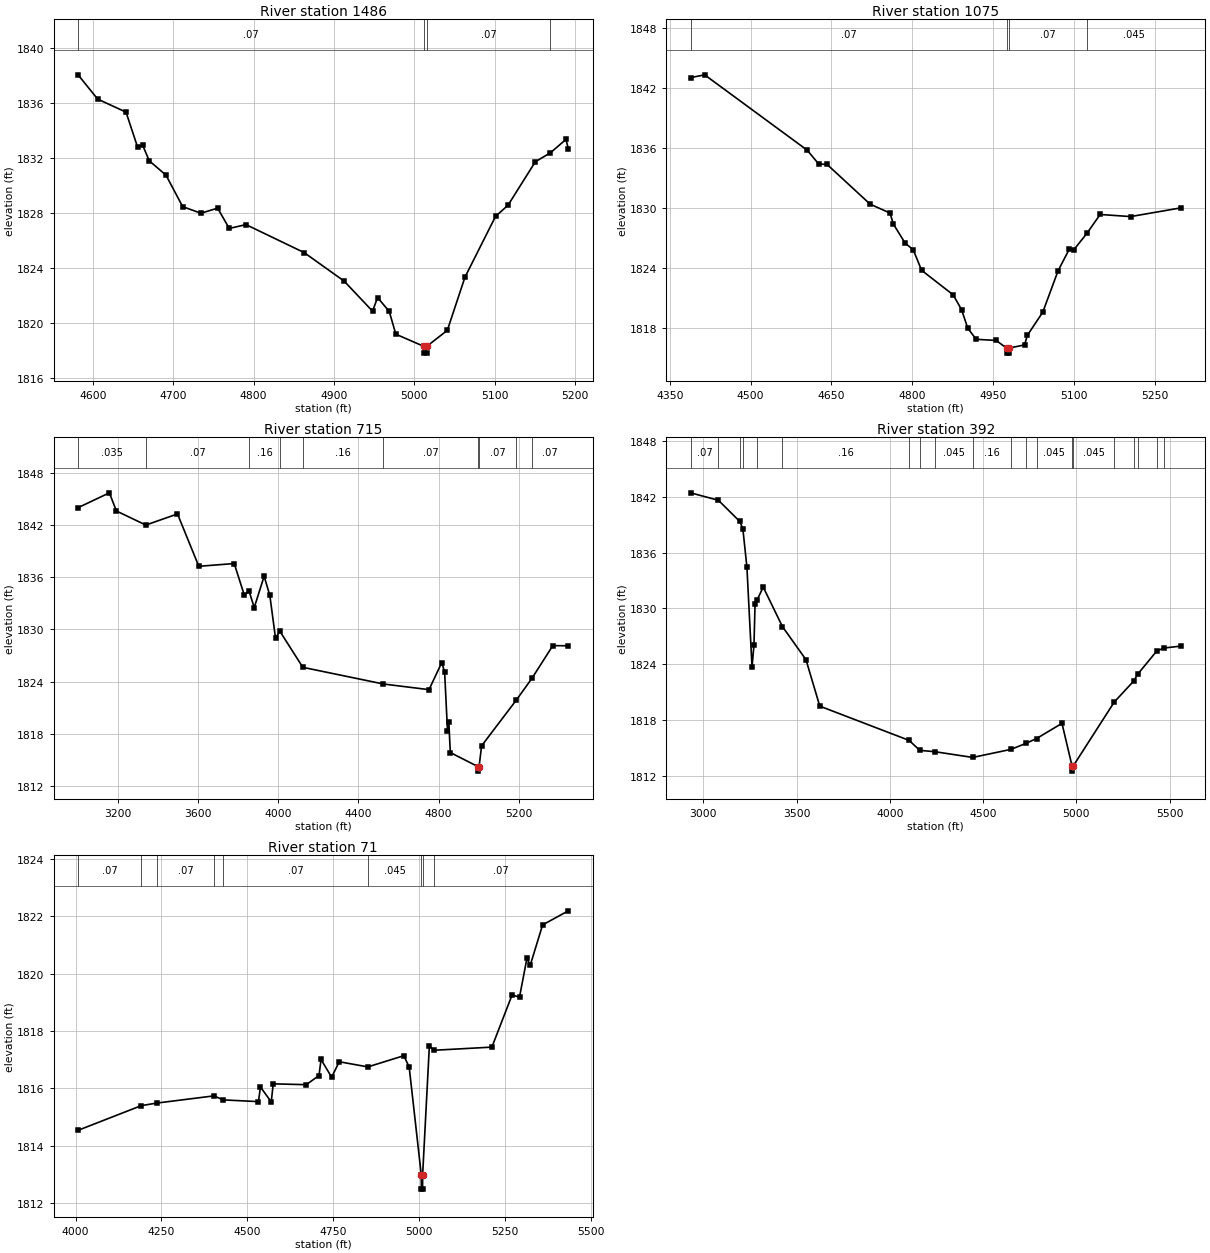
Type RM Length L Ch R = 1,1486,411,411,411
BEGIN DESCRIPTION:
Clear Fork Trib7 3.0
END DESCRIPTION:
XS GIS Cut Line= 3
      1443516.12      6946505.28      1443256.30      6946840.06
      1443167.78      6947004.14
#Sta/Elev= 30
  4581.6 1838.08  4606.0 1836.31  4641.3 1835.36  4655.7 1832.81  4662.1 1832.94
  4670.2 1831.81  4691.0 1830.77  4711.8 1828.47  4734.5 1827.99  4755.3 1828.36
  4769.8 1826.88  4790.6 1827.16  4863.0 1825.12  4912.8 1823.04  4948.1 1820.85
  4954.4 1821.84  4968.9 1820.83  4977.1 1819.17  5011.7 1818.29  5011.9 1817.79
  5015.4 1817.79  5015.7 1818.29  5041.2 1819.45  5063.1 1823.32  5101.2 1827.76
  5116.7 1828.57  5150.7 1831.74  5169.6 1832.40  5188.8 1833.37  5191.8 1832.70
#Mann=4,-1,0
  4581.6    0.07       0  5011.7    0.07       0  5015.7    0.07       0
  5169.6   0.045       0
Bank Sta=5011.7,5015.7
Exp/Cntr=0.3,0.1

Type RM Length L Ch R = 1,1075,360,360,360
BEGIN DESCRIPTION:
Mapping XS b832cb16
END DESCRIPTION:
XS GIS Cut Line= 3
      1443547.38      6946293.45      1443017.88      6946607.68
      1442793.95      6946798.62
#Sta/Elev= 30
  4388.6 1843.05  4414.6 1843.33  4604.9 1835.80  4626.3 1834.42  4641.9 1834.37
  4721.8 1830.40  4758.8 1829.51  4764.7 1828.43  4786.7 1826.51  4801.7 1825.85
  4817.3 1823.79  4875.8 1821.34  4891.4 1819.87  4903.0 1818.00  4918.6 1816.89
  4955.7 1816.78  4975.1 1816.01  4975.3 1815.51  4978.8 1815.51  4979.1 1816.01
  5008.4 1816.33  5013.6 1817.29  5042.2 1819.60  5070.7 1823.75  5091.6 1825.92
  5099.3 1825.80  5124.5 1827.51  5148.7 1829.37  5205.2 1829.16  5298.6 1830.03
#Mann=4,-1,0
  4388.6    0.07       0  4975.1    0.07       0  4979.1    0.07       0
  5124.5   0.045       0
Bank Sta=4975.1,4979.1
Exp/Cntr=0.3,0.1

Type RM Length L Ch R = 1,715,323,323,323
BEGIN DESCRIPTION:
Mapping XS 2435a83b
END DESCRIPTION:
XS GIS Cut Line= 3
      1444474.76      6944988.00      1442964.06      6946291.71
      1442611.60      6946572.98
#Sta/Elev= 30
  3001.2 1844.02  3157.4 1845.73  3192.5 1843.64  3339.5 1842.02  3497.4 1843.30
  3603.8 1837.27  3780.5 1837.59  3830.9 1833.94  3854.5 1834.42  3880.3 1832.52
  3929.7 1836.13  3958.2 1833.91  3986.7 1828.96  4007.8 1829.81  4122.8 1825.64
  4525.1 1823.72  4752.4 1823.07  4816.0 1826.19  4830.3 1825.11  4844.6 1818.34
  4851.2 1819.35  4858.8 1815.83  4998.3 1814.19  4998.5 1813.69  5002.3 1814.19
  5014.7 1816.60  5187.8 1821.86  5265.9 1824.37  5370.2 1828.14  5447.6 1828.12
#Mann=10,-1,0
  3001.2   0.035       0  3339.5    0.07       0  3854.5    0.16       0
  4007.8    0.07       0  4122.8    0.16       0  4525.1    0.07       0
  4998.3    0.07       0  5002.3    0.07       0  5187.8   0.045       0
  5265.9    0.07       0
Bank Sta=4998.3,5002.3
Exp/Cntr=0.3,0.1

Type RM Length L Ch R = 1,392,321,321,321
BEGIN DESCRIPTION:
Mapping XS 62de708a
END DESCRIPTION:
XS GIS Cut Line= 4
      1444374.00      6944838.74      1443520.02      6945300.78
      1442702.61      6946095.20      1442371.02      6946492.76
#Sta/Elev= 30
  2931.7 1842.41  3080.6 1841.61  3195.0 1839.34  3211.6 1838.57  3233.4 1834.44
  3260.9 1823.68  3271.4 1826.10  3277.1 1830.46  3287.1 1830.86  3320.9 1832.29
  3423.7 1828.05  3550.1 1824.49  3624.1 1819.50  4103.3 1815.82  4160.1 1814.75
  4239.9 1814.61  4444.1 1813.99  4649.6 1814.86  4728.2 1815.49  4786.2 1816.02
  4922.6 1817.65  4977.2 1813.02  4977.4 1812.52  4981.2 1813.02  5202.9 1819.94
  5307.0 1822.19  5328.6 1822.93  5431.6 1825.44  5469.6 1825.74  5560.2 1825.95
#Mann=20,-1,0
  2931.7    0.07       0  3080.6    0.16       0  3195.0    0.07       0
  3211.6    0.16       0  3287.1    0.07       0  3423.7    0.16       0
  4103.3    0.12       0  4160.1    0.16       0  4239.9   0.045       0
  4444.1    0.16       0  4649.6   0.045       0  4728.2    0.16       0
  4786.2   0.045       0  4977.2   0.045       0  4981.2   0.045       0
  5202.9    0.07       0  5307.0   0.035       0  5328.6    0.07       0
  5431.6   0.035       0  5469.6    0.07       0
Bank Sta=4977.2,4981.2
Exp/Cntr=0.3,0.1

Type RM Length L Ch R = 1,71,0,0,0
BEGIN DESCRIPTION:
Clear Fork Trib7 1.0
END DESCRIPTION:
XS GIS Cut Line= 2
      1442955.03      6945081.00      1442236.61      6946312.58
#Sta/Elev= 30
  4007.4 1814.54  4191.3 1815.40  4236.7 1815.49  4402.5 1815.74  4429.7 1815.60
  4532.0 1815.54  4537.8 1816.05  4569.2 1815.53  4575.0 1816.16  4671.0 1816.13
  4708.2 1816.45  4714.0 1817.01  4744.9 1816.39  4766.9 1816.93  4850.1 1816.75
  4954.6 1817.14  4970.3 1816.75  5005.5 1812.99  5005.8 1812.49  5009.3 1812.49
  5009.5 1812.99  5029.0 1817.47  5043.1 1817.33  5210.9 1817.44  5269.7 1819.26
  5291.2 1819.18  5312.7 1820.53  5322.6 1820.30  5358.4 1821.70  5433.2 1822.19
#Mann=9,-1,0
  4007.4    0.07       0  4191.3    0.16       0  4236.7    0.07       0
  4402.5    0.16       0  4429.7    0.07       0  4850.1   0.045       0
  5005.5   0.045       0  5009.5   0.045       0  5043.1    0.07       0
Bank Sta=5005.5,5009.5
Exp/Cntr=0.3,0.1

Chan Stop Cuts=-1