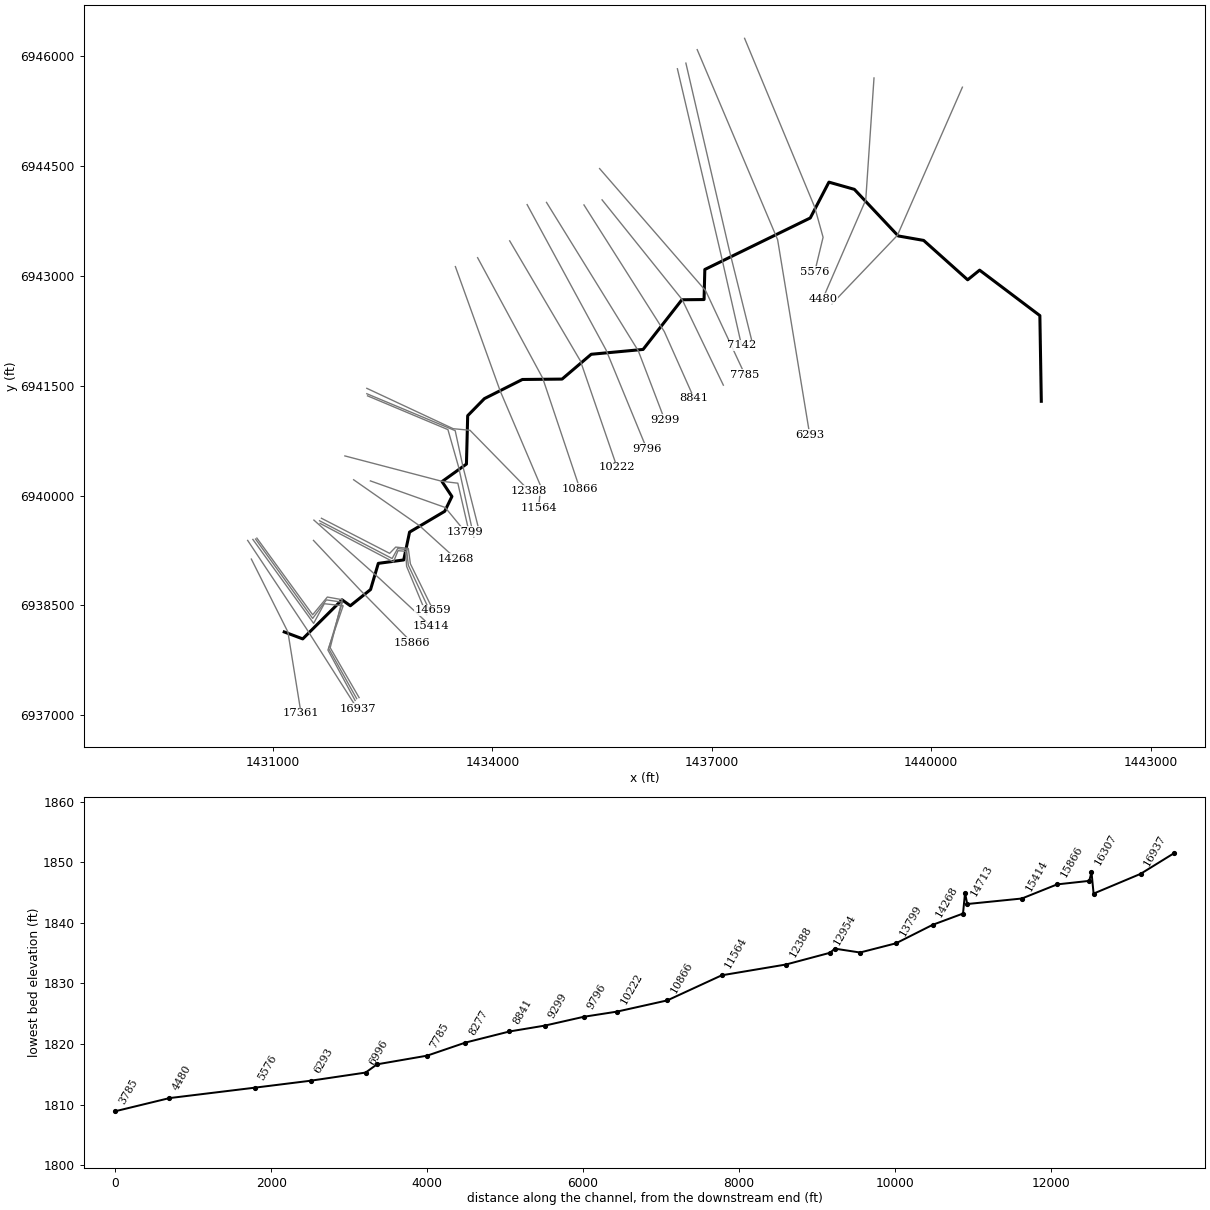
--- Clear Fork Trib8.prj (project) ---

Proj Title=Clear Fork Trib8 Base Level Engineering
Current Plan=p01
Default Exp/Contr=0.3,0.1
English Units
Geom File=g01
Flow File=f01
Plan File=p01
BEGIN DESCRIPTION:
Clear Fork Trib8
END DESCRIPTION:

--- Clear Fork Trib8.p01 (plan) ---

Plan Title=Multiple Run
Short Identifier=Multiple
Geom File=g01
Flow File=f01
Subcritical Flow
K Sum by GR= 0
Std Step Tol= 0.01
Critical Tol= 0.01
Num of Std Step Trials= 20
Max Error Tol= 0.3
Flow Tol Ratio= 0.001
Split Flow NTrial= 30
Split Flow Tol= 0.02
Split Flow Ratio= 0.02
Log Output Level= 0
Friction Slope Method= 1
Unsteady Friction Slope Method= 2
Unsteady Bridges Friction Slope Method= 1
Parabolic Critical Depth
Global Vel Dist=  1 , 1 , 1
Global Log Level= 0
CheckData=True
Encroach Param= -1, 0, 0, 0
BEGIN DESCRIPTION:
Multiple Run
END DESCRIPTION:

--- Clear Fork Trib8.f01 (steady flow) ---

Flow Title=Multiple
Number of Profiles=7
Profile Names=10-year,25-year,50-year,1pct_min,100-year,1pct_plu,500-year
River Rch & RM= Clear Fork Trib8,Reach-1,17361
     227     315     388     237     474     945     716
River Rch & RM= Clear Fork Trib8,Reach-1,16937
     331     467     581     359     716    1428    1101
River Rch & RM= Clear Fork Trib8,Reach-1,7142
     485     697     878     549    1095    2185    1725
River Rch & RM= Clear Fork Trib8,Reach-1,4480
     605     880    1116     702    1401    2795    2235
River Rch & RM= Clear Fork Trib8,Reach-1,3785
     625     911    1156     727    1451    2895    2318
River Rch & RM= Clear Fork Trib8,Reach-1,3219
     729    1069    1363     861    1719    3429    2769
Boundary for River Rch & Prof#=Clear Fork Trib8,Reach-1,1
Up Type=0
Dn Type=3
Dn Slope=0.005
Boundary for River Rch & Prof#=Clear Fork Trib8,Reach-1,2
Up Type=0
Dn Type=3
Dn Slope=0.005
Boundary for River Rch & Prof#=Clear Fork Trib8,Reach-1,3
Up Type=0
Dn Type=3
Dn Slope=0.005
Boundary for River Rch & Prof#=Clear Fork Trib8,Reach-1,4
Up Type=0
Dn Type=3
Dn Slope=0.005
Boundary for River Rch & Prof#=Clear Fork Trib8,Reach-1,5
Up Type=0
Dn Type=3
Dn Slope=0.005
Boundary for River Rch & Prof#=Clear Fork Trib8,Reach-1,6
Up Type=0
Dn Type=3
Dn Slope=0.005
Boundary for River Rch & Prof#=Clear Fork Trib8,Reach-1,7
Up Type=0
Dn Type=3
Dn Slope=0.005

--- Clear Fork Trib8.g01 (geometry) ---

Geom Title=Existing Conditions

River Reach=Clear Fork Trib8,Reach-1
Reach XY= 30
      1431155.00      6938138.00      1431407.84      6938043.09
      1431945.00      6938577.04      1432058.58      6938495.50
      1432335.18      6938717.06      1432441.26      6939074.62
      1432788.62      6939121.30      1432868.36      6939501.34
      1433349.17      6939785.69      1433447.47      6939987.99
      1433312.44      6940191.41      1433646.01      6940430.93
      1433662.99      6941091.34      1433891.70      6941324.60
      1434410.97      6941585.85      1434953.37      6941591.13
      1435351.67      6941929.99      1436061.06      6941996.14
      1436591.29      6942674.53      1436894.48      6942677.46
      1436905.00      6943088.00      1438346.54      6943791.50
      1438601.55      6944280.77      1438949.38      6944182.38
      1439548.66      6943546.02      1439896.70      6943484.93
      1440498.33      6942946.96      1440661.67      6943079.04
      1441485.37      6942458.16      1441505.00      6941288.00

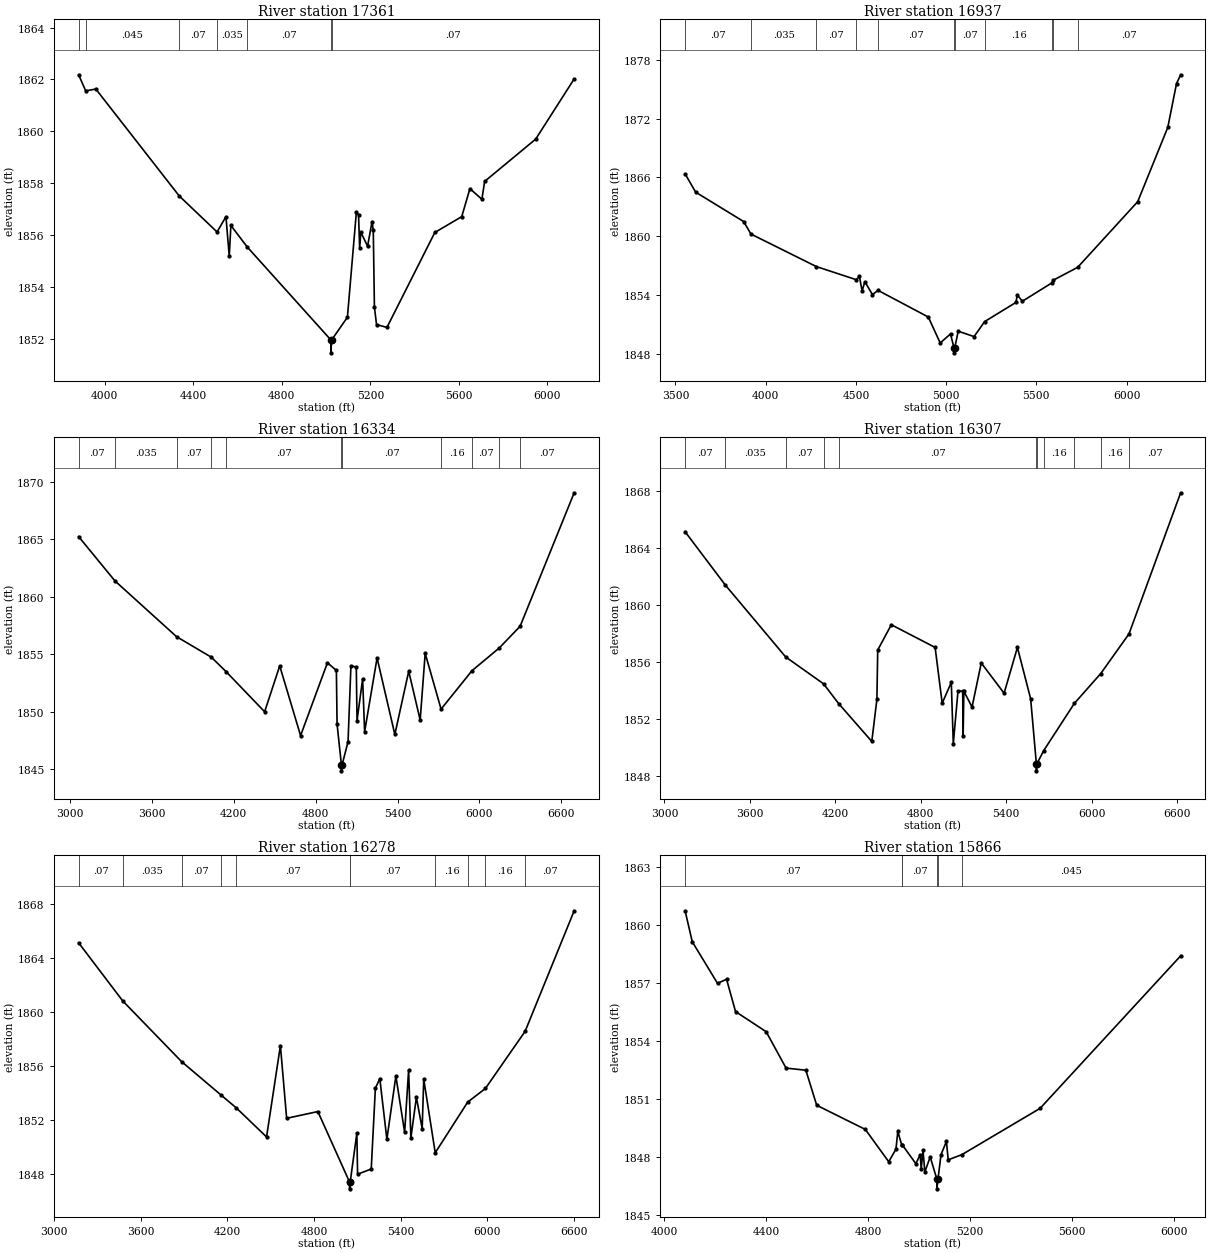
Type RM Length L Ch R = 1,17361,424,424,424
BEGIN DESCRIPTION:
Clear Fork Trib8 25.0
END DESCRIPTION:
XS GIS Cut Line= 3
      1430705.42      6939133.04      1431205.00      6938138.00
      1431385.11      6937026.30
#Sta/Elev= 30
  3881.7 1862.18  3913.6 1861.56  3959.4 1861.63  4336.2 1857.51  4507.3 1856.12
  4547.5 1856.71  4562.4 1855.19  4569.9 1856.37  4642.8 1855.55  5021.4 1851.96
  5021.7 1851.46  5025.4 1851.96  5096.4 1852.83  5136.9 1856.88  5146.7 1856.79
  5151.8 1855.51  5157.2 1856.11  5187.6 1855.57  5207.8 1856.52  5213.4 1856.19
  5218.5 1853.22  5228.1 1852.55  5275.1 1852.44  5491.5 1856.10  5613.1 1856.71
  5650.1 1857.79  5704.2 1857.38  5716.8 1858.07  5947.4 1859.70  6121.3 1862.02
#Mann=7,-1,0
  3881.7    0.07       0  3913.6   0.045       0  4336.2    0.07       0
  4507.3   0.035       0  4642.8    0.07       0  5021.4    0.07       0
  5025.4    0.07       0
Bank Sta=5021.4,5025.4
Exp/Cntr=0.3,0.1

Type RM Length L Ch R = 1,16937,603,603,603
BEGIN DESCRIPTION:
Clear Fork Trib8 24.0
END DESCRIPTION:
XS GIS Cut Line= 3
      1430654.98      6939388.02      1431455.00      6938188.00
      1432155.01      6937087.99
#Sta/Elev= 30
  3553.5 1866.37  3612.1 1864.50  3878.0 1861.50  3918.6 1860.22  4281.1 1856.90
  4502.2 1855.56  4519.5 1855.89  4534.5 1854.41  4549.6 1855.36  4591.6 1854.04
  4622.7 1854.47  4901.1 1851.75  4967.2 1849.10  5024.5 1850.02  5043.6 1848.59
  5043.9 1848.09  5047.8 1848.59  5066.9 1850.30  5154.9 1849.75  5213.4 1851.28
  5386.9 1853.24  5394.5 1854.00  5422.5 1853.36  5589.1 1855.27  5595.0 1855.52
  5729.3 1856.83  6061.7 1863.53  6228.5 1871.12  6276.7 1875.59  6299.6 1876.49
#Mann=11,-1,0
  3553.5    0.07       0  3918.6   0.035       0  4281.1    0.07       0
  4502.2   0.035       0  4622.7    0.07       0  5043.6    0.07       0
  5047.8    0.07       0  5213.4    0.16       0  5589.1    0.07       0
  5595.0    0.16       0  5729.3    0.07       0
Bank Sta=5043.6,5047.8
Exp/Cntr=0.3,0.1

Type RM Length L Ch R = 1,16334,27,27,27
BEGIN DESCRIPTION:
Mapping XS aa1b70fa
END DESCRIPTION:
XS GIS Cut Line= 6
      1430726.28      6939401.24      1431556.99      6938255.43
      1431702.83      6938523.65      1431960.64      6938495.01
      1431752.30      6937890.84      1432124.10      6937201.84
#Sta/Elev= 30
  3063.7 1865.25  3329.6 1861.39  3780.7 1856.53  4036.8 1854.73  4147.0 1853.44
  4426.4 1849.98  4536.9 1853.98  4689.7 1847.90  4886.4 1854.25  4952.0 1853.58
  4957.1 1848.89  4989.1 1845.33  4989.4 1844.83  4993.4 1845.33  5037.4 1847.37
  5058.6 1853.98  5097.9 1853.88  5103.3 1849.21  5144.4 1852.84  5158.9 1848.24
  5250.2 1854.67  5380.3 1848.00  5482.0 1853.51  5565.9 1849.26  5602.6 1855.07
  5719.0 1850.21  5945.5 1853.56  6145.3 1855.54  6298.0 1857.43  6694.1 1869.07
#Mann=11,-1,0
  3063.7    0.07       0  3329.6   0.035       0  3780.7    0.07       0
  4036.8   0.035       0  4147.0    0.07       0  4989.1    0.07       0
  4993.4    0.07       0  5719.0    0.16       0  5945.5    0.07       0
  6145.3    0.16       0  6298.0    0.07       0
Bank Sta=4989.1,4993.4
Exp/Cntr=0.3,0.1

Type RM Length L Ch R = 1,16307,29,29,29
BEGIN DESCRIPTION:
Mapping XS 633e8622
END DESCRIPTION:
XS GIS Cut Line= 6
      1430762.69      6939406.50      1431543.97      6938323.13
      1431731.47      6938575.74      1431950.22      6938544.49
      1431762.72      6937911.68      1432145.51      6937226.82
#Sta/Elev= 30
  3144.7 1865.13  3425.9 1861.41  3851.5 1856.35  4117.2 1854.47  4223.7 1853.08
  4456.2 1850.43  4492.0 1853.38  4497.9 1856.84  4593.4 1858.61  4901.1 1857.02
  4950.7 1853.11  5014.7 1854.57  5028.7 1850.27  5062.0 1853.98  5094.7 1853.95
  5097.9 1850.84  5102.9 1853.95  5160.4 1852.84  5225.2 1855.93  5385.6 1853.81
  5479.2 1857.02  5572.1 1853.42  5612.3 1848.87  5612.6 1848.37  5616.6 1848.87
  5663.9 1849.79  5879.4 1853.10  6064.7 1855.19  6263.0 1857.97  6625.8 1867.86
#Mann=11,-1,0
  3144.7    0.07       0  3425.9   0.035       0  3851.5    0.07       0
  4117.2   0.035       0  4223.7    0.07       0  5612.3    0.07       0
  5616.6    0.07       0  5663.9    0.16       0  5879.4    0.07       0
  6064.7    0.16       0  6263.0    0.07       0
Bank Sta=5612.3,5616.6
Exp/Cntr=0.3,0.1

Type RM Length L Ch R = 1,16278,412,412,412
BEGIN DESCRIPTION:
Mapping XS 2b3c8dfd
END DESCRIPTION:
XS GIS Cut Line= 6
      1430780.95      6939419.48      1431543.97      6938372.61
      1431744.49      6938614.80      1431947.62      6938578.34
      1431783.55      6937922.09      1432178.45      6937241.43
#Sta/Elev= 30
  3170.9 1865.14  3476.1 1860.84  3883.4 1856.35  4158.2 1853.86  4261.6 1852.93
  4472.1 1850.77  4567.9 1857.53  4611.1 1852.15  4827.3 1852.65  5046.8 1847.43
  5047.1 1846.93  5051.1 1847.43  5097.3 1851.05  5102.3 1848.01  5196.8 1848.40
  5225.5 1854.37  5256.1 1855.09  5305.1 1850.60  5367.4 1855.27  5428.1 1851.12
  5455.6 1855.72  5471.3 1850.70  5509.5 1853.70  5549.5 1851.39  5560.3 1855.05
  5639.9 1849.60  5864.7 1853.35  5987.5 1854.36  6262.4 1858.59  6601.9 1867.51
#Mann=11,-1,0
  3170.9    0.07       0  3476.1   0.035       0  3883.4    0.07       0
  4158.2   0.035       0  4261.6    0.07       0  5046.8    0.07       0
  5051.1    0.07       0  5639.9    0.16       0  5864.7    0.07       0
  5987.5    0.16       0  6262.4    0.07       0
Bank Sta=5046.8,5051.1
Exp/Cntr=0.3,0.1

Type RM Length L Ch R = 1,15866,452,452,452
BEGIN DESCRIPTION:
Clear Fork Trib8 22.0
END DESCRIPTION:
XS GIS Cut Line= 3
      1431555.01      6939387.99      1432184.52      6938718.73
      1432905.01      6937987.99
#Sta/Elev= 30
  4081.2 1860.72  4109.3 1859.12  4208.4 1856.97  4244.0 1857.18  4279.2 1855.51
  4399.4 1854.47  4477.5 1852.59  4555.2 1852.48  4597.7 1850.67  4788.6 1849.42
  4880.5 1847.75  4908.8 1848.40  4916.1 1849.32  4930.9 1848.64  4933.2 1848.63
  4986.9 1847.65  5003.9 1848.11  5007.9 1847.38  5015.0 1848.34  5022.1 1847.22
  5043.2 1848.00  5069.3 1846.85  5069.6 1846.35  5073.8 1846.85  5085.7 1848.12
  5106.9 1848.80  5113.9 1847.85  5168.0 1848.12  5474.6 1850.51  6026.2 1858.39
#Mann=6,-1,0
  4081.2    0.07       0  4930.9   0.035       0  4933.2    0.07       0
  5069.3    0.07       0  5073.8    0.07       0  5168.0   0.045       0
Bank Sta=5069.3,5073.8
Exp/Cntr=0.3,0.1

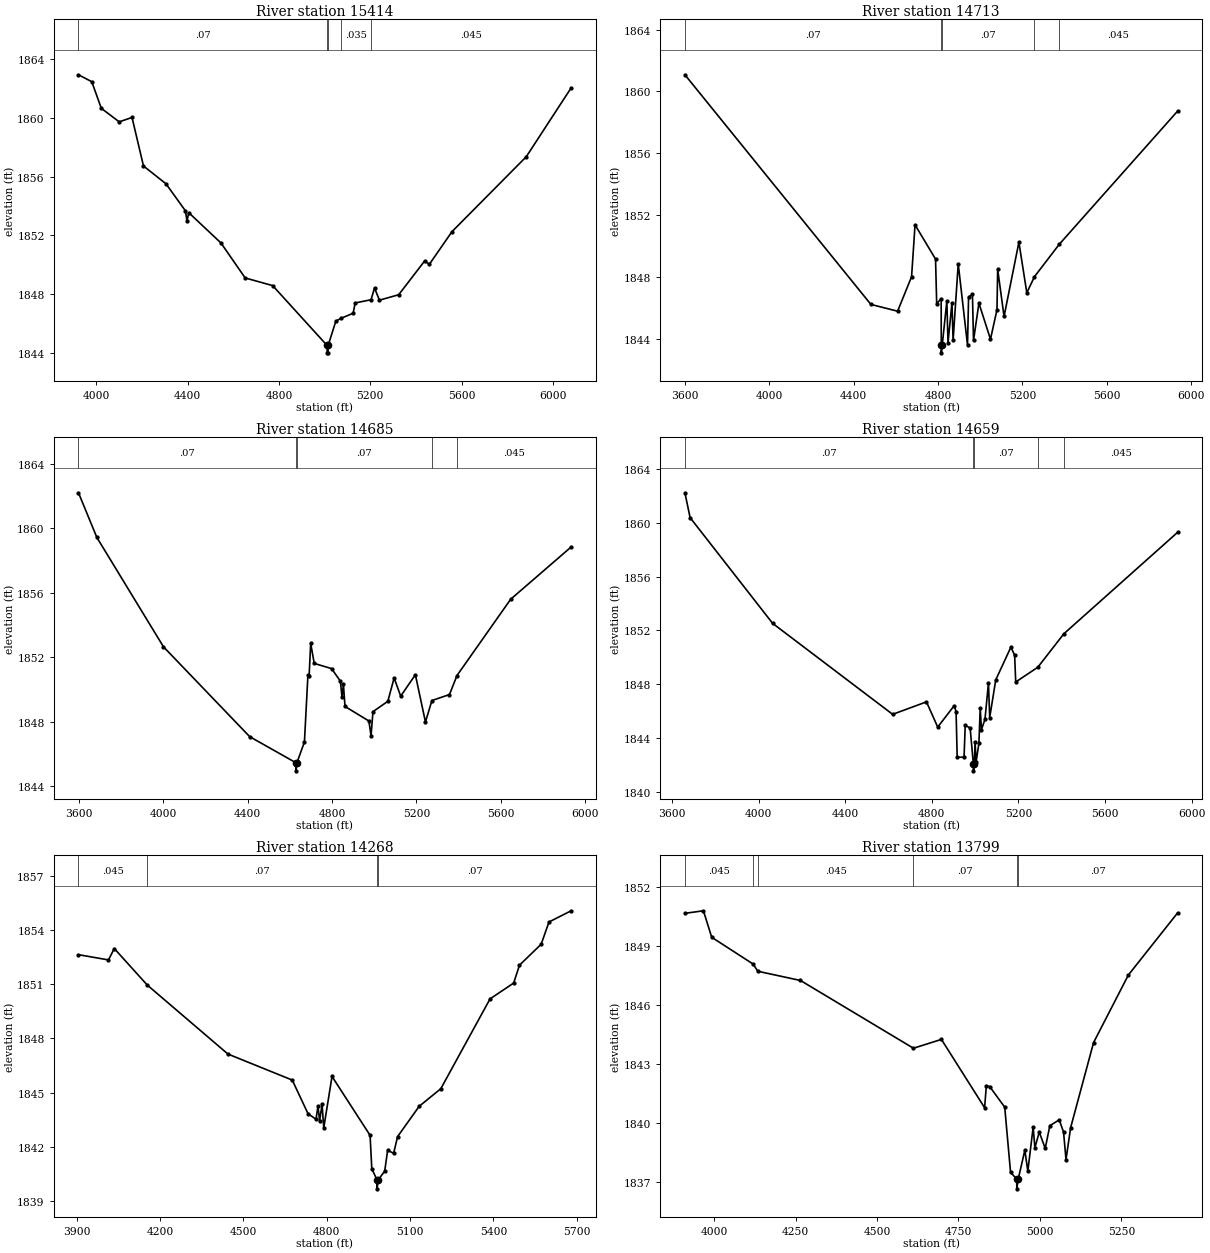
Type RM Length L Ch R = 1,15414,701,701,701
BEGIN DESCRIPTION:
Clear Fork Trib8 21.0
END DESCRIPTION:
XS GIS Cut Line= 3
      1431560.64      6939665.33      1432460.65      6938865.33
      1433160.34      6938215.61
#Sta/Elev= 30
  3921.5 1862.92  3979.7 1862.45  4021.5 1860.64  4100.1 1859.72  4156.1 1860.02
  4206.3 1856.72  4305.0 1855.51  4390.3 1853.67  4397.0 1852.96  4404.5 1853.55
  4545.8 1851.49  4652.0 1849.11  4772.4 1848.59  5011.0 1844.52  5011.3 1844.02
  5015.2 1844.02  5015.5 1844.52  5049.2 1846.17  5070.8 1846.36  5125.2 1846.71
  5133.8 1847.41  5203.6 1847.63  5218.8 1848.43  5240.3 1847.60  5324.8 1847.97
  5438.2 1850.26  5459.2 1850.04  5558.4 1852.26  5883.8 1857.35  6080.5 1862.03
#Mann=5,-1,0
  3921.5    0.07       0  5011.0    0.07       0  5015.5    0.07       0
  5070.8   0.035       0  5203.6   0.045       0
Bank Sta=5011,5015.5
Exp/Cntr=0.3,0.1

Type RM Length L Ch R = 1,14713,28,28,28
BEGIN DESCRIPTION:
Mapping XS 40b17fd2
END DESCRIPTION:
XS GIS Cut Line= 6
      1431645.54      6939620.01      1432648.14      6939093.97
      1432710.64      6939247.61      1432814.80      6939239.80
      1432827.83      6939034.07      1433103.26      6938371.46
#Sta/Elev= 30
  3600.8 1861.08  4481.8 1846.24  4608.4 1845.80  4674.6 1848.03  4691.0 1851.38
  4788.1 1849.17  4793.6 1846.28  4814.8 1846.62  4815.2 1843.61  4815.5 1843.11
  4819.8 1843.61  4841.7 1846.46  4847.1 1843.75  4865.9 1846.33  4871.3 1843.91
  4895.6 1848.86  4939.6 1843.61  4944.6 1846.71  4962.9 1846.89  4968.0 1843.91
  4993.6 1846.32  5048.4 1843.99  5079.2 1845.90  5082.4 1848.51  5112.7 1845.46
  5183.0 1850.26  5220.5 1846.99  5256.7 1848.03  5373.9 1850.12  5934.7 1858.73
#Mann=5,-1,0
  3600.8    0.07       0  4815.2    0.07       0  4819.8    0.07       0
  5256.7   0.035       0  5373.9   0.045       0
Bank Sta=4815.2,4819.8
Exp/Cntr=0.3,0.1

Type RM Length L Ch R = 1,14685,26,26,26
BEGIN DESCRIPTION:
Mapping XS 35a8b3ba
END DESCRIPTION:
XS GIS Cut Line= 6
      1431637.69      6939656.48      1432629.91      6939140.84
      1432705.43      6939276.26      1432827.83      6939263.24
      1432851.26      6939049.70      1433153.34      6938406.49
#Sta/Elev= 30
  3597.0 1862.21  3684.1 1859.44  4000.1 1852.66  4409.0 1847.09  4628.5 1845.47
  4628.8 1844.97  4633.1 1845.47  4668.7 1846.76  4685.2 1850.89  4690.8 1850.83
  4698.4 1852.87  4715.2 1851.63  4797.2 1851.31  4839.3 1850.53  4846.9 1849.54
  4853.6 1850.33  4861.2 1848.96  4974.5 1848.06  4984.7 1847.15  4993.8 1848.64
  5064.2 1849.28  5094.1 1850.73  5125.3 1849.60  5194.9 1850.93  5242.7 1848.00
  5273.4 1849.33  5356.7 1849.70  5392.3 1850.88  5647.0 1855.61  5933.8 1858.85
#Mann=5,-1,0
  3597.0    0.07       0  4628.5    0.07       0  4633.1    0.07       0
  5273.4   0.035       0  5392.3   0.045       0
Bank Sta=4628.5,4633.1
Exp/Cntr=0.3,0.1

Type RM Length L Ch R = 1,14659,391,391,391
BEGIN DESCRIPTION:
Mapping XS 89d4d18c
END DESCRIPTION:
XS GIS Cut Line= 6
      1431663.76      6939690.32      1432596.05      6939211.15
      1432679.39      6939297.09      1432851.26      6939278.86
      1432879.91      6939067.93      1433192.27      6938432.79
#Sta/Elev= 30
  3659.2 1862.26  3683.1 1860.41  4064.4 1852.53  4618.9 1845.75  4775.1 1846.68
  4827.1 1844.80  4902.9 1846.39  4911.9 1845.96  4917.0 1842.55  4948.7 1842.56
  4954.2 1844.93  4976.9 1844.73  4991.8 1842.04  4992.2 1841.54  4996.4 1842.04
  4999.6 1843.67  5004.5 1842.21  5017.5 1843.61  5023.4 1846.24  5029.1 1844.61
  5045.3 1845.37  5061.5 1848.08  5067.2 1845.51  5095.2 1848.32  5165.2 1850.76
  5182.4 1850.15  5187.4 1848.16  5289.5 1849.26  5409.6 1851.75  5935.1 1859.31
#Mann=5,-1,0
  3659.2    0.07       0  4991.8    0.07       0  4996.4    0.07       0
  5289.5   0.035       0  5409.6   0.045       0
Bank Sta=4991.8,4996.4
Exp/Cntr=0.3,0.1

Type RM Length L Ch R = 1,14268,469,469,469
BEGIN DESCRIPTION:
Clear Fork Trib8 19.0
END DESCRIPTION:
XS GIS Cut Line= 3
      1432103.88      6940216.35      1433005.00      6939588.00
      1433504.93      6939135.61
#Sta/Elev= 30
  3907.1 1852.63  4015.0 1852.34  4035.9 1852.97  4154.5 1850.95  4444.9 1847.13
  4676.3 1845.69  4733.0 1843.83  4761.8 1843.52  4768.8 1844.24  4774.9 1843.44
  4783.6 1844.34  4789.7 1843.05  4819.4 1845.89  4956.4 1842.63  4962.5 1840.79
  4981.1 1840.17  4981.4 1839.67  4985.7 1840.17  5009.0 1840.65  5019.5 1841.80
  5041.2 1841.64  5055.3 1842.56  5133.1 1844.24  5210.8 1845.21  5387.9 1850.18
  5473.0 1851.06  5494.0 1852.05  5572.1 1853.21  5600.1 1854.44  5679.9 1855.06
#Mann=4,-1,0
  3907.1   0.045       0  4154.5    0.07       0  4981.1    0.07       0
  4985.7    0.07       0
Bank Sta=4981.1,4985.7
Exp/Cntr=0.3,0.1

Type RM Length L Ch R = 1,13799,461,461,461
BEGIN DESCRIPTION:
Clear Fork Trib8 18.0
END DESCRIPTION:
XS GIS Cut Line= 3
      1432333.00      6940200.75      1433355.00      6939838.00
      1433627.31      6939508.02
#Sta/Elev= 30
  3910.2 1850.66  3967.0 1850.79  3992.5 1849.44  4119.3 1848.08  4134.1 1847.71
  4265.0 1847.24  4611.7 1843.79  4697.6 1844.24  4830.2 1840.76  4835.5 1841.89
  4846.1 1841.83  4891.9 1840.79  4909.8 1837.47  4928.7 1837.13  4929.0 1836.63
  4933.4 1837.13  4953.7 1838.60  4962.8 1837.53  4979.2 1839.77  4984.5 1838.72
  4997.9 1839.52  5016.2 1838.69  5030.5 1839.85  5059.2 1840.14  5072.5 1839.52
  5080.0 1838.12  5094.3 1839.75  5164.7 1844.08  5271.5 1847.52  5422.5 1850.68
#Mann=6,-1,0
  3910.2   0.045       0  4119.3    0.07       0  4134.1   0.045       0
  4611.7    0.07       0  4928.7    0.07       0  4933.4    0.07       0
Bank Sta=4928.7,4933.4
Exp/Cntr=0.3,0.1

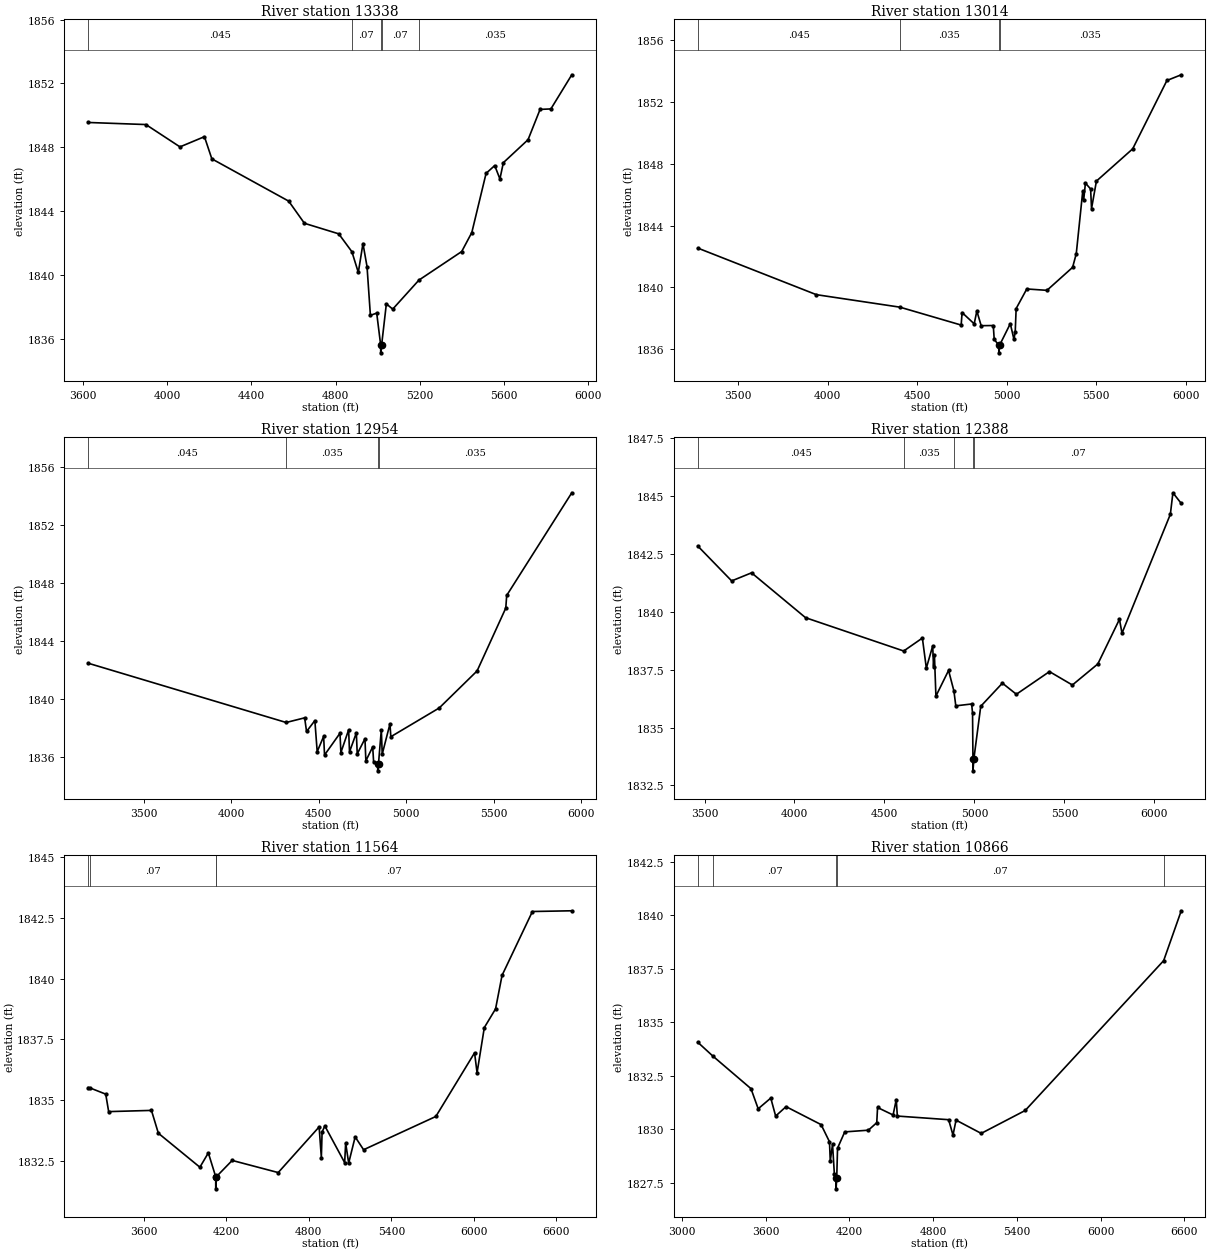
Type RM Length L Ch R = 1,13338,324,324,324
BEGIN DESCRIPTION:
Mapping XS 6734b245
END DESCRIPTION:
XS GIS Cut Line= 4
      1431984.05      6940541.89      1433309.60      6940195.53
      1433528.35      6940169.49      1433686.78      6939481.23
#Sta/Elev= 30
  3625.6 1849.55  3899.3 1849.42  4061.1 1848.02  4177.3 1848.66  4212.5 1847.27
  4577.5 1844.62  4652.3 1843.23  4815.2 1842.57  4877.7 1841.45  4908.2 1840.15
  4930.3 1841.96  4949.6 1840.52  4965.6 1837.46  4995.6 1837.60  5014.3 1835.61
  5014.6 1835.11  5019.0 1835.61  5041.4 1838.18  5071.6 1837.85  5196.2 1839.67
  5399.3 1841.46  5447.3 1842.65  5515.1 1846.36  5556.1 1846.85  5580.8 1846.01
  5597.1 1847.03  5714.4 1848.47  5771.6 1850.37  5822.9 1850.40  5922.2 1852.54
#Mann=5,-1,0
  3625.6   0.045       0  4877.7    0.07       0  5014.3    0.07       0
  5019.0    0.07       0  5196.2   0.035       0
Bank Sta=5014.3,5019
Exp/Cntr=0.3,0.1

Type RM Length L Ch R = 1,13014,60,60,60
BEGIN DESCRIPTION:
Mapping XS 76980999
END DESCRIPTION:
XS GIS Cut Line= 4
      1432293.94      6941362.21      1433392.93      6940901.26
      1433538.76      6940390.84      1433747.10      6939435.08
#Sta/Elev= 30
  3274.7 1842.54  3937.3 1839.52  4404.1 1838.71  4746.2 1837.55  4751.4 1838.36
  4819.0 1837.63  4833.8 1838.46  4858.0 1837.51  4925.6 1837.52  4930.8 1836.62
  4956.2 1836.25  4956.6 1835.75  4961.0 1836.25  5020.7 1837.64  5041.1 1836.62
  5048.2 1837.12  5053.3 1838.62  5112.8 1839.89  5225.4 1839.80  5368.7 1841.29
  5389.1 1842.17  5425.3 1846.23  5430.4 1845.64  5440.3 1846.75  5469.3 1846.37
  5474.4 1845.10  5501.7 1846.88  5704.3 1848.97  5895.5 1853.40  5975.5 1853.77
#Mann=4,-1,0
  3274.7   0.045       0  4404.1   0.035       0  4956.2   0.035       0
  4961.0   0.035       0
Bank Sta=4956.2,4961
Exp/Cntr=0.3,0.1

Type RM Length L Ch R = 1,12954,566,566,566
BEGIN DESCRIPTION:
Clear Fork Trib8 17.0
END DESCRIPTION:
XS GIS Cut Line= 4
      1432283.97      6941391.28      1433492.32      6940886.94
      1433599.51      6940390.15      1433831.74      6939473.72
#Sta/Elev= 30
  3182.4 1842.48  4313.2 1838.40  4418.8 1838.72  4429.7 1837.78  4477.2 1838.53
  4490.5 1836.39  4527.3 1837.44  4532.5 1836.16  4620.8 1837.66  4625.9 1836.33
  4670.1 1837.89  4675.2 1836.38  4714.2 1837.68  4719.4 1836.24  4763.5 1837.28
  4768.6 1835.76  4807.7 1836.72  4812.8 1835.71  4836.1 1835.57  4836.5 1835.07
  4840.9 1835.57  4857.0 1837.90  4862.1 1836.22  4906.3 1838.30  4911.4 1837.42
  5187.9 1839.40  5404.2 1841.95  5568.2 1846.28  5573.4 1847.15  5945.4 1854.22
#Mann=4,-1,0
  3182.4   0.045       0  4313.2   0.035       0  4836.1   0.035       0
  4840.9   0.035       0
Bank Sta=4836.1,4840.9
Exp/Cntr=0.3,0.1

Type RM Length L Ch R = 1,12388,824,824,824
BEGIN DESCRIPTION:
Mapping XS 1c0db27d
END DESCRIPTION:
XS GIS Cut Line= 4
      1432283.96      6941465.08      1433464.54      6940913.85
      1433694.58      6940892.14      1434500.95      6940068.43
#Sta/Elev= 30
  3462.3 1842.85  3650.9 1841.34  3761.4 1841.69  4061.5 1839.75  4606.8 1838.31
  4710.6 1838.87  4732.6 1837.57  4768.0 1838.53  4772.5 1837.64  4777.5 1838.15
  4785.8 1836.36  4856.1 1837.47  4885.9 1836.58  4896.3 1835.94  4984.4 1836.02
  4989.4 1835.62  4991.6 1833.63  4991.9 1833.13  4996.4 1833.63  5034.9 1835.92
  5155.2 1836.92  5232.9 1836.44  5416.8 1837.42  5544.1 1836.84  5685.5 1837.75
  5805.7 1839.68  5819.8 1839.08  6088.5 1844.22  6102.7 1845.15  6149.0 1844.69
#Mann=5,-1,0
  3462.3   0.045       0  4606.8   0.035       0  4885.9    0.07       0
  4991.6    0.07       0  4996.4    0.07       0
Bank Sta=4991.6,4996.4
Exp/Cntr=0.3,0.1

Type RM Length L Ch R = 1,11564,698,698,698
BEGIN DESCRIPTION:
Mapping XS 50547170
END DESCRIPTION:
XS GIS Cut Line= 5
      1433494.93      6943127.37      1434106.91      6941430.34
      1434658.12      6940136.94      1434662.46      6940128.26
      1434632.08      6939833.09
#Sta/Elev= 30
  3195.7 1835.52  3210.4 1835.50  3322.6 1835.25  3343.9 1834.53  3655.1 1834.58
  3705.3 1833.64  4007.4 1832.24  4068.8 1832.83  4122.4 1831.85  4122.7 1831.35
  4127.3 1831.85  4242.3 1832.52  4577.0 1832.02  4874.6 1833.90  4890.7 1832.64
  4896.1 1833.69  4916.1 1833.94  5060.3 1832.43  5067.5 1833.24  5089.4 1832.41
  5136.6 1833.49  5197.9 1832.96  5723.4 1834.33  6005.0 1836.95  6023.2 1836.13
  6075.9 1837.99  6157.7 1838.76  6204.9 1840.14  6425.7 1842.77  6712.1 1842.80
#Mann=4,-1,0
  3195.7   0.035       0  3210.4    0.07       0  4122.4    0.07       0
  4127.3    0.07       0
Bank Sta=4122.4,4127.3
Exp/Cntr=0.3,0.1

Type RM Length L Ch R = 1,10866,644,644,644
BEGIN DESCRIPTION:
Mapping XS c14f018d
END DESCRIPTION:
XS GIS Cut Line= 3
      1433798.72      6943248.96      1434688.50      6941603.95
      1435196.31      6940093.56
#Sta/Elev= 30
  3114.2 1834.06  3222.9 1833.41  3495.7 1831.89  3547.3 1830.95  3637.5 1831.45
  3672.4 1830.61  3746.9 1831.05  3998.0 1830.21  4058.0 1829.41  4063.7 1828.51
  4079.9 1829.29  4093.0 1827.90  4105.0 1827.71  4105.3 1827.21  4109.9 1827.71
  4115.8 1829.11  4167.4 1829.87  4336.7 1829.95  4396.7 1830.30  4402.4 1831.01
  4513.7 1830.66  4536.4 1831.38  4544.1 1830.61  4911.6 1830.44  4942.8 1829.72
  4964.7 1830.42  5144.9 1829.80  5460.0 1830.87  6451.9 1837.87  6577.9 1840.20
#Mann=5,-1,0
  3114.2   0.035       0  3222.9    0.07       0  4105.0    0.07       0
  4109.9    0.07       0  6451.9   0.035       0
Bank Sta=4105,4109.9
Exp/Cntr=0.3,0.1

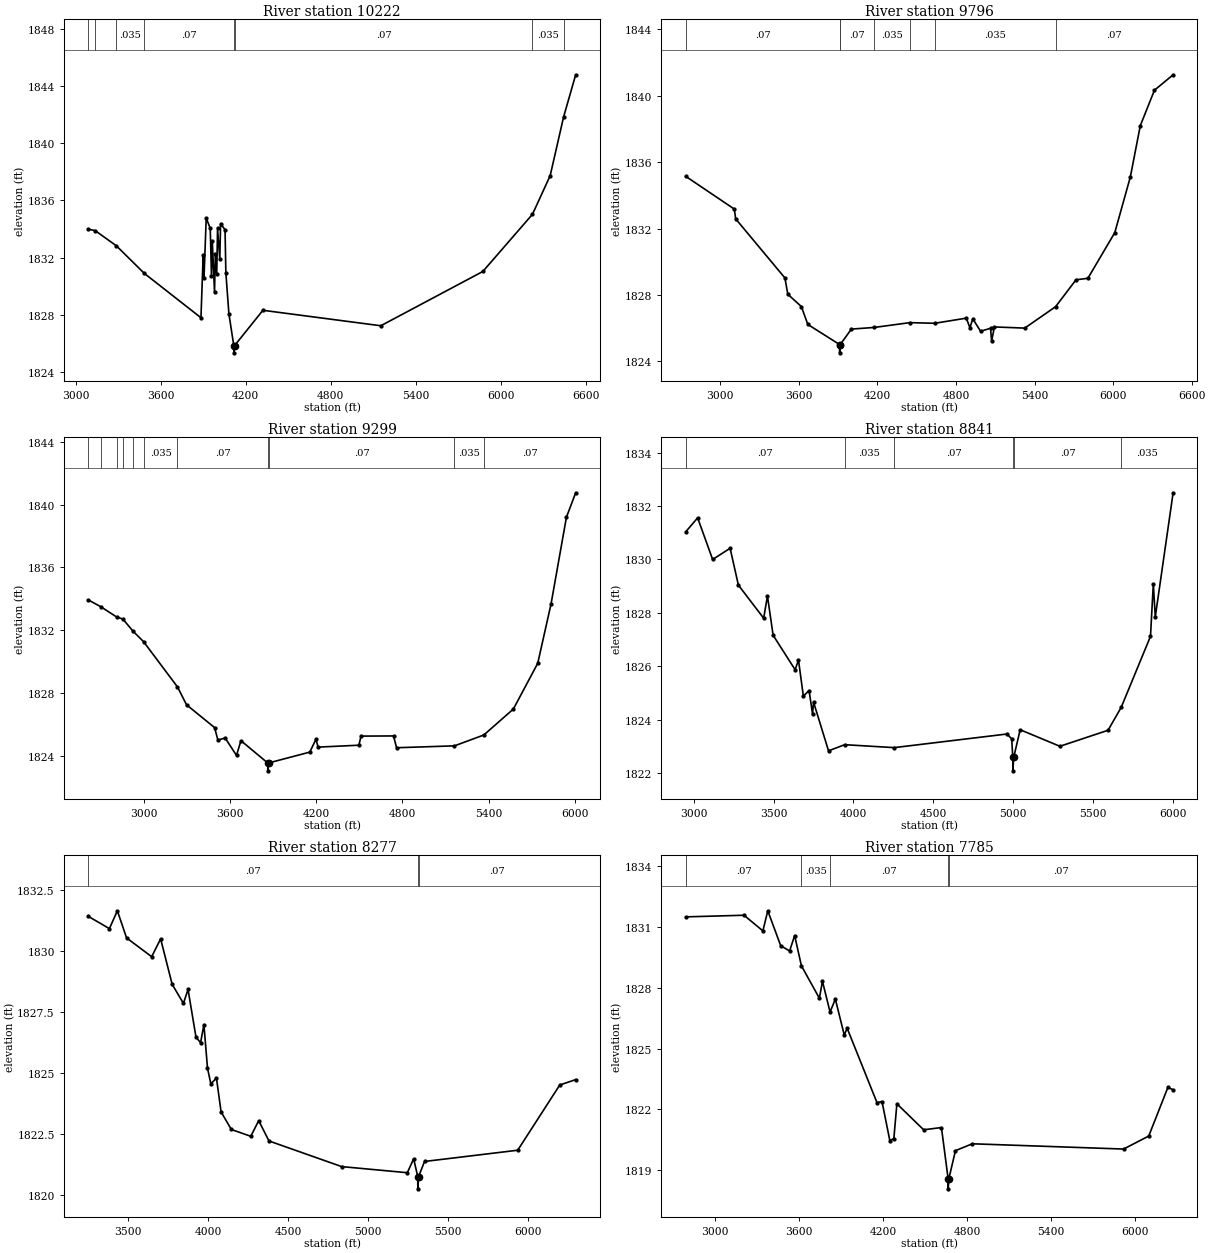
Type RM Length L Ch R = 1,10222,426,426,426
BEGIN DESCRIPTION:
Clear Fork Trib8 14.0
END DESCRIPTION:
XS GIS Cut Line= 3
      1434237.09      6943478.99      1435205.00      6941838.00
      1435705.01      6940387.96
#Sta/Elev= 30
  3090.5 1833.99  3138.9 1833.89  3288.5 1832.83  3485.0 1830.91  3885.2 1827.81
  3900.9 1832.21  3906.7 1830.59  3922.3 1834.77  3950.8 1834.04  3959.4 1830.71
  3965.2 1833.15  3980.9 1829.59  3986.7 1832.29  3996.5 1830.88  4002.3 1834.04
  4018.0 1831.89  4023.8 1834.38  4055.1 1833.95  4060.9 1830.95  4082.3 1828.09
  4116.9 1825.86  4117.3 1825.36  4121.9 1825.86  4322.4 1828.33  5154.3 1827.25
  5874.4 1831.04  6224.5 1835.03  6349.6 1837.73  6444.3 1841.83  6529.5 1844.77
#Mann=8,-1,0
  3090.5   0.035       0  3138.9    0.07       0  3288.5   0.035       0
  3485.0    0.07       0  4116.9    0.07       0  4121.9    0.07       0
  6224.5   0.035       0  6444.3    0.07       0
Bank Sta=4116.9,4121.9
Exp/Cntr=0.3,0.1

Type RM Length L Ch R = 1,9796,497,497,497
BEGIN DESCRIPTION:
Clear Fork Trib8 13.0
END DESCRIPTION:
XS GIS Cut Line= 3
      1434475.83      6943973.73      1435555.00      6941988.00
      1436112.13      6940636.02
#Sta/Elev= 30
  2736.2 1835.14  3106.9 1833.17  3117.3 1832.58  3493.5 1829.02  3515.4 1828.04
  3618.9 1827.30  3668.3 1826.22  3911.0 1825.01  3911.4 1824.51  3916.0 1825.01
  4000.9 1825.94  4176.0 1826.04  4448.1 1826.33  4637.0 1826.29  4878.9 1826.60
  4906.4 1826.02  4928.3 1826.56  4988.1 1825.81  5064.2 1825.99  5071.9 1825.21
  5093.6 1826.07  5325.2 1826.00  5560.9 1827.29  5716.7 1828.91  5807.4 1829.00
  6012.9 1831.75  6131.9 1835.11  6207.6 1838.19  6315.8 1840.33  6458.5 1841.26
#Mann=7,-1,0
  2736.2    0.07       0  3911.0   0.035       0  3916.0    0.07       0
  4176.0   0.035       0  4448.1    0.07       0  4637.0   0.035       0
  5560.9    0.07       0
Bank Sta=3911,3916
Exp/Cntr=0.3,0.1

Type RM Length L Ch R = 1,9299,458,458,458
BEGIN DESCRIPTION:
Clear Fork Trib8 12.0
END DESCRIPTION:
XS GIS Cut Line= 3
      1434740.61      6944004.09      1435995.48      6941976.85
      1436354.99      6941038.03
#Sta/Elev= 30
  2615.8 1833.93  2700.7 1833.51  2814.0 1832.84  2855.5 1832.72  2927.2 1831.94
  2999.7 1831.28  3235.6 1828.40  3298.9 1827.26  3493.9 1825.81  3516.8 1825.02
  3567.2 1825.15  3646.3 1824.04  3677.1 1824.98  3863.5 1823.56  3863.9 1823.06
  3868.9 1823.56  4155.7 1824.25  4198.9 1825.07  4213.6 1824.57  4497.2 1824.69
  4512.6 1825.27  4738.3 1825.28  4759.6 1824.53  5162.2 1824.65  5366.3 1825.34
  5571.8 1826.99  5741.3 1829.90  5834.0 1833.68  5941.1 1839.20  6005.3 1840.75
#Mann=11,-1,0
  2615.8    0.07       0  2700.7   0.035       0  2814.0    0.07       0
  2855.5   0.035       0  2927.2    0.07       0  2999.7   0.035       0
  3235.6    0.07       0  3863.5    0.07       0  3868.9    0.07       0
  5162.2   0.035       0  5366.3    0.07       0
Bank Sta=3863.5,3868.9
Exp/Cntr=0.3,0.1

Type RM Length L Ch R = 1,8841,564,564,564
BEGIN DESCRIPTION:
Clear Fork Trib8 11.0
END DESCRIPTION:
XS GIS Cut Line= 3
      1435252.73      6943969.42      1436351.03      6942239.64
      1436758.83      6941326.13
#Sta/Elev= 30
  2951.0 1831.04  3025.1 1831.56  3119.1 1830.00  3228.4 1830.42  3280.1 1829.04
  3438.3 1827.80  3462.0 1828.63  3497.6 1827.16  3635.0 1825.87  3656.2 1826.23
  3686.7 1824.88  3722.6 1825.09  3744.3 1824.20  3750.2 1824.66  3844.2 1822.83
  3945.4 1823.06  4255.2 1822.95  4960.6 1823.46  4990.1 1823.28  4997.3 1822.58
  4997.7 1822.08  5002.7 1822.58  5043.3 1823.62  5291.9 1823.00  5593.2 1823.60
  5675.6 1824.46  5858.8 1827.12  5876.5 1829.09  5888.8 1827.85  6000.4 1832.50
#Mann=6,-1,0
  2951.0    0.07       0  3945.4   0.035       0  4255.2    0.07       0
  4997.3    0.07       0  5002.7    0.07       0  5675.6   0.035       0
Bank Sta=4997.3,5002.7
Exp/Cntr=0.3,0.1

Type RM Length L Ch R = 1,8277,492,492,492
BEGIN DESCRIPTION:
Clear Fork Trib8 10.0
END DESCRIPTION:
XS GIS Cut Line= 3
      1435500.15      6944038.83      1436594.88      6942677.37
      1437158.11      6941508.49
#Sta/Elev= 30
  3253.0 1831.40  3384.6 1830.90  3434.2 1831.63  3491.8 1830.52  3648.6 1829.75
  3704.6 1830.48  3776.6 1828.62  3847.0 1827.84  3875.8 1828.41  3925.4 1826.46
  3954.2 1826.23  3975.0 1826.97  3997.3 1825.19  4018.2 1824.55  4053.4 1824.78
  4082.2 1823.40  4146.1 1822.68  4267.7 1822.40  4317.3 1823.04  4381.3 1822.21
  4835.7 1821.16  5245.6 1820.91  5285.3 1821.48  5310.8 1820.75  5311.2 1820.25
  5316.2 1820.75  5353.2 1821.37  5935.3 1821.83  6198.1 1824.50  6297.5 1824.72
#Mann=3,-1,0
  3253.0    0.07       0  5310.8    0.07       0  5316.2    0.07       0
Bank Sta=5310.8,5316.2
Exp/Cntr=0.3,0.1

Type RM Length L Ch R = 1,7785,643,643,643
BEGIN DESCRIPTION:
Clear Fork Trib8 9.0
END DESCRIPTION:
XS GIS Cut Line= 3
      1435466.55      6944465.85      1436916.25      6942797.77
      1437454.98      6941647.59
#Sta/Elev= 30
  2790.0 1831.49  3205.7 1831.57  3340.5 1830.80  3375.6 1831.79  3467.7 1830.07
  3531.4 1829.81  3567.5 1830.57  3615.6 1829.08  3744.1 1827.48  3765.9 1828.32
  3820.3 1826.80  3858.0 1827.44  3921.6 1825.67  3942.5 1826.00  4155.2 1822.34
  4191.3 1822.39  4247.3 1820.46  4275.8 1820.57  4297.5 1822.28  4488.5 1821.00
  4615.7 1821.11  4663.3 1818.59  4663.8 1818.09  4668.8 1818.59  4715.5 1819.97
  4836.1 1820.31  5916.3 1820.05  6095.9 1820.69  6232.9 1823.09  6270.1 1822.97
#Mann=5,-1,0
  2790.0    0.07       0  3615.6   0.035       0  3820.3    0.07       0
  4663.3    0.07       0  4668.8    0.07       0
Bank Sta=4663.3,4668.8
Exp/Cntr=0.3,0.1

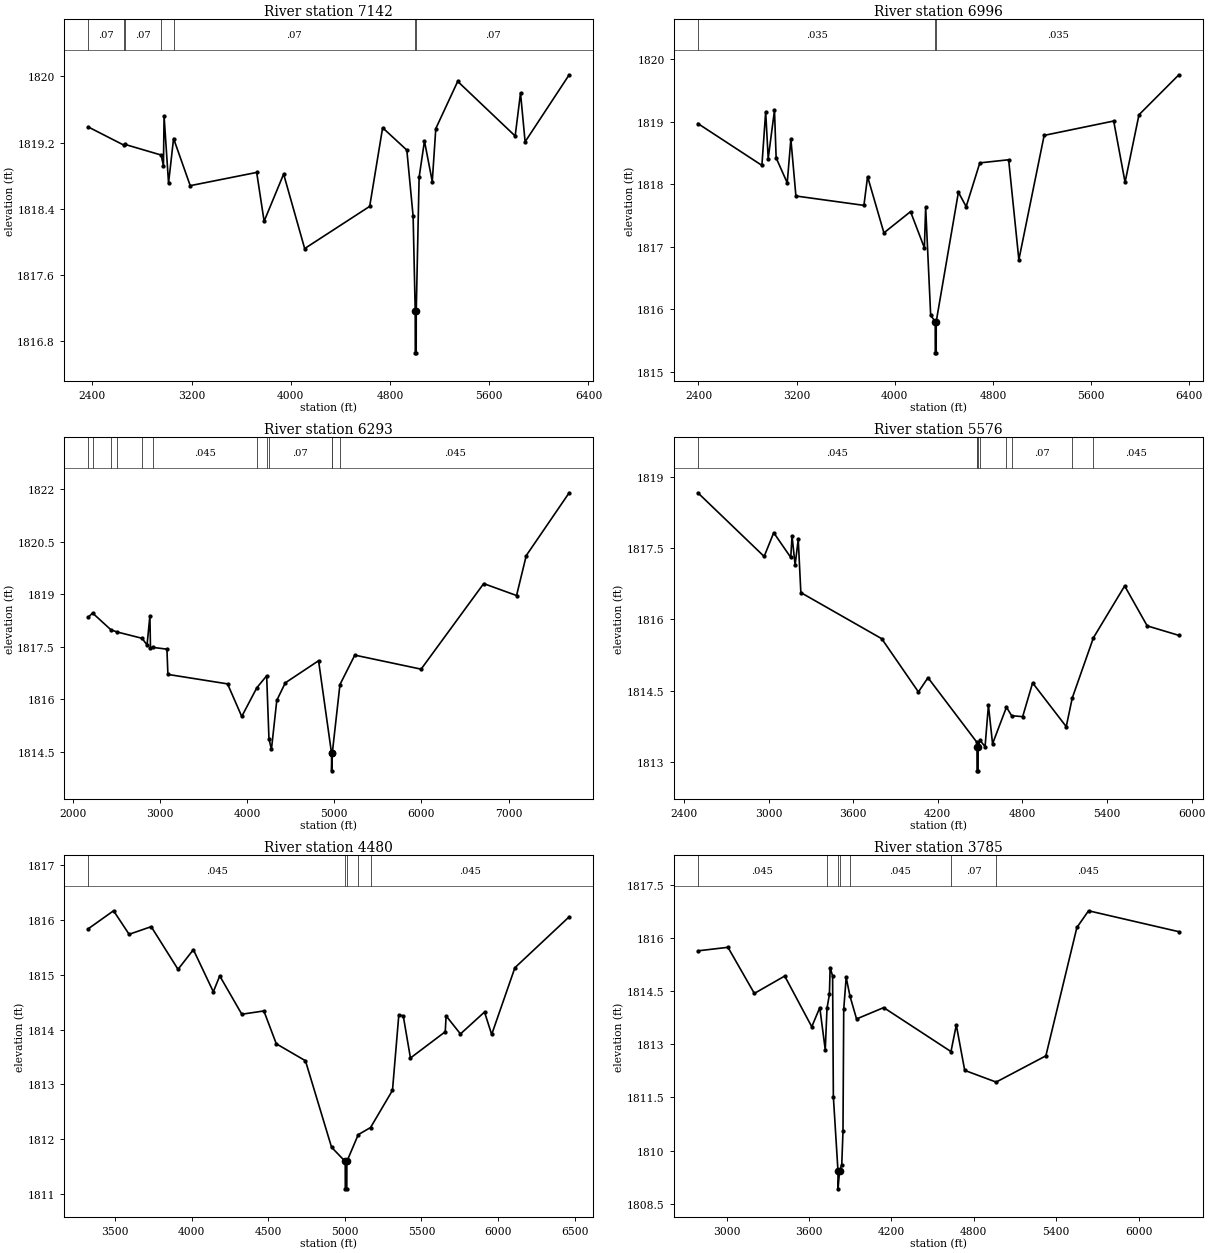
Type RM Length L Ch R = 1,7142,146,146,146
BEGIN DESCRIPTION:
Mapping XS f4eb993c
END DESCRIPTION:
XS GIS Cut Line= 3
      1436530.08      6945829.05      1437122.53      6943307.00
      1437406.92      6942051.51
#Sta/Elev= 30
  2366.3 1819.39  2653.9 1819.17  2659.9 1819.18  2955.0 1819.05  2973.2 1818.92
  2978.4 1819.52  3014.5 1818.71  3054.9 1819.25  3189.2 1818.68  3725.0 1818.84
  3784.9 1818.25  3942.2 1818.82  4111.8 1817.92  4636.1 1818.43  4740.3 1819.38
  4935.4 1819.11  4986.2 1818.31  5003.1 1817.16  5003.6 1816.66  5010.8 1816.66
  5011.3 1817.16  5034.5 1818.78  5077.6 1819.22  5140.5 1818.73  5169.0 1819.37
  5345.6 1819.94  5808.9 1819.28  5852.0 1819.80  5889.0 1819.21  6244.3 1820.02
#Mann=7,-1,0
  2366.3    0.07       0  2653.9   0.035       0  2659.9    0.07       0
  2955.0   0.035       0  3054.9    0.07       0  5003.1    0.07       0
  5011.3    0.07       0
Bank Sta=5003.1,5011.3
Exp/Cntr=0.3,0.1

Type RM Length L Ch R = 1,6996,703,703,703
BEGIN DESCRIPTION:
Mapping XS 883507fc
END DESCRIPTION:
XS GIS Cut Line= 3
      1436646.11      6945906.34      1437233.64      6943376.45
      1437552.93      6942092.37
#Sta/Elev= 30
  2394.9 1818.97  2916.8 1818.30  2947.6 1819.16  2968.1 1818.41  3019.4 1819.18
  3032.9 1818.42  3123.3 1818.02  3152.9 1818.72  3194.0 1817.81  3748.3 1817.66
  3778.2 1818.12  3911.3 1817.22  4128.2 1817.56  4241.1 1816.98  4251.4 1817.63
  4292.4 1815.90  4329.4 1815.80  4329.9 1815.30  4337.1 1815.30  4337.6 1815.80
  4518.3 1817.87  4581.6 1817.64  4692.8 1818.34  4927.8 1818.39  5011.1 1816.79
  5217.2 1818.78  5784.0 1819.01  5876.7 1818.03  5990.1 1819.11  6315.3 1819.75
#Mann=3,-1,0
  2394.9   0.035       0  4329.4   0.035       0  4337.6   0.035       0
Bank Sta=4329.4,4337.6
Exp/Cntr=0.3,0.1

Type RM Length L Ch R = 1,6293,717,717,717
BEGIN DESCRIPTION:
Mapping XS 2e751225
END DESCRIPTION:
XS GIS Cut Line= 3
      1436800.80      6946090.05      1437900.31      6943494.50
      1438338.93      6940832.42
#Sta/Elev= 30
  2177.3 1818.34  2228.1 1818.46  2439.5 1817.98  2509.9 1817.92  2795.1 1817.74
  2852.9 1817.55  2885.4 1818.38  2892.0 1817.47  2921.7 1817.48  3080.9 1817.43
  3091.8 1816.71  3776.0 1816.44  3938.8 1815.51  4111.9 1816.33  4224.5 1816.67
  4250.8 1814.88  4279.2 1814.57  4340.7 1815.97  4438.5 1816.47  4819.9 1817.10
  4968.8 1814.46  4969.3 1813.96  4977.0 1814.46  5065.1 1816.42  5235.5 1817.26
  5995.9 1816.86  6713.5 1819.30  7090.6 1818.96  7202.0 1820.10  7694.1 1821.89
#Mann=12,-1,0
  2177.3    0.07       0  2228.1   0.045       0  2439.5    0.07       0
  2509.9   0.045       0  2795.1    0.07       0  2921.7   0.045       0
  4111.9   0.035       0  4224.5   0.045       0  4250.8    0.07       0
  4968.8    0.07       0  4977.0    0.07       0  5065.1   0.045       0
Bank Sta=4968.8,4977
Exp/Cntr=0.3,0.1

Type RM Length L Ch R = 1,5576,1096,1096,1096
BEGIN DESCRIPTION:
Mapping XS edcbee25
END DESCRIPTION:
XS GIS Cut Line= 4
      1437448.58      6946244.72      1438407.25      6943938.95
      1438521.73      6943528.00      1438407.25      6943054.26
#Sta/Elev= 30
  2498.5 1818.66  2968.6 1817.32  3036.4 1817.82  3157.2 1817.30  3166.4 1817.75
  3188.1 1817.14  3210.3 1817.68  3228.8 1816.56  3802.3 1815.59  4062.5 1814.47
  4130.3 1814.77  4477.3 1813.41  4477.9 1813.31  4478.4 1812.81  4485.7 1812.81
  4486.2 1813.31  4499.4 1813.45  4535.2 1813.32  4559.0 1814.19  4588.3 1813.38
  4686.9 1814.15  4723.5 1813.97  4801.7 1813.95  4872.3 1814.66  5110.8 1813.74
  5153.2 1814.34  5303.6 1815.61  5525.1 1816.70  5684.8 1815.86  5909.6 1815.66
#Mann=9,-1,0
  2498.5   0.045       0  4477.3   0.035       0  4477.9    0.07       0
  4486.2   0.035       0  4499.4    0.07       0  4686.9   0.035       0
  4723.5    0.07       0  5153.2   0.035       0  5303.6   0.045       0
Bank Sta=4477.9,4486.2
Exp/Cntr=0.3,0.1

Type RM Length L Ch R = 1,4480,695,695,695
BEGIN DESCRIPTION:
Clear Fork Trib8 8.0
END DESCRIPTION:
XS GIS Cut Line= 3
      1439217.85      6945703.37      1439105.00      6944038.00
      1438518.35      6942688.93
#Sta/Elev= 30
  3324.5 1815.84  3490.3 1816.17  3592.0 1815.74  3736.1 1815.88  3911.2 1815.10
  4011.4 1815.46  4141.7 1814.69  4183.5 1814.98  4327.6 1814.28  4471.7 1814.34
  4552.7 1813.74  4743.1 1813.43  4913.5 1811.85  5002.7 1811.59  5003.2 1811.09
  5013.0 1811.09  5013.5 1811.59  5087.7 1812.08  5168.1 1812.21  5311.3 1812.89
  5352.7 1814.27  5381.6 1814.25  5428.5 1813.48  5655.8 1813.96  5661.3 1814.25
  5755.0 1813.92  5912.1 1814.32  5958.9 1813.91  6110.5 1815.13  6464.8 1816.06
#Mann=5,-1,0
  3324.5   0.045       0  5002.7   0.045       0  5013.5   0.045       0
  5087.7    0.07       0  5168.1   0.045       0
Bank Sta=5002.7,5013.5
Exp/Cntr=0.3,0.1

Type RM Length L Ch R = 1,3785,566,566,566
BEGIN DESCRIPTION:
Clear Fork Trib8 7.0
END DESCRIPTION:
XS GIS Cut Line= 3
      1440426.35      6945577.62      1439537.95      6943554.49
      1438643.37      6942619.51
#Sta/Elev= 30
  2790.4 1815.63  3009.5 1815.73  3201.8 1814.43  3423.0 1814.92  3620.0 1813.49
  3678.4 1814.03  3718.3 1812.84  3731.0 1814.01  3748.5 1814.40  3753.9 1815.16
  3771.8 1814.92  3777.3 1811.52  3811.0 1809.42  3811.5 1808.92  3822.3 1809.42
  3838.5 1809.60  3847.4 1810.54  3852.8 1813.98  3870.7 1814.88  3898.6 1814.35
  3946.3 1813.71  4144.0 1814.03  4634.0 1812.79  4672.8 1813.54  4734.0 1812.26
  4963.0 1811.93  5325.1 1812.67  5551.2 1816.29  5636.1 1816.76  6294.0 1816.17
#Mann=7,-1,0
  2790.4   0.045       0  3731.0    0.07       0  3811.0   0.045       0
  3822.3    0.07       0  3898.6   0.045       0  4634.0    0.07       0
  4963.0   0.045       0
Bank Sta=3811,3822.3
Exp/Cntr=0.3,0.1