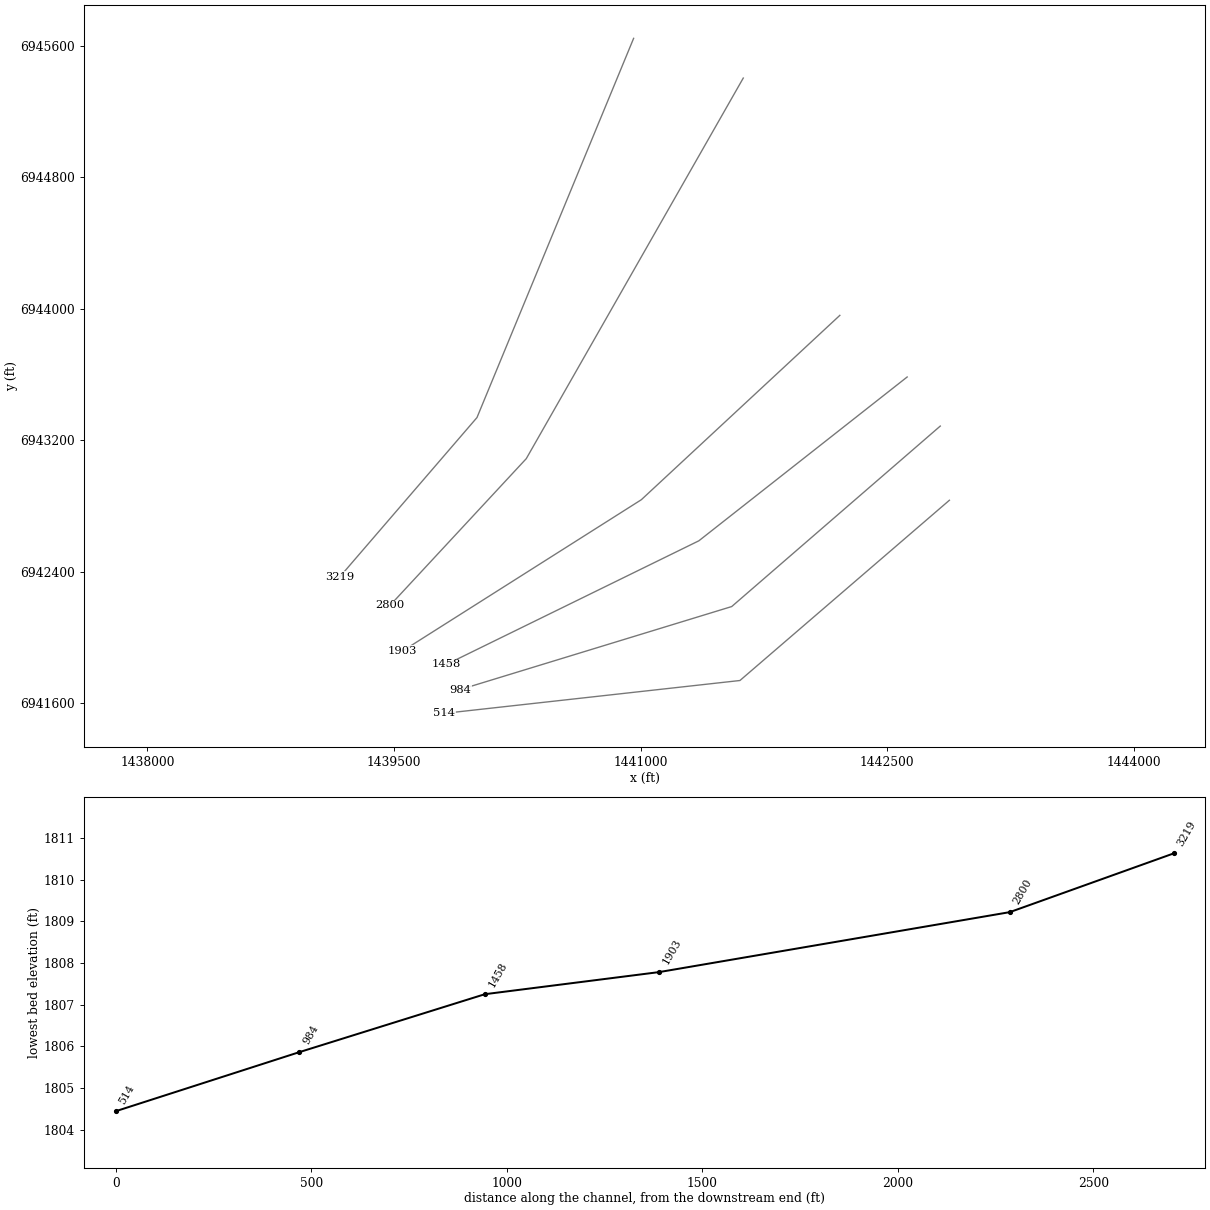
HEC-RAS study Clear Fork Trib8.prj: Clear Fork Trib8 Base Level Engineering

--- Clear Fork Trib8.g01 (geometry) --- (continued)

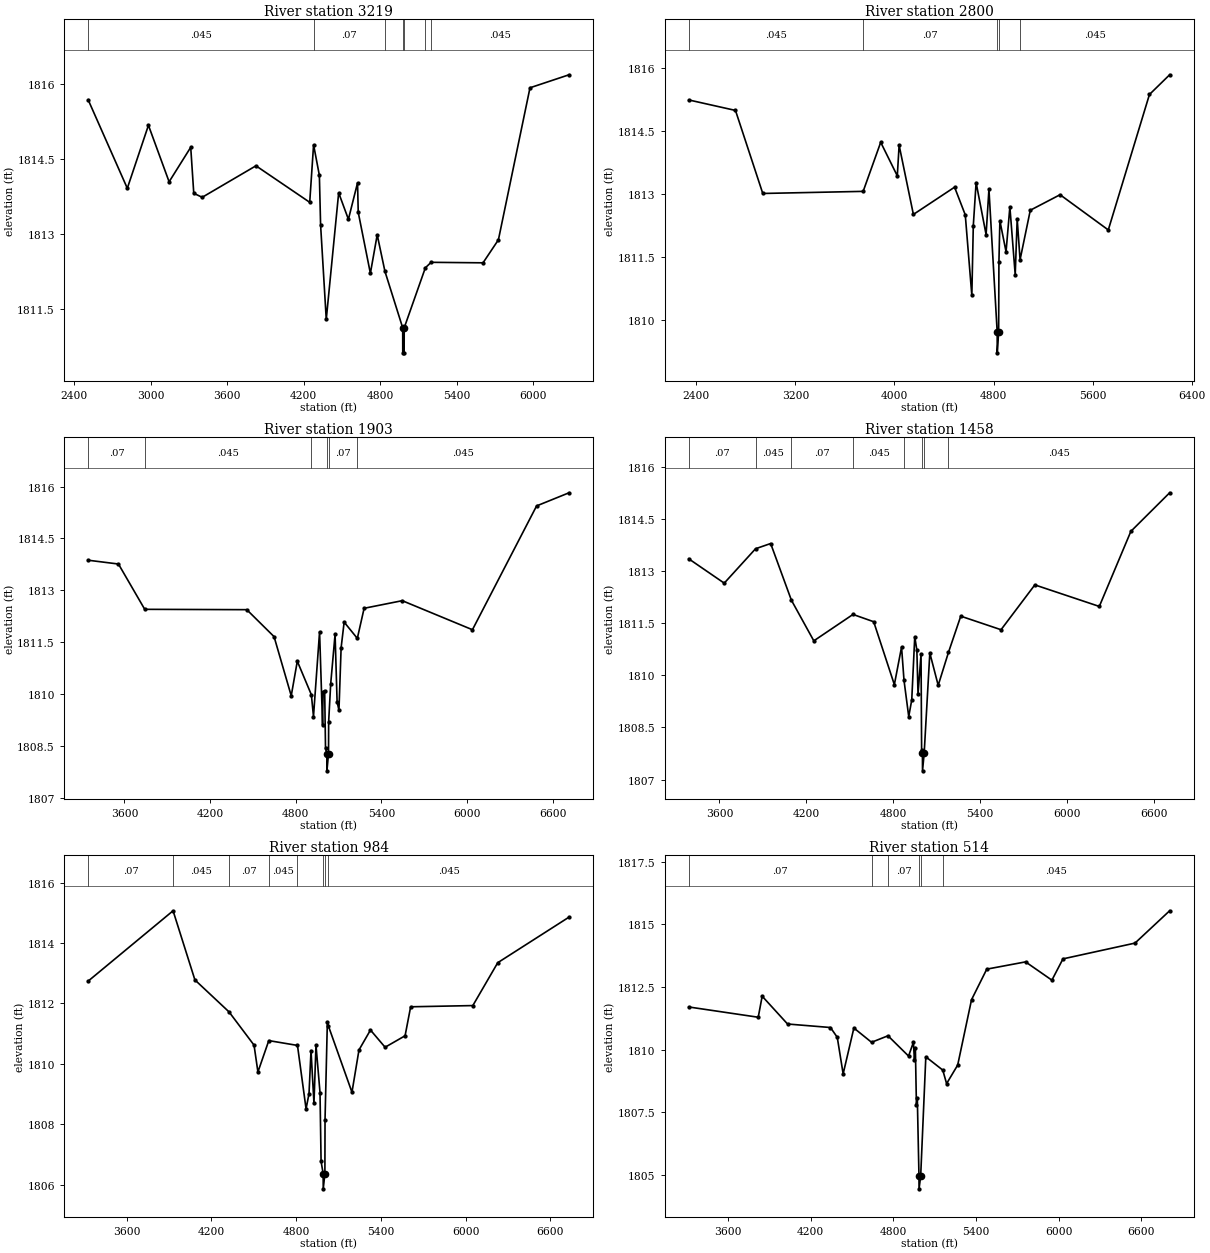
Type RM Length L Ch R = 1,3219,419,419,419
BEGIN DESCRIPTION:
Clear Fork Trib8 6.0
END DESCRIPTION:
XS GIS Cut Line= 3
      1440958.13      6945645.35      1440005.00      6943338.00
      1439171.12      6942369.48
#Sta/Elev= 30
  2507.8 1815.69  2815.2 1813.92  2981.0 1815.18  3143.3 1814.05  3312.9 1814.74
  3336.8 1813.82  3403.0 1813.74  3824.9 1814.37  4246.9 1813.64  4277.2 1814.79
  4322.6 1814.18  4332.2 1813.19  4376.7 1811.30  4474.1 1813.83  4550.6 1813.30
  4622.3 1814.03  4627.7 1813.44  4723.0 1812.22  4776.6 1812.99  4837.2 1812.26
  4976.7 1811.13  4977.2 1810.63  4988.0 1810.63  4988.5 1811.13  5154.4 1812.33
  5199.7 1812.44  5607.2 1812.43  5727.9 1812.89  5975.8 1815.93  6282.3 1816.19
#Mann=7,-1,0
  2507.8   0.045       0  4277.2    0.07       0  4837.2   0.045       0
  4976.7   0.045       0  4988.5   0.045       0  5154.4    0.07       0
  5199.7   0.045       0
Bank Sta=4976.7,4988.5
Exp/Cntr=0.3,0.1

Type RM Length L Ch R = 1,2800,897,897,897
BEGIN DESCRIPTION:
Clear Fork Trib8 5.0
END DESCRIPTION:
XS GIS Cut Line= 3
      1441625.24      6945403.65      1440305.00      6943088.00
      1439476.71      6942195.91
#Sta/Elev= 30
  2338.8 1815.25  2716.1 1815.00  2936.5 1813.02  3747.0 1813.07  3888.7 1814.24
  4022.7 1813.44  4037.4 1814.17  4152.6 1812.52  4485.1 1813.17  4571.5 1812.51
  4624.5 1810.59  4636.3 1812.25  4659.0 1813.28  4739.6 1812.04  4762.6 1813.12
  4829.2 1809.72  4829.7 1809.22  4841.0 1809.72  4843.2 1811.38  4851.0 1812.37
  4900.8 1811.63  4931.6 1812.70  4974.8 1811.08  4990.7 1812.41  5014.0 1811.44
  5096.5 1812.62  5336.9 1812.99  5726.3 1812.15  6058.6 1815.38  6221.7 1815.85
#Mann=5,-1,0
  2338.8   0.045       0  3747.0    0.07       0  4829.2    0.07       0
  4841.0    0.07       0  5014.0   0.045       0
Bank Sta=4829.2,4841
Exp/Cntr=0.3,0.1

Type RM Length L Ch R = 1,1903,445,445,445
BEGIN DESCRIPTION:
Clear Fork Trib8 4.0
END DESCRIPTION:
XS GIS Cut Line= 3
      1442212.84      6943959.81      1441005.00      6942838.00
      1439553.11      6941918.13
#Sta/Elev= 30
  3346.0 1813.87  3558.2 1813.76  3742.2 1812.45  4456.7 1812.44  4647.8 1811.66
  4768.0 1809.95  4810.5 1810.95  4909.0 1809.98  4923.8 1809.35  4966.4 1811.80
  4987.4 1809.11  4991.0 1810.06  5002.1 1810.10  5008.0 1808.43  5017.4 1808.28
  5017.9 1807.78  5029.2 1808.28  5030.0 1809.20  5044.4 1810.30  5075.0 1811.73
  5089.1 1809.78  5102.1 1809.53  5117.3 1811.34  5138.5 1812.08  5230.8 1811.61
  5278.3 1812.48  5545.3 1812.70  6036.8 1811.86  6486.0 1815.44  6713.2 1815.82
#Mann=6,-1,0
  3346.0    0.07       0  3742.2   0.045       0  4909.0    0.07       0
  5017.4    0.07       0  5029.2    0.07       0  5230.8   0.045       0
Bank Sta=5017.4,5029.2
Exp/Cntr=0.3,0.1

Type RM Length L Ch R = 1,1458,474,474,474
BEGIN DESCRIPTION:
Clear Fork Trib8 3.0
END DESCRIPTION:
XS GIS Cut Line= 3
      1442622.53      6943584.78      1441355.00      6942588.00
      1439818.48      6941835.52
#Sta/Elev= 30
  3387.7 1813.35  3632.9 1812.65  3849.4 1813.64  3953.7 1813.79  4097.0 1812.16
  4252.0 1810.99  4522.8 1811.75  4665.8 1811.54  4808.6 1809.73  4858.3 1810.81
  4875.4 1809.85  4908.0 1808.81  4928.8 1809.29  4949.6 1811.11  4964.1 1810.72
  4972.2 1809.46  4993.0 1810.60  4997.0 1807.84  5002.7 1807.75  5003.2 1807.25
  5014.6 1807.75  5053.7 1810.64  5111.6 1809.71  5182.7 1810.66  5267.5 1811.70
  5545.8 1811.31  5779.4 1812.60  6225.0 1811.98  6443.1 1814.14  6711.1 1815.25
#Mann=8,-1,0
  3387.7    0.07       0  3849.4   0.045       0  4097.0    0.07       0
  4522.8   0.045       0  4875.4    0.07       0  5002.7    0.07       0
  5014.6    0.07       0  5182.7   0.045       0
Bank Sta=5002.7,5014.6
Exp/Cntr=0.3,0.1

Type RM Length L Ch R = 1,984,470,470,470
BEGIN DESCRIPTION:
Clear Fork Trib8 2.0
END DESCRIPTION:
XS GIS Cut Line= 3
      1442823.89      6943286.14      1441555.00      6942188.00
      1439901.95      6941682.51
#Sta/Elev= 30
  3326.4 1812.74  3928.0 1815.07  4082.7 1812.78  4324.6 1811.72  4501.6 1810.62
  4529.1 1809.73  4606.1 1810.77  4809.3 1810.61  4870.1 1808.51  4891.0 1809.01
  4905.2 1810.44  4926.1 1808.69  4940.4 1810.62  4968.9 1809.05  4976.5 1806.77
  4991.3 1806.36  4991.8 1805.86  5003.5 1806.36  5004.5 1808.15  5020.9 1811.38
  5028.7 1811.25  5195.3 1809.06  5245.0 1810.46  5326.4 1811.12  5430.0 1810.55
  5571.6 1810.93  5611.0 1811.89  6051.5 1811.93  6228.0 1813.35  6733.1 1814.86
#Mann=8,-1,0
  3326.4    0.07       0  3928.0   0.045       0  4324.6    0.07       0
  4606.1   0.045       0  4809.3    0.07       0  4991.3    0.07       0
  5003.5    0.07       0  5028.7   0.045       0
Bank Sta=4991.3,5003.5
Exp/Cntr=0.3,0.1

Type RM Length L Ch R = 1,514,0,0,0
BEGIN DESCRIPTION:
Clear Fork Trib8 1.0
END DESCRIPTION:
XS GIS Cut Line= 3
      1442879.47      6942834.78      1441605.00      6941738.00
      1439805.01      6941538.00
#Sta/Elev= 30
  3313.7 1811.70  3818.3 1811.29  3846.9 1812.13  4031.2 1811.02  4342.8 1810.88
  4392.2 1810.49  4435.0 1809.03  4512.9 1810.86  4641.3 1810.29  4760.6 1810.55
  4910.1 1809.74  4945.2 1810.29  4952.9 1809.57  4959.5 1810.08  4967.1 1807.80
  4973.7 1808.05  4985.7 1804.94  4986.2 1804.44  4998.0 1804.94  5035.4 1809.71
  5158.5 1809.18  5186.3 1808.64  5266.8 1809.38  5367.4 1811.99  5478.1 1813.21
  5759.8 1813.50  5951.0 1812.77  6031.5 1813.62  6554.7 1814.25  6806.2 1815.54
#Mann=6,-1,0
  3313.7    0.07       0  4641.3   0.045       0  4760.6    0.07       0
  4985.7    0.07       0  4998.0    0.07       0  5158.5   0.045       0
Bank Sta=4985.7,4998
Exp/Cntr=0.3,0.1

Chan Stop Cuts=-1