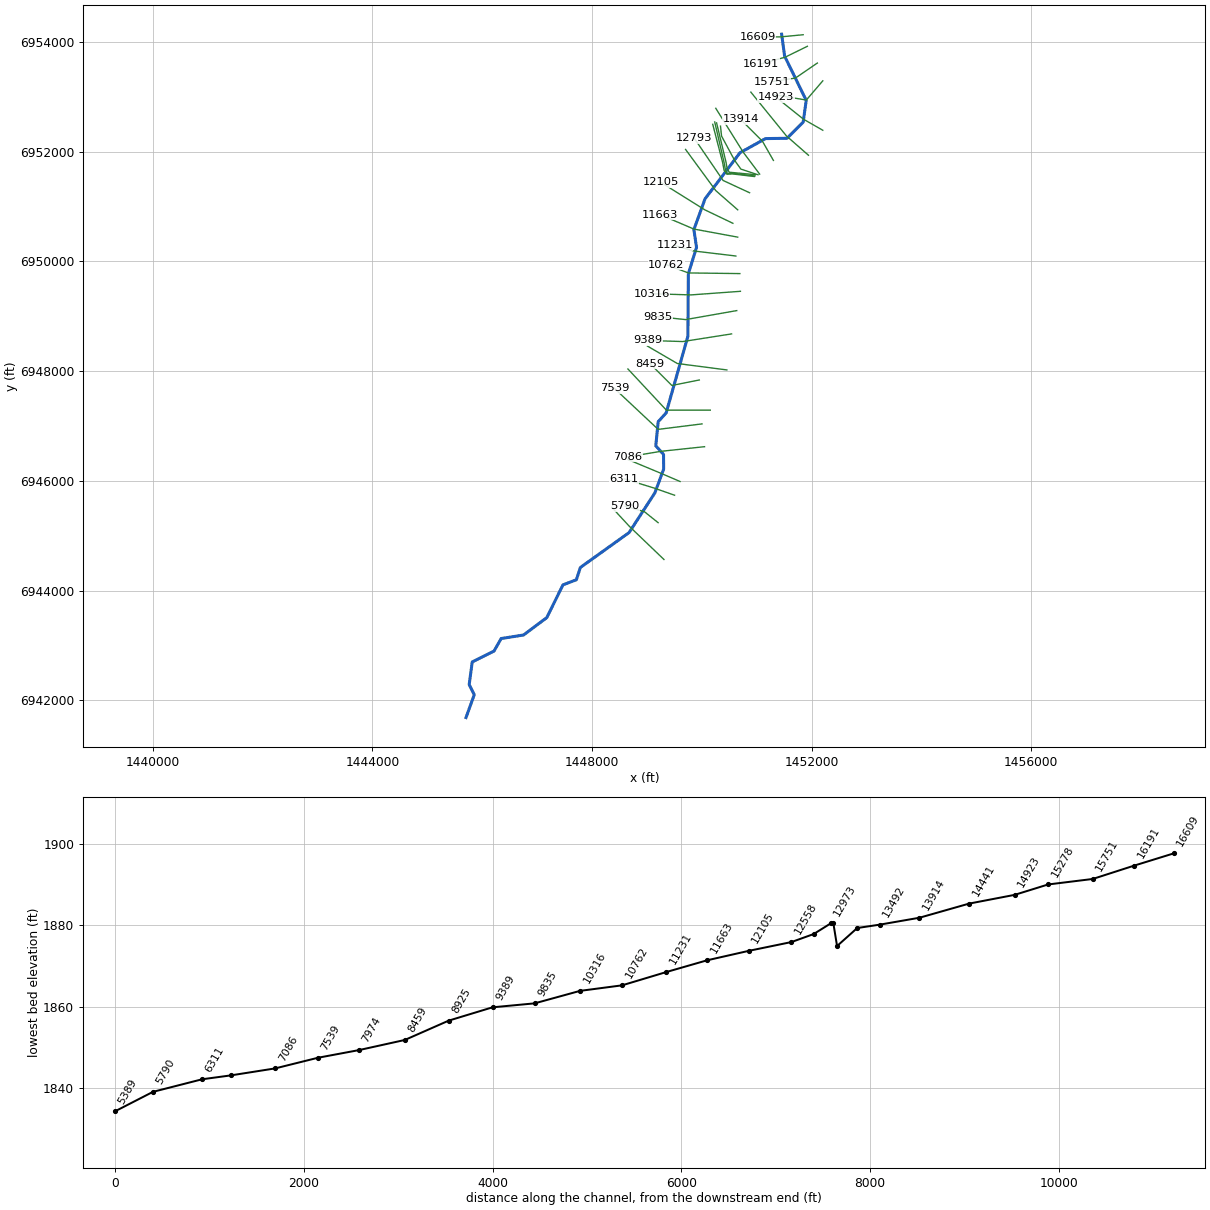
--- Clear Fork Trib9.prj (project) ---

Proj Title=Clear Fork Trib9 Base Level Engineering
Current Plan=p01
Default Exp/Contr=0.3,0.1
English Units
Geom File=g01
Flow File=f01
Plan File=p01
BEGIN DESCRIPTION:
Clear Fork Trib9
END DESCRIPTION:

--- Clear Fork Trib9.p01 (plan) ---

Plan Title=Multiple Run
Short Identifier=Multiple
Geom File=g01
Flow File=f01
Subcritical Flow
K Sum by GR= 0
Std Step Tol= 0.01
Critical Tol= 0.01
Num of Std Step Trials= 20
Max Error Tol= 0.3
Flow Tol Ratio= 0.001
Split Flow NTrial= 30
Split Flow Tol= 0.02
Split Flow Ratio= 0.02
Log Output Level= 0
Friction Slope Method= 1
Unsteady Friction Slope Method= 2
Unsteady Bridges Friction Slope Method= 1
Parabolic Critical Depth
Global Vel Dist=  1 , 1 , 1
Global Log Level= 0
CheckData=True
Encroach Param= -1, 0, 0, 0
BEGIN DESCRIPTION:
Multiple Run
END DESCRIPTION:

--- Clear Fork Trib9.f01 (steady flow) ---

Flow Title=Multiple
Number of Profiles=7
Profile Names=10-year,25-year,50-year,1pct_min,100-year,1pct_plu,500-year
River Rch & RM= Clear Fork Trib9,Reach-1,16609
     249     346     426     261     521    1039     788
River Rch & RM= Clear Fork Trib9,Reach-1,16191
     420     600     754     470     938    1871    1471
River Rch & RM= Clear Fork Trib9,Reach-1,13492
     537     776     980     615    1227    2448    1946
River Rch & RM= Clear Fork Trib9,Reach-1,6617
     655     956    1217     768    1533    3059    2464
Boundary for River Rch & Prof#=Clear Fork Trib9,Reach-1,1
Up Type=0
Dn Type=3
Dn Slope=0.005
Boundary for River Rch & Prof#=Clear Fork Trib9,Reach-1,2
Up Type=0
Dn Type=3
Dn Slope=0.005
Boundary for River Rch & Prof#=Clear Fork Trib9,Reach-1,3
Up Type=0
Dn Type=3
Dn Slope=0.005
Boundary for River Rch & Prof#=Clear Fork Trib9,Reach-1,4
Up Type=0
Dn Type=3
Dn Slope=0.005
Boundary for River Rch & Prof#=Clear Fork Trib9,Reach-1,5
Up Type=0
Dn Type=3
Dn Slope=0.005
Boundary for River Rch & Prof#=Clear Fork Trib9,Reach-1,6
Up Type=0
Dn Type=3
Dn Slope=0.005
Boundary for River Rch & Prof#=Clear Fork Trib9,Reach-1,7
Up Type=0
Dn Type=3
Dn Slope=0.005

--- Clear Fork Trib9.g01 (geometry) ---

Geom Title=Existing Conditions

River Reach=Clear Fork Trib9,Reach-1
Reach XY= 30
      1451455.00      6954138.00      1451508.83      6953739.58
      1451902.95      6952932.14      1451847.01      6952534.66
      1451553.37      6952241.13      1451160.94      6952235.74
      1450695.30      6951977.23      1450058.53      6951136.55
      1449856.20      6950577.49      1449904.51      6950253.22
      1449755.25      6949772.78      1449747.18      6948634.58
      1449351.46      6947239.46      1449205.65      6947077.36
      1449162.32      6946637.90      1449303.38      6946481.97
      1449305.41      6946213.00      1449145.68      6945781.34
      1448675.93      6945057.93      1447787.86      6944421.55
      1447715.16      6944198.36      1447471.49      6944105.05
      1447175.98      6943507.79      1446753.50      6943191.62
      1446344.63      6943126.92      1446214.71      6942898.75
      1445818.37      6942701.32      1445762.33      6942287.90
      1445854.64      6942103.27      1445705.00      6941688.00

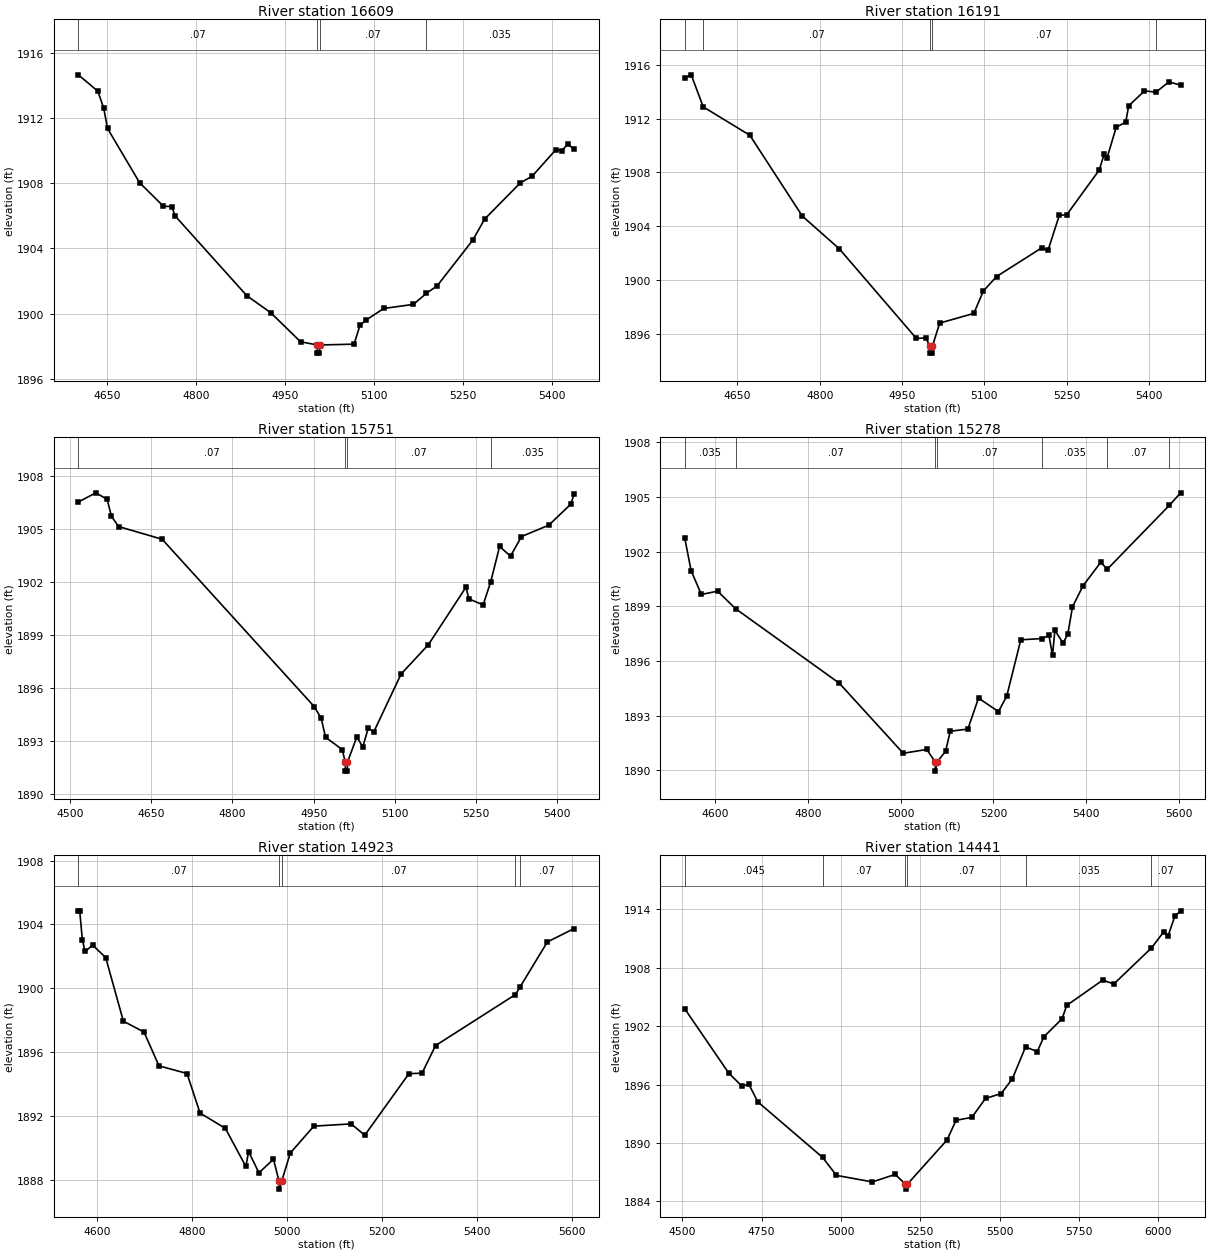
Type RM Length L Ch R = 1,16609,418,418,418
BEGIN DESCRIPTION:
Clear Fork Trib9 32.0
END DESCRIPTION:
XS GIS Cut Line= 3
      1451847.64      6954127.79      1451430.00      6954088.00
      1451014.23      6954088.72
#Sta/Elev= 30
  4601.8 1914.64  4634.6 1913.64  4644.6 1912.59  4651.0 1911.35  4704.9 1908.03
  4745.1 1906.58  4758.9 1906.56  4765.2 1905.97  4885.7 1901.09  4925.9 1900.05
  4976.1 1898.27  5004.3 1898.07  5004.5 1897.57  5008.0 1897.57  5008.3 1898.07
  5066.3 1898.12  5076.3 1899.28  5086.3 1899.59  5116.3 1900.31  5166.3 1900.56
  5188.2 1901.24  5206.3 1901.70  5266.3 1904.50  5286.3 1905.79  5346.3 1908.01
  5366.3 1908.42  5406.3 1910.05  5416.3 1909.99  5426.3 1910.39  5437.1 1910.08
#Mann=4,-1,0
  4601.8    0.07       0  5004.3    0.07       0  5008.3    0.07       0
  5188.2   0.035       0
Bank Sta=5004.3,5008.3
Exp/Cntr=0.3,0.1

Type RM Length L Ch R = 1,16191,440,440,440
BEGIN DESCRIPTION:
Mapping XS 28c0181d
END DESCRIPTION:
XS GIS Cut Line= 3
      1451923.14      6953916.86      1451519.47      6953718.93
      1451081.95      6953596.53
#Sta/Elev= 30
  4554.0 1915.02  4565.7 1915.25  4587.6 1912.87  4672.6 1910.76  4768.2 1904.76
  4835.6 1902.33  4976.2 1895.67  4993.1 1895.71  5001.3 1895.08  5001.5 1894.58
  5005.0 1894.58  5005.3 1895.08  5018.6 1896.81  5080.9 1897.53  5098.2 1899.19
  5122.4 1900.27  5205.5 1902.42  5216.1 1902.21  5236.7 1904.81  5250.3 1904.86
  5309.4 1908.17  5318.5 1909.35  5323.7 1909.07  5340.5 1911.36  5357.9 1911.74
  5363.1 1912.94  5392.0 1914.06  5413.1 1913.96  5436.5 1914.73  5457.9 1914.48
#Mann=5,-1,0
  4554.0   0.035       0  4587.6    0.07       0  5001.3    0.07       0
  5005.3    0.07       0  5413.1   0.035       0
Bank Sta=5001.3,5005.3
Exp/Cntr=0.3,0.1

Type RM Length L Ch R = 1,15751,473,473,473
BEGIN DESCRIPTION:
Clear Fork Trib9 31.0
END DESCRIPTION:
XS GIS Cut Line= 3
      1452105.42      6953612.17      1451705.00      6953338.00
      1451278.69      6953273.83
#Sta/Elev= 30
  4515.1 1906.55  4547.5 1907.07  4568.4 1906.70  4576.2 1905.75  4589.4 1905.16
  4670.0 1904.44  4951.0 1894.96  4964.0 1894.29  4972.0 1893.22  5002.9 1892.52
  5008.5 1891.80  5008.7 1891.30  5012.2 1891.30  5012.5 1891.80  5029.8 1893.24
  5040.8 1892.67  5050.9 1893.73  5061.1 1893.52  5111.6 1896.80  5162.2 1898.47
  5231.7 1901.73  5236.8 1901.06  5263.3 1900.72  5277.4 1902.04  5293.7 1904.03
  5313.9 1903.48  5334.1 1904.59  5384.7 1905.24  5425.1 1906.42  5431.5 1907.01
#Mann=4,-1,0
  4515.1    0.07       0  5008.5    0.07       0  5012.5    0.07       0
  5277.4   0.035       0
Bank Sta=5008.5,5012.5
Exp/Cntr=0.3,0.1

Type RM Length L Ch R = 1,15278,355,355,355
BEGIN DESCRIPTION:
Clear Fork Trib9 30.0
END DESCRIPTION:
XS GIS Cut Line= 3
      1452205.02      6953288.02      1451905.00      6952938.00
      1451304.98      6953038.00
#Sta/Elev= 30
  4534.3 1902.73  4548.0 1900.95  4570.0 1899.65  4605.1 1899.83  4644.2 1898.86
  4867.4 1894.78  5005.4 1890.93  5056.1 1891.14  5074.4 1890.45  5074.7 1889.95
  5078.4 1890.45  5096.7 1891.04  5106.8 1892.14  5144.8 1892.26  5167.7 1893.96
  5210.7 1893.22  5228.5 1894.06  5258.9 1897.16  5304.8 1897.23  5319.7 1897.40
  5327.3 1896.31  5332.4 1897.68  5350.1 1896.98  5360.3 1897.47  5370.4 1898.97
  5393.2 1900.13  5431.2 1901.41  5445.5 1901.04  5579.6 1904.55  5603.6 1905.23
#Mann=7,-1,0
  4534.3   0.035       0  4644.2    0.07       0  5074.4    0.07       0
  5078.4    0.07       0  5304.8   0.035       0  5445.5    0.07       0
  5579.6   0.035       0
Bank Sta=5074.4,5078.4
Exp/Cntr=0.3,0.1

Type RM Length L Ch R = 1,14923,482,482,482
BEGIN DESCRIPTION:
Clear Fork Trib9 29.0
END DESCRIPTION:
XS GIS Cut Line= 3
      1452205.01      6952387.47      1451855.00      6952587.48
      1451355.03      6952987.46
#Sta/Elev= 30
  4560.9 1904.85  4563.8 1904.85  4569.4 1903.03  4575.1 1902.30  4591.0 1902.70
  4618.5 1901.92  4655.7 1897.93  4699.1 1897.25  4730.6 1895.13  4789.6 1894.65
  4817.0 1892.17  4870.3 1891.21  4913.4 1888.82  4919.2 1889.75  4941.0 1888.42
  4971.6 1889.28  4983.2 1887.90  4983.7 1887.40  4988.9 1887.90  5006.9 1889.66
  5056.5 1891.35  5134.9 1891.49  5163.7 1890.78  5256.6 1894.64  5284.2 1894.67
  5312.6 1896.40  5480.7 1899.60  5490.2 1900.06  5547.9 1902.90  5604.3 1903.74
#Mann=5,-1,0
  4560.9    0.07       0  4983.2    0.07       0  4988.9    0.07       0
  5480.7   0.035       0  5490.2    0.07       0
Bank Sta=4983.2,4988.9
Exp/Cntr=0.3,0.1

Type RM Length L Ch R = 1,14441,527,527,527
BEGIN DESCRIPTION:
Clear Fork Trib9 28.0
END DESCRIPTION:
XS GIS Cut Line= 3
      1451944.07      6951932.26      1451544.06      6952282.27
      1450894.06      6953082.28
#Sta/Elev= 30
  4508.0 1903.77  4646.0 1897.20  4688.7 1895.81  4709.6 1896.04  4738.1 1894.22
  4942.1 1888.52  4985.8 1886.67  5099.2 1886.00  5171.1 1886.77  5203.4 1885.76
  5203.8 1885.26  5209.1 1885.76  5334.1 1890.30  5362.8 1892.33  5412.4 1892.63
  5455.5 1894.57  5505.1 1895.08  5540.3 1896.60  5581.6 1899.86  5618.6 1899.39
  5639.6 1900.91  5696.9 1902.76  5711.2 1904.12  5824.7 1906.72  5859.9 1906.33
  5978.5 1910.03  6016.5 1911.66  6030.9 1911.28  6051.9 1913.27  6070.3 1913.84
#Mann=6,-1,0
  4508.0   0.045       0  4942.1    0.07       0  5203.4    0.07       0
  5209.1    0.07       0  5581.6   0.035       0  5978.5    0.07       0
Bank Sta=5203.4,5209.1
Exp/Cntr=0.3,0.1

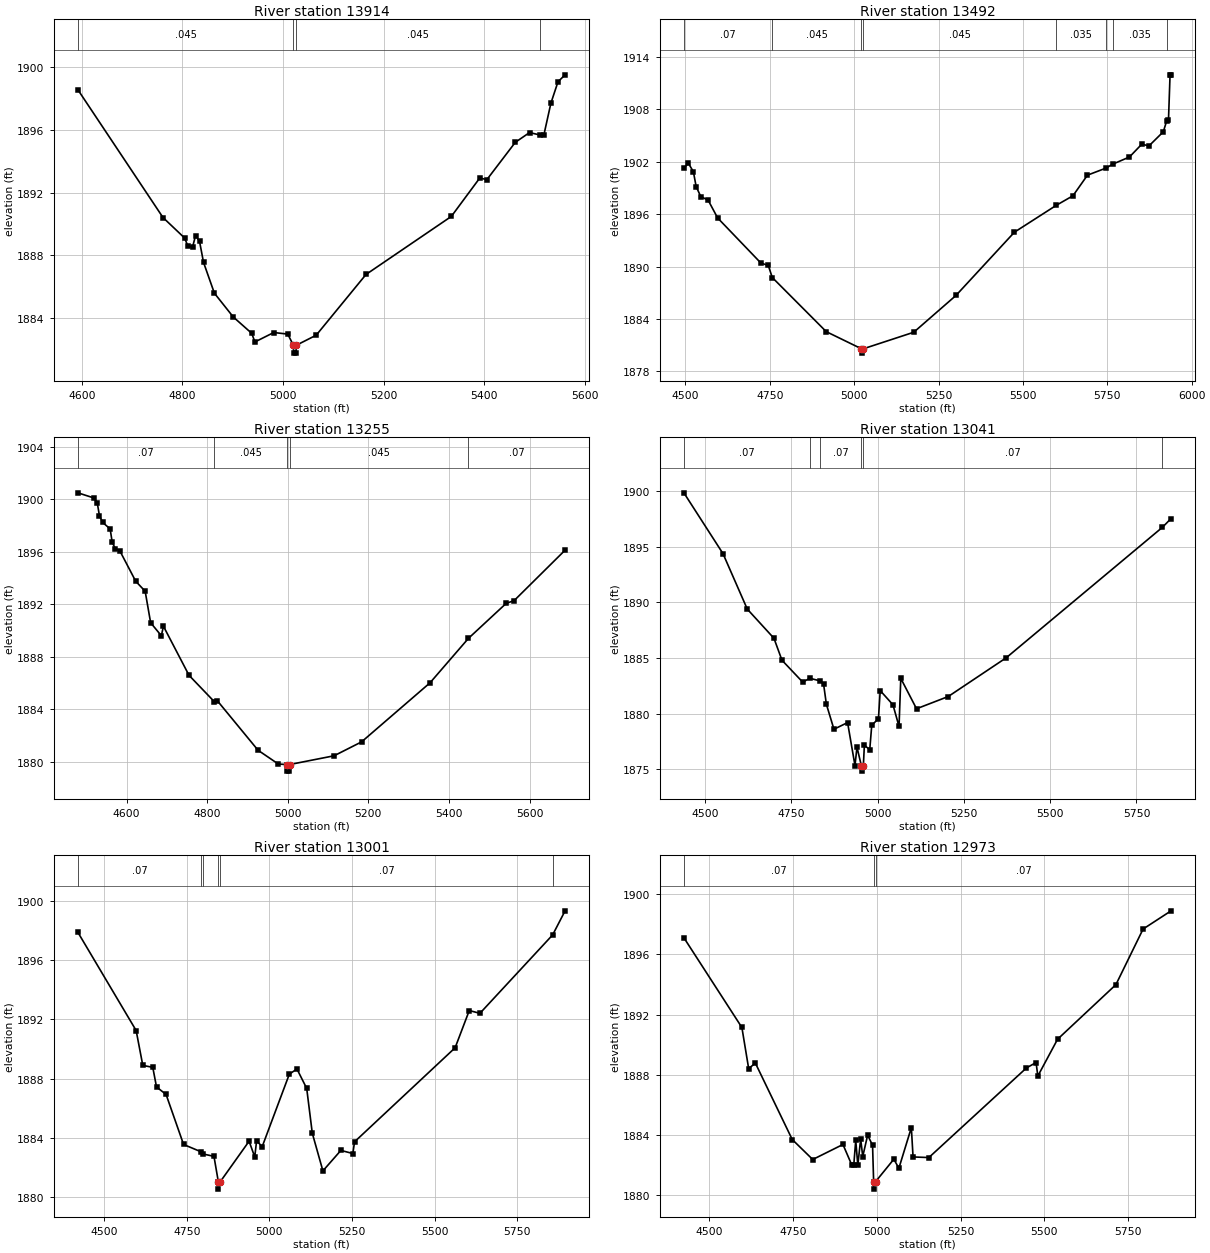
Type RM Length L Ch R = 1,13914,422,422,422
BEGIN DESCRIPTION:
Clear Fork Trib9 27.0
END DESCRIPTION:
XS GIS Cut Line= 3
      1451305.02      6951837.96      1451105.00      6952188.00
      1450705.03      6952587.97
#Sta/Elev= 30
  4592.2 1898.53  4761.4 1890.41  4804.6 1889.10  4811.1 1888.57  4820.4 1888.56
  4826.2 1889.26  4834.1 1888.89  4842.0 1887.56  4863.6 1885.60  4901.1 1884.09
  4937.8 1883.05  4944.2 1882.50  4981.7 1883.10  5009.5 1883.00  5020.7 1882.29
  5021.2 1881.79  5026.0 1881.79  5026.5 1882.29  5066.1 1882.93  5165.1 1886.79
  5334.8 1890.48  5391.3 1892.92  5405.5 1892.82  5462.0 1895.19  5490.3 1895.81
  5511.8 1895.65  5518.6 1895.63  5532.8 1897.68  5546.9 1899.04  5561.0 1899.48
#Mann=4,-1,0
  4592.2   0.045       0  5020.7   0.045       0  5026.5   0.045       0
  5511.8    0.07       0
Bank Sta=5020.7,5026.5
Exp/Cntr=0.3,0.1

Type RM Length L Ch R = 1,13492,237,237,237
BEGIN DESCRIPTION:
Clear Fork Trib9 26.0
END DESCRIPTION:
XS GIS Cut Line= 3
      1451054.98      6951588.03      1450755.00      6951988.00
      1450254.98      6952788.03
#Sta/Elev= 30
  4495.6 1901.31  4509.1 1901.82  4523.7 1900.87  4532.0 1899.16  4545.6 1898.02
  4567.4 1897.61  4595.6 1895.57  4723.7 1890.41  4745.6 1890.13  4757.5 1888.75
  4917.4 1882.55  5021.6 1880.59  5022.0 1880.09  5027.4 1880.59  5176.6 1882.48
  5301.6 1886.69  5474.9 1893.94  5599.5 1897.03  5648.3 1898.11  5691.3 1900.47
  5745.6 1901.27  5766.7 1901.74  5815.7 1902.55  5852.3 1904.02  5873.5 1903.82
  5916.0 1905.44  5925.9 1906.67  5931.3 1906.75  5936.0 1911.96  5939.0 1911.96
#Mann=8,-1,0
  4495.6    0.07       0  4757.5   0.045       0  5021.6   0.045       0
  5027.4   0.045       0  5599.5   0.035       0  5745.6    0.07       0
  5766.7   0.035       0  5925.9    0.07       0
Bank Sta=5021.6,5027.4
Exp/Cntr=0.3,0.1

Type RM Length L Ch R = 1,13255,214,214,214
BEGIN DESCRIPTION:
Mapping XS 84e8de8c
END DESCRIPTION:
XS GIS Cut Line= 5
      1451023.49      6951577.15      1450712.68      6951679.60
      1450598.10      6951839.32      1450360.25      6952282.03
      1450341.22      6952463.65
#Sta/Elev= 30
  4479.2 1900.48  4519.7 1900.08  4527.4 1899.68  4532.7 1898.73  4540.8 1898.22
  4559.2 1897.73  4564.4 1896.70  4572.4 1896.21  4582.9 1896.08  4622.7 1893.74
  4646.1 1892.98  4659.7 1890.58  4686.2 1889.59  4691.5 1890.31  4755.0 1886.57
  4817.5 1884.57  4825.6 1884.62  4926.3 1880.86  4976.6 1879.81  4998.4 1879.77
  4998.9 1879.27  5003.8 1879.27  5004.3 1879.77  5115.0 1880.44  5183.2 1881.50
  5353.0 1886.00  5448.4 1889.39  5541.8 1892.05  5561.9 1892.27  5688.2 1896.11
#Mann=5,-1,0
  4479.2    0.07       0  4817.5   0.045       0  4998.4   0.045       0
  5004.3   0.045       0  5448.4    0.07       0
Bank Sta=4998.4,5004.3
Exp/Cntr=0.3,0.1

Type RM Length L Ch R = 1,13041,40,40,40
BEGIN DESCRIPTION:
Mapping XS 5de1f97a
END DESCRIPTION:
XS GIS Cut Line= 6
      1450977.80      6951578.31      1450563.74      6951617.37
      1450501.24      6951622.58      1450462.18      6951687.68
      1450441.35      6951807.47      1450269.80      6952522.25
#Sta/Elev= 30
  4439.0 1899.84  4552.3 1894.38  4622.6 1889.40  4699.9 1886.78  4723.1 1884.81
  4783.3 1882.84  4803.7 1883.19  4832.6 1882.96  4843.6 1882.68  4851.8 1880.85
  4873.7 1878.61  4913.2 1879.21  4934.6 1875.35  4940.4 1877.00  4953.0 1875.35
  4953.5 1874.85  4958.9 1875.35  4961.8 1877.17  4977.4 1876.78  4983.2 1878.97
  5002.6 1879.56  5007.7 1882.08  5044.6 1880.81  5062.2 1878.86  5067.3 1883.18
  5112.9 1880.45  5204.8 1881.55  5372.8 1885.03  5825.0 1896.74  5850.2 1897.53
#Mann=6,-1,0
  4439.0    0.07       0  4803.7   0.045       0  4832.6    0.07       0
  4953.0    0.07       0  4958.9    0.07       0  5825.0   0.035       0
Bank Sta=4953,4958.9
Exp/Cntr=0.3,0.1

Type RM Length L Ch R = 1,13001,28,28,28
BEGIN DESCRIPTION:
Mapping XS 9e659fef
END DESCRIPTION:
XS GIS Cut Line= 6
      1450969.98      6951554.87      1450561.14      6951604.35
      1450462.18      6951604.35      1450430.93      6951669.45
      1450407.49      6951794.45      1450235.63      6952539.20
#Sta/Elev= 30
  4420.7 1897.86  4597.0 1891.24  4617.1 1888.89  4647.3 1888.76  4658.6 1887.44
  4687.6 1886.93  4740.5 1883.56  4794.1 1883.06  4799.3 1882.92  4832.5 1882.76
  4845.7 1881.05  4846.2 1880.55  4851.6 1881.05  4938.8 1883.78  4955.9 1882.72
  4961.5 1883.80  4978.6 1883.42  5060.6 1888.30  5083.6 1888.65  5113.2 1887.34
  5130.1 1884.32  5162.2 1881.78  5216.6 1883.16  5252.8 1882.95  5258.0 1883.74
  5562.4 1890.08  5605.2 1892.59  5637.4 1892.40  5857.6 1897.69  5895.2 1899.31
#Mann=6,-1,0
  4420.7    0.07       0  4794.1   0.045       0  4799.3    0.07       0
  4845.7    0.07       0  4851.6    0.07       0  5857.6   0.035       0
Bank Sta=4845.7,4851.6
Exp/Cntr=0.3,0.1

Type RM Length L Ch R = 1,12973,180,180,180
BEGIN DESCRIPTION:
Mapping XS 1055b829
END DESCRIPTION:
XS GIS Cut Line= 6
      1450957.02      6951544.45      1450561.14      6951591.33
      1450456.97      6951586.12      1450407.49      6951653.83
      1450378.85      6951804.87      1450199.58      6952495.96
#Sta/Elev= 30
  4423.7 1897.11  4596.9 1891.14  4617.1 1888.41  4637.2 1888.77  4747.2 1883.69
  4808.4 1882.36  4898.6 1883.36  4925.1 1881.99  4930.9 1881.99  4936.8 1883.63
  4943.0 1881.97  4951.5 1883.72  4957.7 1882.56  4972.3 1883.98  4987.0 1883.31
  4990.2 1880.89  4990.7 1880.39  4996.1 1880.89  5050.5 1882.38  5065.6 1881.78
  5102.8 1884.48  5107.9 1882.53  5155.1 1882.49  5446.4 1888.45  5475.2 1888.81
  5480.4 1887.91  5539.4 1890.36  5713.5 1893.99  5794.7 1897.69  5878.2 1898.90
#Mann=3,-1,0
  4423.7    0.07       0  4990.2    0.07       0  4996.1    0.07       0
Bank Sta=4990.2,4996.1
Exp/Cntr=0.3,0.1

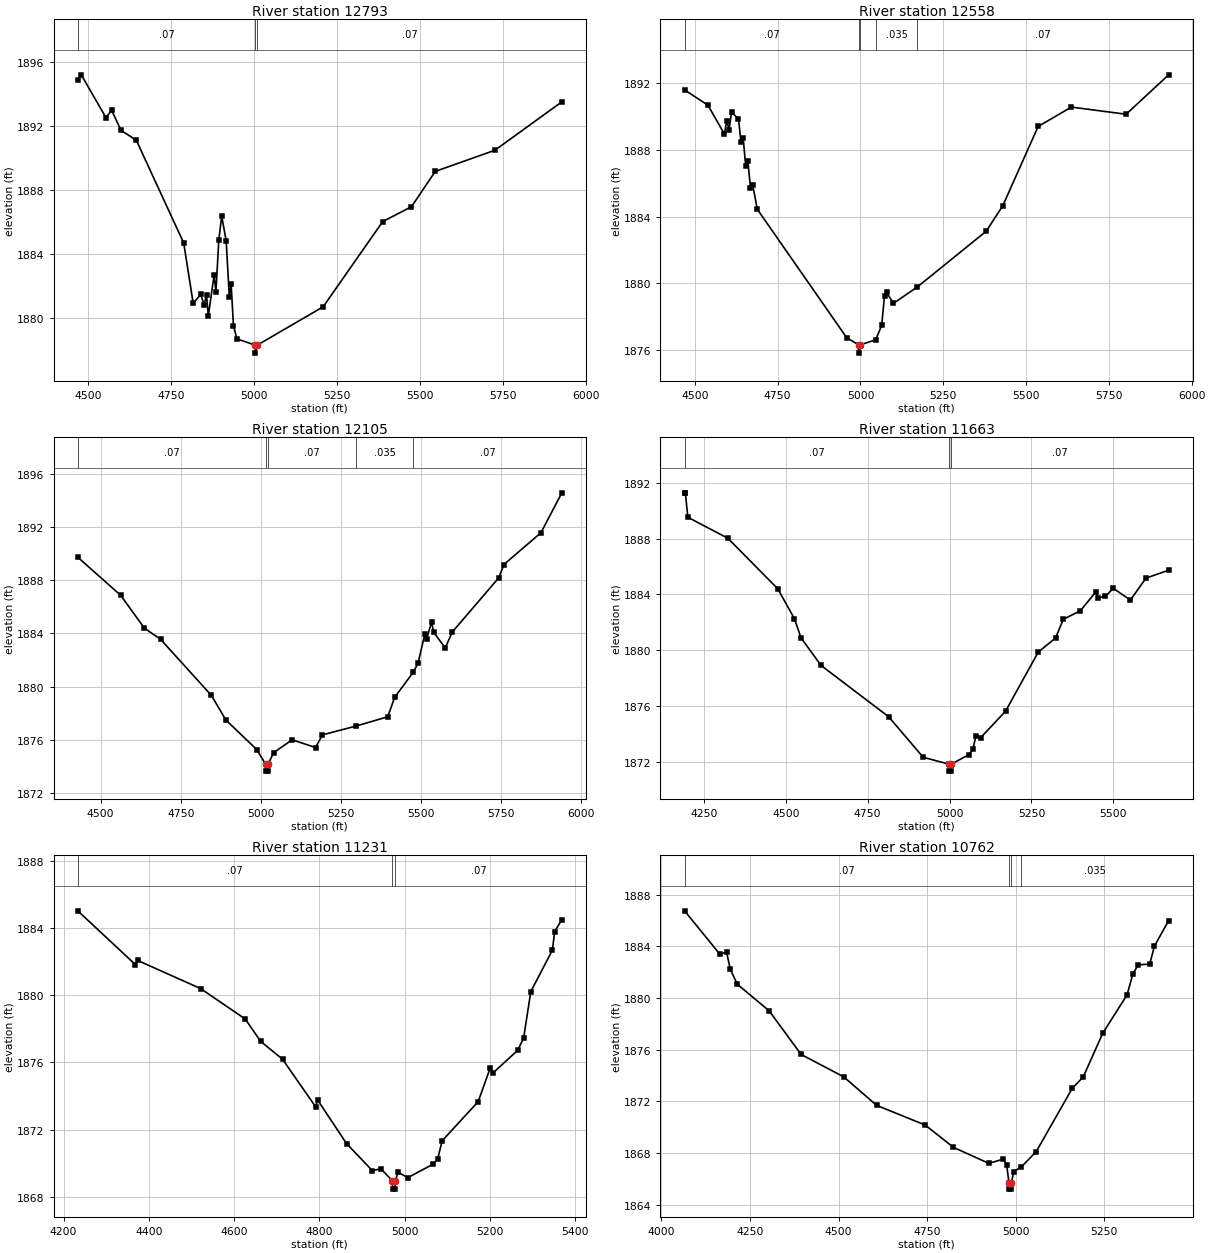
Type RM Length L Ch R = 1,12793,235,235,235
BEGIN DESCRIPTION:
Mapping XS 14eb7324
END DESCRIPTION:
XS GIS Cut Line= 3
      1450870.71      6951249.03      1450388.03      6951473.00
      1449865.44      6952238.65
#Sta/Elev= 30
  4469.5 1894.90  4480.1 1895.20  4554.3 1892.53  4571.7 1892.98  4600.1 1891.72
  4646.0 1891.11  4788.9 1884.68  4817.5 1880.90  4840.2 1881.47  4850.6 1880.80
  4857.6 1881.43  4863.1 1880.12  4880.5 1882.68  4886.0 1881.61  4894.7 1884.87
  4903.4 1886.35  4916.8 1884.83  4926.3 1881.33  4931.8 1882.10  4938.8 1879.51
  4949.2 1878.68  5004.7 1878.29  5005.2 1877.79  5010.6 1878.29  5209.2 1880.69
  5388.7 1886.02  5475.4 1886.95  5547.2 1889.16  5726.7 1890.48  5928.6 1893.51
#Mann=3,-1,0
  4469.5    0.07       0  5004.7    0.07       0  5010.6    0.07       0
Bank Sta=5004.7,5010.6
Exp/Cntr=0.3,0.1

Type RM Length L Ch R = 1,12558,453,453,453
BEGIN DESCRIPTION:
Clear Fork Trib9 24.0
END DESCRIPTION:
XS GIS Cut Line= 3
      1450655.02      6950937.98      1450255.00      6951288.00
      1449704.99      6952038.01
#Sta/Elev= 30
  4468.9 1891.59  4539.6 1890.67  4589.0 1888.95  4596.6 1889.74  4603.2 1889.21
  4610.8 1890.24  4631.7 1889.86  4639.3 1888.48  4645.9 1888.72  4653.5 1887.03
  4660.2 1887.31  4667.8 1885.74  4674.4 1885.92  4688.6 1884.44  4958.2 1876.76
  4994.1 1876.33  4994.6 1875.83  5000.1 1876.33  5046.1 1876.63  5064.1 1877.49
  5072.6 1879.26  5078.8 1879.46  5099.6 1878.81  5171.7 1879.79  5379.8 1883.13
  5429.9 1884.66  5536.5 1889.40  5636.8 1890.56  5802.0 1890.13  5930.5 1892.49
#Mann=5,-1,0
  4468.9    0.07       0  4994.1    0.07       0  5000.1    0.07       0
  5046.1   0.035       0  5171.7    0.07       0
Bank Sta=4994.1,5000.1
Exp/Cntr=0.3,0.1

Type RM Length L Ch R = 1,12105,442,442,442
BEGIN DESCRIPTION:
Clear Fork Trib9 23.0
END DESCRIPTION:
XS GIS Cut Line= 3
      1450566.31      6950692.91      1450055.00      6950938.00
      1449255.01      6951437.99
#Sta/Elev= 30
  4428.8 1889.72  4562.8 1886.86  4636.3 1884.41  4687.2 1883.56  4845.8 1879.35
  4891.1 1877.50  4987.3 1875.29  5015.5 1874.17  5016.0 1873.67  5021.7 1873.67
  5022.2 1874.17  5040.0 1875.06  5097.8 1876.02  5170.9 1875.44  5192.2 1876.39
  5298.4 1877.06  5396.2 1877.75  5417.4 1879.20  5475.3 1881.08  5490.5 1881.76
  5511.7 1883.96  5517.6 1883.62  5533.0 1884.86  5538.9 1884.10  5575.4 1882.91
  5597.2 1884.10  5742.9 1888.19  5758.2 1889.17  5873.8 1891.55  5939.2 1894.55
#Mann=5,-1,0
  4428.8    0.07       0  5015.5    0.07       0  5022.2    0.07       0
  5298.4   0.035       0  5475.3    0.07       0
Bank Sta=5015.5,5022.2
Exp/Cntr=0.3,0.1

Type RM Length L Ch R = 1,11663,432,432,432
BEGIN DESCRIPTION:
Clear Fork Trib9 22.0
END DESCRIPTION:
XS GIS Cut Line= 3
      1450654.92      6950440.28      1449855.00      6950588.00
      1449243.46      6950849.13
#Sta/Elev= 30
  4190.8 1891.28  4193.3 1891.28  4200.8 1889.53  4322.9 1888.03  4475.4 1884.41
  4526.3 1882.27  4546.6 1880.89  4607.6 1878.92  4813.8 1875.25  4919.7 1872.34
  4998.3 1871.85  4998.8 1871.35  5004.6 1871.35  5005.1 1871.85  5058.6 1872.52
  5071.4 1872.91  5080.4 1873.85  5095.0 1873.74  5171.3 1875.65  5271.1 1879.88
  5323.8 1880.88  5347.4 1882.22  5400.0 1882.84  5447.2 1884.20  5452.7 1883.77
  5476.3 1883.86  5499.9 1884.44  5552.5 1883.60  5599.8 1885.17  5669.2 1885.74
#Mann=3,-1,0
  4190.8    0.07       0  4998.3    0.07       0  5005.1    0.07       0
Bank Sta=4998.3,5005.1
Exp/Cntr=0.3,0.1

Type RM Length L Ch R = 1,11231,469,469,469
BEGIN DESCRIPTION:
Clear Fork Trib9 21.0
END DESCRIPTION:
XS GIS Cut Line= 3
      1450621.05      6950096.53      1449855.00      6950188.00
      1449505.00      6950288.00
#Sta/Elev= 30
  4233.3 1885.01  4368.7 1881.81  4373.8 1882.06  4521.4 1880.39  4626.2 1878.58
  4662.4 1877.25  4713.7 1876.19  4791.1 1873.37  4796.1 1873.76  4863.8 1871.18
  4924.2 1869.57  4944.4 1869.68  4971.2 1868.97  4971.7 1868.47  4977.5 1868.47
  4978.0 1868.97  4984.7 1869.47  5007.4 1869.15  5067.2 1869.96  5077.6 1870.27
  5088.0 1871.34  5172.5 1873.67  5201.1 1875.69  5206.3 1875.35  5264.8 1876.71
  5279.1 1877.44  5296.0 1880.21  5346.7 1882.68  5351.9 1883.78  5368.8 1884.48
#Mann=3,-1,0
  4233.3    0.07       0  4971.2    0.07       0  4978.0    0.07       0
Bank Sta=4971.2,4978
Exp/Cntr=0.3,0.1

Type RM Length L Ch R = 1,10762,446,446,446
BEGIN DESCRIPTION:
Clear Fork Trib9 20.0
END DESCRIPTION:
XS GIS Cut Line= 3
      1450693.92      6949776.22      1449755.00      6949788.00
      1449354.99      6949938.00
#Sta/Elev= 30
  4065.2 1886.74  4164.1 1883.41  4184.1 1883.52  4194.1 1882.23  4214.1 1881.06
  4304.1 1879.00  4394.1 1875.63  4514.2 1873.90  4607.3 1871.69  4744.2 1870.17
  4824.2 1868.44  4924.2 1867.20  4964.2 1867.53  4974.2 1867.10  4980.7 1865.71
  4981.2 1865.21  4987.1 1865.21  4987.6 1865.71  4994.2 1866.56  5015.7 1866.93
  5057.6 1868.11  5159.9 1873.03  5190.2 1873.88  5245.4 1877.27  5313.9 1880.23
  5330.8 1881.89  5345.9 1882.56  5378.0 1882.62  5391.3 1884.01  5431.4 1885.99
#Mann=4,-1,0
  4065.2    0.07       0  4980.7    0.07       0  4987.6    0.07       0
  5015.7   0.035       0
Bank Sta=4980.7,4987.6
Exp/Cntr=0.3,0.1

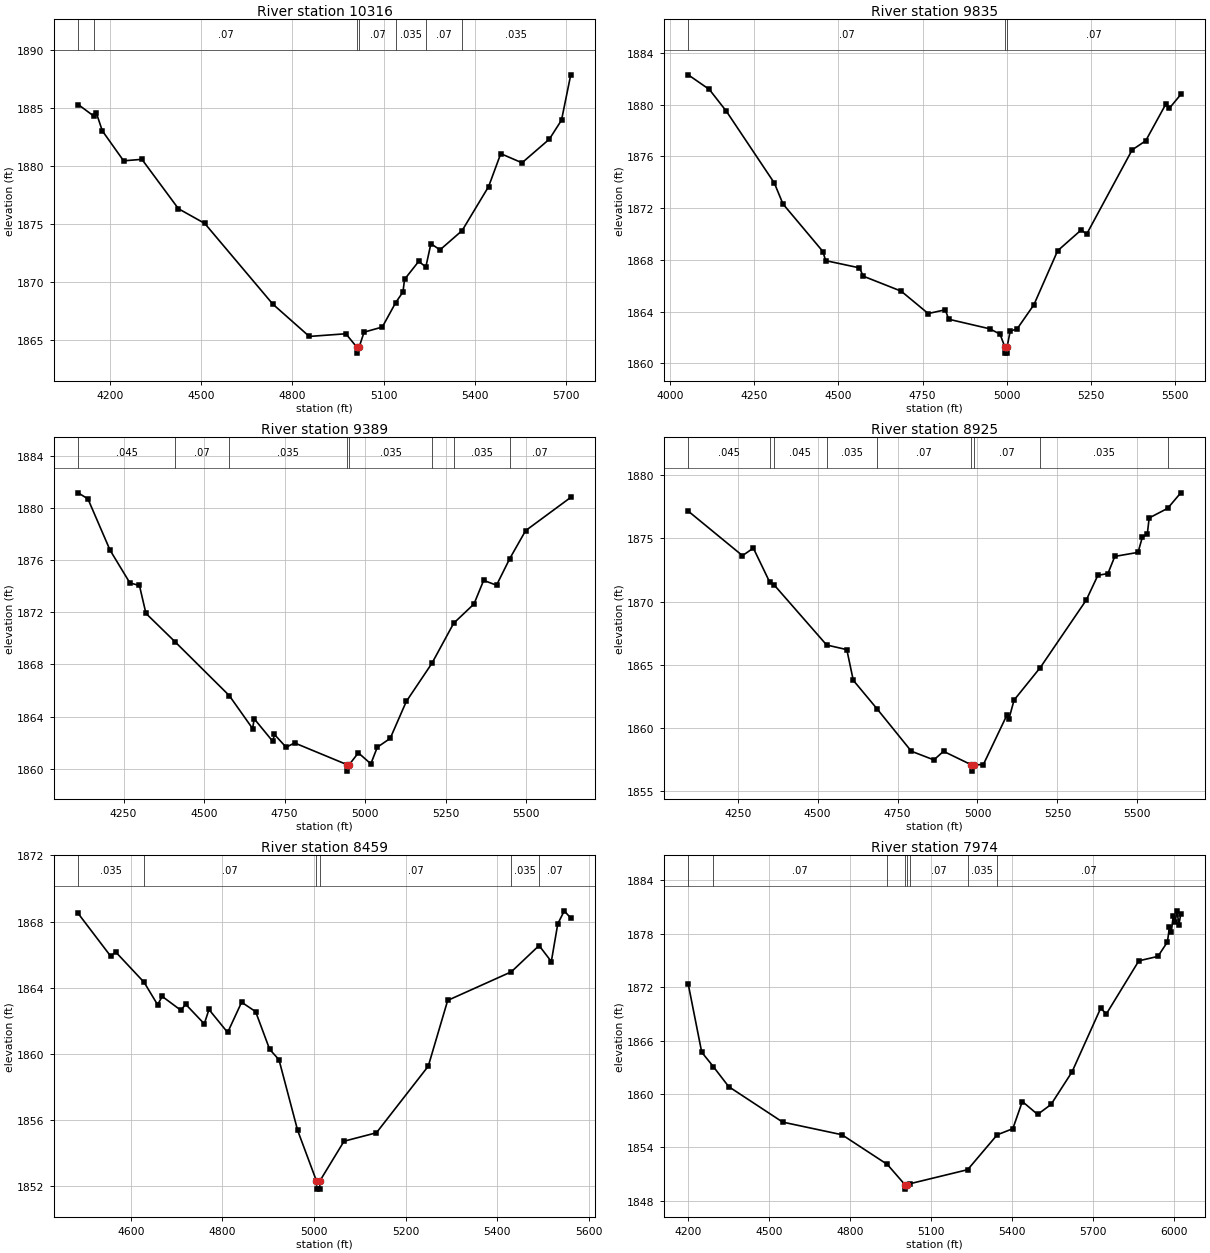
Type RM Length L Ch R = 1,10316,481,481,481
BEGIN DESCRIPTION:
Clear Fork Trib9 19.0
END DESCRIPTION:
XS GIS Cut Line= 3
      1450704.34      6949453.31      1449805.00      6949388.00
      1449084.61      6949409.04
#Sta/Elev= 30
  4094.1 1885.30  4146.1 1884.29  4153.6 1884.60  4173.6 1883.03  4243.8 1880.44
  4304.0 1880.57  4424.3 1876.31  4511.0 1875.04  4735.1 1868.08  4855.4 1865.29
  4975.8 1865.52  5012.3 1864.35  5012.8 1863.85  5019.3 1864.35  5035.8 1865.66
  5095.8 1866.10  5140.0 1868.21  5164.0 1869.13  5169.0 1870.21  5215.9 1871.77
  5239.2 1871.28  5255.9 1873.29  5285.9 1872.76  5358.7 1874.42  5446.0 1878.22
  5486.0 1881.06  5556.0 1880.27  5646.1 1882.31  5686.1 1883.95  5716.5 1887.86
#Mann=7,-1,0
  4094.1   0.035       0  4146.1    0.07       0  5012.3    0.07       0
  5019.3    0.07       0  5140.0   0.035       0  5239.2    0.07       0
  5358.7   0.035       0
Bank Sta=5012.3,5019.3
Exp/Cntr=0.3,0.1

Type RM Length L Ch R = 1,9835,446,446,446
BEGIN DESCRIPTION:
Clear Fork Trib9 18.0
END DESCRIPTION:
XS GIS Cut Line= 3
      1450636.71      6949101.75      1449705.00      6948938.00
      1449191.36      6948992.37
#Sta/Elev= 30
  4054.0 1882.30  4116.7 1881.17  4167.4 1879.48  4309.6 1873.94  4335.3 1872.32
  4454.0 1868.64  4461.9 1867.94  4562.5 1867.38  4573.5 1866.74  4686.3 1865.58
  4766.5 1863.85  4817.2 1864.14  4827.4 1863.41  4949.2 1862.67  4979.7 1862.26
  4993.8 1861.29  4994.3 1860.79  5000.5 1860.79  5001.0 1861.29  5010.0 1862.50
  5030.2 1862.65  5080.4 1864.53  5150.8 1868.70  5221.2 1870.32  5236.9 1869.98
  5372.1 1876.50  5412.3 1877.20  5472.6 1880.06  5482.7 1879.72  5516.5 1880.78
#Mann=3,-1,0
  4054.0    0.07       0  4993.8    0.07       0  5001.0    0.07       0
Bank Sta=4993.8,5001
Exp/Cntr=0.3,0.1

Type RM Length L Ch R = 1,9389,464,464,464
BEGIN DESCRIPTION:
Clear Fork Trib9 17.0
END DESCRIPTION:
XS GIS Cut Line= 3
      1450542.87      6948677.26      1449655.00      6948538.00
      1449024.72      6948557.47
#Sta/Elev= 30
  4108.9 1881.15  4139.3 1880.68  4208.0 1876.75  4269.6 1874.24  4299.1 1874.05
  4319.3 1871.91  4410.2 1869.72  4578.0 1865.61  4650.5 1863.08  4655.5 1863.83
  4713.1 1862.10  4718.2 1862.63  4754.6 1861.65  4780.8 1861.98  4943.3 1860.32
  4943.8 1859.82  4950.5 1860.32  4978.8 1861.22  5017.6 1860.38  5037.6 1861.65
  5077.7 1862.33  5127.7 1865.16  5207.1 1868.08  5274.9 1871.16  5337.8 1872.63
  5367.8 1874.44  5407.8 1874.07  5448.9 1876.11  5498.1 1878.25  5638.2 1880.80
#Mann=8,-1,0
  4108.9   0.045       0  4410.2    0.07       0  4578.0   0.035       0
  4943.3   0.035       0  4950.5   0.035       0  5207.1    0.07       0
  5274.9   0.035       0  5448.9    0.07       0
Bank Sta=4943.3,4950.5
Exp/Cntr=0.3,0.1

Type RM Length L Ch R = 1,8925,466,466,466
BEGIN DESCRIPTION:
Clear Fork Trib9 16.0
END DESCRIPTION:
XS GIS Cut Line= 3
      1450456.99      6948021.01      1449555.00      6948138.00
      1449009.49      6948455.66
#Sta/Elev= 30
  4095.2 1877.17  4264.9 1873.64  4298.9 1874.24  4350.1 1871.54  4363.6 1871.33
  4528.1 1866.56  4591.3 1866.19  4611.5 1863.76  4685.1 1861.52  4793.0 1858.14
  4863.6 1857.45  4893.8 1858.13  4981.0 1857.06  4981.5 1856.56  4988.2 1857.06
  5018.4 1857.08  5092.8 1861.04  5098.6 1860.71  5114.4 1862.19  5196.5 1864.77
  5340.3 1870.12  5376.6 1872.08  5408.0 1872.22  5429.6 1873.58  5502.3 1873.90
  5515.6 1875.09  5531.3 1875.36  5537.1 1876.63  5594.9 1877.39  5636.0 1878.62
#Mann=9,-1,0
  4095.2   0.045       0  4350.1   0.035       0  4363.6   0.045       0
  4528.1   0.035       0  4685.1    0.07       0  4981.0    0.07       0
  4988.2    0.07       0  5196.5   0.035       0  5594.9    0.07       0
Bank Sta=4981,4988.2
Exp/Cntr=0.3,0.1

Type RM Length L Ch R = 1,8459,485,485,485
BEGIN DESCRIPTION:
Clear Fork Trib9 15.0
END DESCRIPTION:
XS GIS Cut Line= 3
      1449955.02      6947838.00      1449455.00      6947738.00
      1449055.00      6948138.00
#Sta/Elev= 30
  4485.0 1868.49  4556.4 1865.89  4566.6 1866.17  4629.1 1864.32  4658.4 1862.97
  4668.6 1863.47  4709.4 1862.63  4719.6 1863.00  4760.4 1861.81  4770.6 1862.68
  4811.4 1861.29  4841.9 1863.12  4872.5 1862.55  4903.1 1860.27  4923.5 1859.64
  4964.3 1855.36  5005.3 1852.31  5005.8 1851.81  5012.4 1851.81  5012.9 1852.31
  5065.6 1854.71  5136.3 1855.22  5249.5 1859.25  5291.9 1863.23  5430.9 1864.96
  5491.5 1866.55  5518.2 1865.58  5532.3 1867.86  5546.5 1868.65  5560.6 1868.21
#Mann=6,-1,0
  4485.0   0.035       0  4629.1    0.07       0  5005.3    0.07       0
  5012.9    0.07       0  5430.9   0.035       0  5491.5    0.07       0
Bank Sta=5005.3,5012.9
Exp/Cntr=0.3,0.1

Type RM Length L Ch R = 1,7974,435,435,435
BEGIN DESCRIPTION:
Clear Fork Trib9 14.0
END DESCRIPTION:
XS GIS Cut Line= 3
      1450155.03      6947288.00      1449355.00      6947288.00
      1448655.03      6948037.96
#Sta/Elev= 30
  4200.4 1872.34  4250.4 1864.69  4293.3 1863.08  4350.4 1860.83  4550.4 1856.85
  4770.4 1855.43  4938.5 1852.10  5003.7 1849.83  5004.2 1849.33  5011.3 1849.83
  5024.2 1849.95  5236.2 1851.51  5345.6 1855.42  5403.7 1856.11  5438.9 1859.16
  5495.6 1857.71  5545.4 1858.83  5623.1 1862.48  5729.1 1869.61  5750.6 1868.99
  5870.8 1874.94  5941.6 1875.44  5976.8 1877.06  5984.1 1878.69  5990.9 1878.16
  5998.3 1879.94  6005.1 1879.26  6012.4 1880.55  6019.3 1878.98  6026.3 1880.22
#Mann=8,-1,0
  4200.4   0.035       0  4293.3    0.07       0  4938.5    0.16       0
  5003.7    0.07       0  5011.3    0.16       0  5024.2    0.07       0
  5236.2   0.035       0  5345.6    0.07       0
Bank Sta=5003.7,5011.3
Exp/Cntr=0.3,0.1

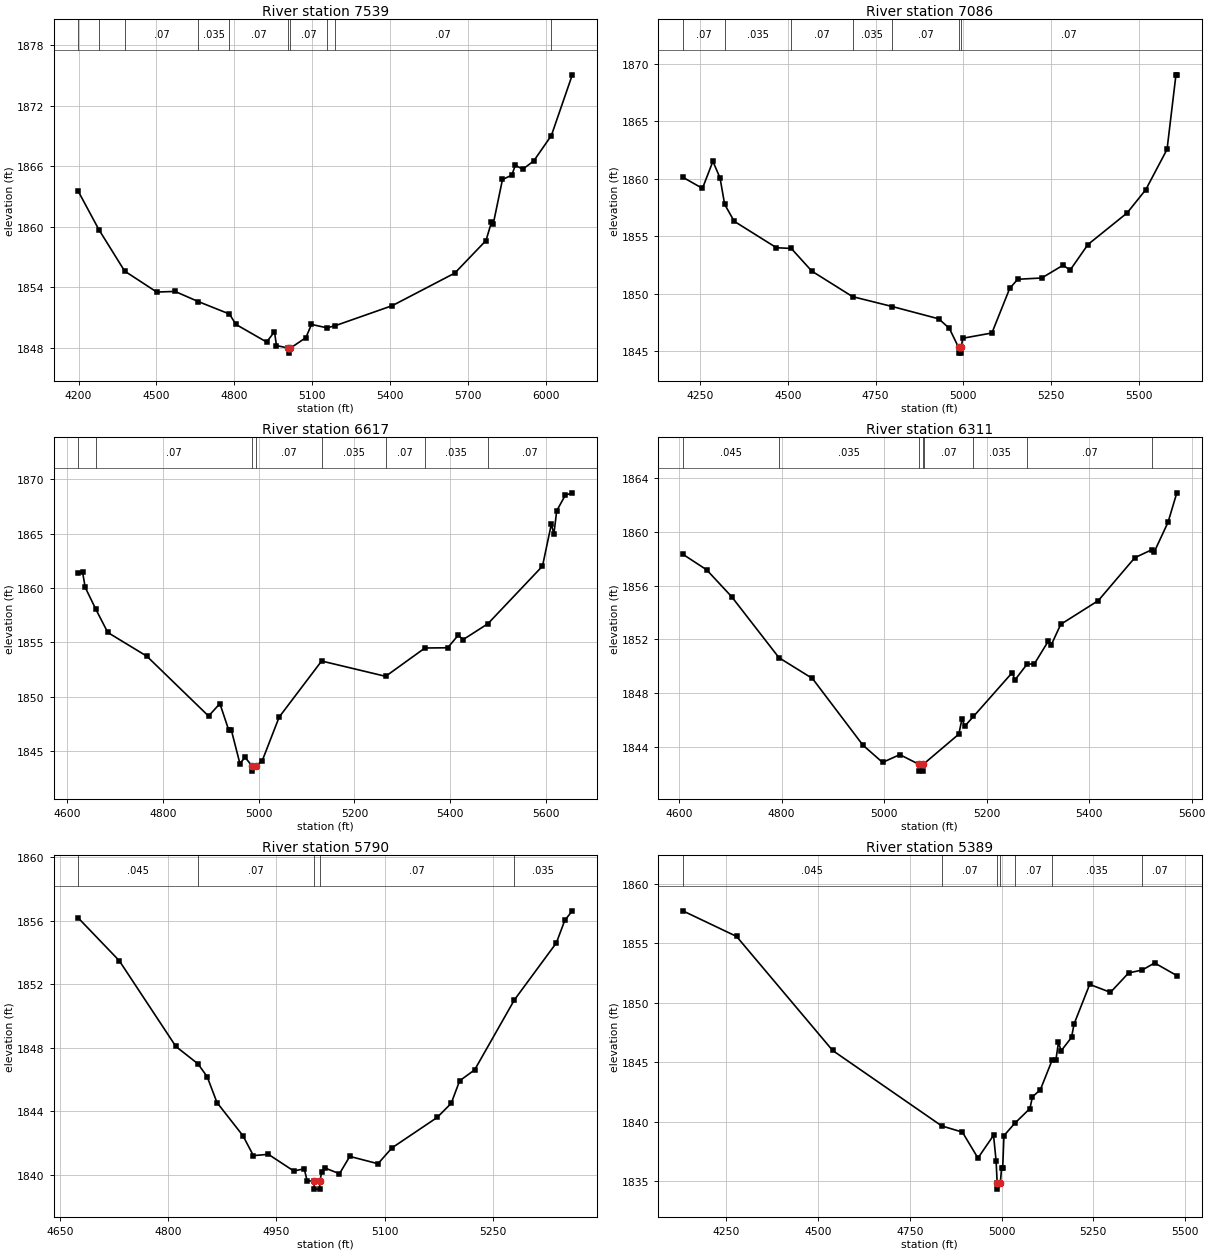
Type RM Length L Ch R = 1,7539,453,453,453
BEGIN DESCRIPTION:
Clear Fork Trib9 13.0
END DESCRIPTION:
XS GIS Cut Line= 3
      1450005.00      6947038.00      1449205.00      6946938.00
      1448405.01      6947687.99
#Sta/Elev= 30
  4198.9 1863.51  4278.2 1859.71  4377.6 1855.59  4501.2 1853.51  4571.8 1853.57
  4661.6 1852.56  4781.2 1851.33  4806.1 1850.30  4924.5 1848.55  4954.7 1849.58
  4962.3 1848.20  5008.3 1847.95  5008.8 1847.45  5016.1 1847.95  5075.7 1848.99
  5097.2 1850.30  5156.6 1849.96  5188.5 1850.17  5408.4 1852.16  5649.1 1855.39
  5769.3 1858.62  5790.3 1860.44  5797.6 1860.31  5832.8 1864.68  5868.5 1865.10
  5882.4 1866.10  5910.5 1865.69  5953.0 1866.51  6021.1 1869.04  6101.7 1875.06
#Mann=10,-1,0
  4198.9    0.07       0  4278.2   0.035       0  4377.6    0.07       0
  4661.6   0.035       0  4781.2    0.07       0  5008.3    0.07       0
  5016.1    0.07       0  5156.6   0.035       0  5188.5    0.07       0
  6021.1   0.035       0
Bank Sta=5008.3,5016.1
Exp/Cntr=0.3,0.1

Type RM Length L Ch R = 1,7086,469,469,469
BEGIN DESCRIPTION:
Clear Fork Trib9 12.0
END DESCRIPTION:
XS GIS Cut Line= 3
      1450050.74      6946622.58      1449255.00      6946538.00
      1448655.00      6946438.00
#Sta/Elev= 30
  4200.1 1860.13  4256.2 1859.16  4286.0 1861.51  4306.4 1860.06  4319.4 1857.78
  4346.7 1856.30  4467.3 1854.00  4509.4 1853.94  4567.9 1851.97  4684.1 1849.75
  4797.3 1848.89  4929.9 1847.82  4960.1 1846.99  4986.3 1845.34  4986.8 1844.84
  4993.8 1844.84  4994.3 1845.34  4997.8 1846.13  5081.4 1846.59  5132.1 1850.46
  5154.9 1851.26  5223.4 1851.37  5284.2 1852.48  5304.5 1852.06  5355.2 1854.28
  5466.7 1857.02  5519.9 1859.04  5580.7 1862.55  5606.1 1869.03  5608.6 1869.03
#Mann=7,-1,0
  4200.1    0.07       0  4319.4   0.035       0  4509.4    0.07       0
  4684.1   0.035       0  4797.3    0.07       0  4986.3    0.07       0
  4994.3    0.07       0
Bank Sta=4986.3,4994.3
Exp/Cntr=0.3,0.1

Type RM Length L Ch R = 1,6617,306,306,306
BEGIN DESCRIPTION:
Clear Fork Trib9 11.0
END DESCRIPTION:
XS GIS Cut Line= 3
      1449604.96      6945988.02      1449255.00      6946138.00
      1448655.04      6946387.98
#Sta/Elev= 30
  4623.8 1861.39  4632.8 1861.47  4638.3 1860.05  4660.6 1858.03  4685.4 1855.90
  4767.0 1853.71  4895.7 1848.20  4919.3 1849.35  4937.5 1846.94  4942.9 1846.96
  4961.0 1843.83  4971.9 1844.40  4985.9 1843.63  4986.4 1843.13  4994.2 1843.63
  5007.3 1844.05  5043.0 1848.11  5131.5 1853.27  5265.1 1851.86  5347.1 1854.47
  5394.5 1854.49  5416.2 1855.63  5427.0 1855.25  5478.3 1856.70  5592.3 1862.01
  5610.7 1865.86  5616.1 1864.98  5622.0 1867.11  5639.9 1868.54  5654.5 1868.76
#Mann=8,-1,0
  4623.8   0.035       0  4660.6    0.07       0  4985.9    0.07       0
  4994.2    0.07       0  5131.5   0.035       0  5265.1    0.07       0
  5347.1   0.035       0  5478.3    0.07       0
Bank Sta=4985.9,4994.2
Exp/Cntr=0.3,0.1

Type RM Length L Ch R = 1,6311,521,521,521
BEGIN DESCRIPTION:
Clear Fork Trib9 10.0
END DESCRIPTION:
XS GIS Cut Line= 3
      1449505.01      6945738.00      1449134.32      6945867.91
      1448588.58      6946036.21
#Sta/Elev= 30
  4607.2 1858.35  4653.7 1857.19  4702.6 1855.18  4794.9 1850.63  4860.2 1849.08
  4958.6 1844.11  4997.0 1842.82  5030.7 1843.40  5068.4 1842.67  5068.9 1842.17
  5076.2 1842.17  5076.7 1842.67  5077.1 1842.70  5145.8 1844.93  5152.0 1846.08
  5157.2 1845.52  5174.4 1846.25  5250.0 1849.52  5255.2 1848.97  5278.9 1850.15
  5293.1 1850.17  5320.6 1851.88  5325.8 1851.56  5344.6 1853.12  5417.9 1854.89
  5489.1 1858.09  5522.0 1858.68  5527.0 1858.52  5553.9 1860.73  5571.1 1862.93
#Mann=8,-1,0
  4607.2   0.045       0  4794.9   0.035       0  5068.4   0.035       0
  5076.7   0.035       0  5077.1    0.07       0  5174.4   0.035       0
  5278.9    0.07       0  5522.0   0.035       0
Bank Sta=5068.4,5076.7
Exp/Cntr=0.3,0.1

Type RM Length L Ch R = 1,5790,401,401,401
BEGIN DESCRIPTION:
Clear Fork Trib9 9.0
END DESCRIPTION:
XS GIS Cut Line= 3
      1449204.98      6945238.02      1448955.00      6945438.00
      1448605.03      6945537.99
#Sta/Elev= 30
  4675.5 1856.16  4732.3 1853.47  4810.7 1848.07  4841.2 1846.98  4854.0 1846.17
  4867.6 1844.54  4903.6 1842.45  4918.0 1841.20  4938.8 1841.28  4974.0 1840.23
  4988.4 1840.37  4992.4 1839.62  5001.8 1839.59  5002.3 1839.09  5009.7 1839.09
  5010.2 1839.59  5012.5 1840.17  5017.7 1840.41  5037.2 1840.06  5051.5 1841.15
  5090.5 1840.69  5110.0 1841.69  5172.4 1843.60  5191.9 1844.49  5203.6 1845.91
  5224.4 1846.60  5279.5 1851.01  5337.5 1854.59  5349.2 1856.01  5359.6 1856.61
#Mann=5,-1,0
  4675.5   0.045       0  4841.2    0.07       0  5001.8    0.07       0
  5010.2    0.07       0  5279.5   0.035       0
Bank Sta=5001.8,5010.2
Exp/Cntr=0.3,0.1

Type RM Length L Ch R = 1,5389,468,468,468
BEGIN DESCRIPTION:
Clear Fork Trib9 8.0
END DESCRIPTION:
XS GIS Cut Line= 3
      1449311.15      6944567.18      1448684.07      6945168.07
      1448359.84      6945518.48
#Sta/Elev= 30
  4131.5 1857.71  4278.0 1855.56  4539.7 1845.98  4836.9 1839.64  4893.2 1839.12
  4935.6 1836.94  4978.1 1838.85  4985.0 1836.72  4988.0 1834.83  4988.5 1834.33
  4996.5 1834.83  5000.0 1836.10  5003.0 1836.10  5006.4 1838.82  5035.9 1839.86
  5077.2 1841.10  5084.0 1842.08  5105.6 1842.68  5138.4 1845.22  5148.1 1845.21
  5154.9 1846.65  5162.3 1845.95  5190.6 1847.08  5197.4 1848.20  5240.0 1851.53
  5296.6 1850.86  5346.0 1852.49  5383.3 1852.74  5416.9 1853.33  5477.4 1852.27
#Mann=7,-1,0
  4131.5   0.045       0  4836.9    0.07       0  4988.0   0.045       0
  4996.5    0.07       0  5035.9    0.07       0  5138.4   0.035       0
  5383.3    0.07       0
Bank Sta=4988,4996.5
Exp/Cntr=0.3,0.1