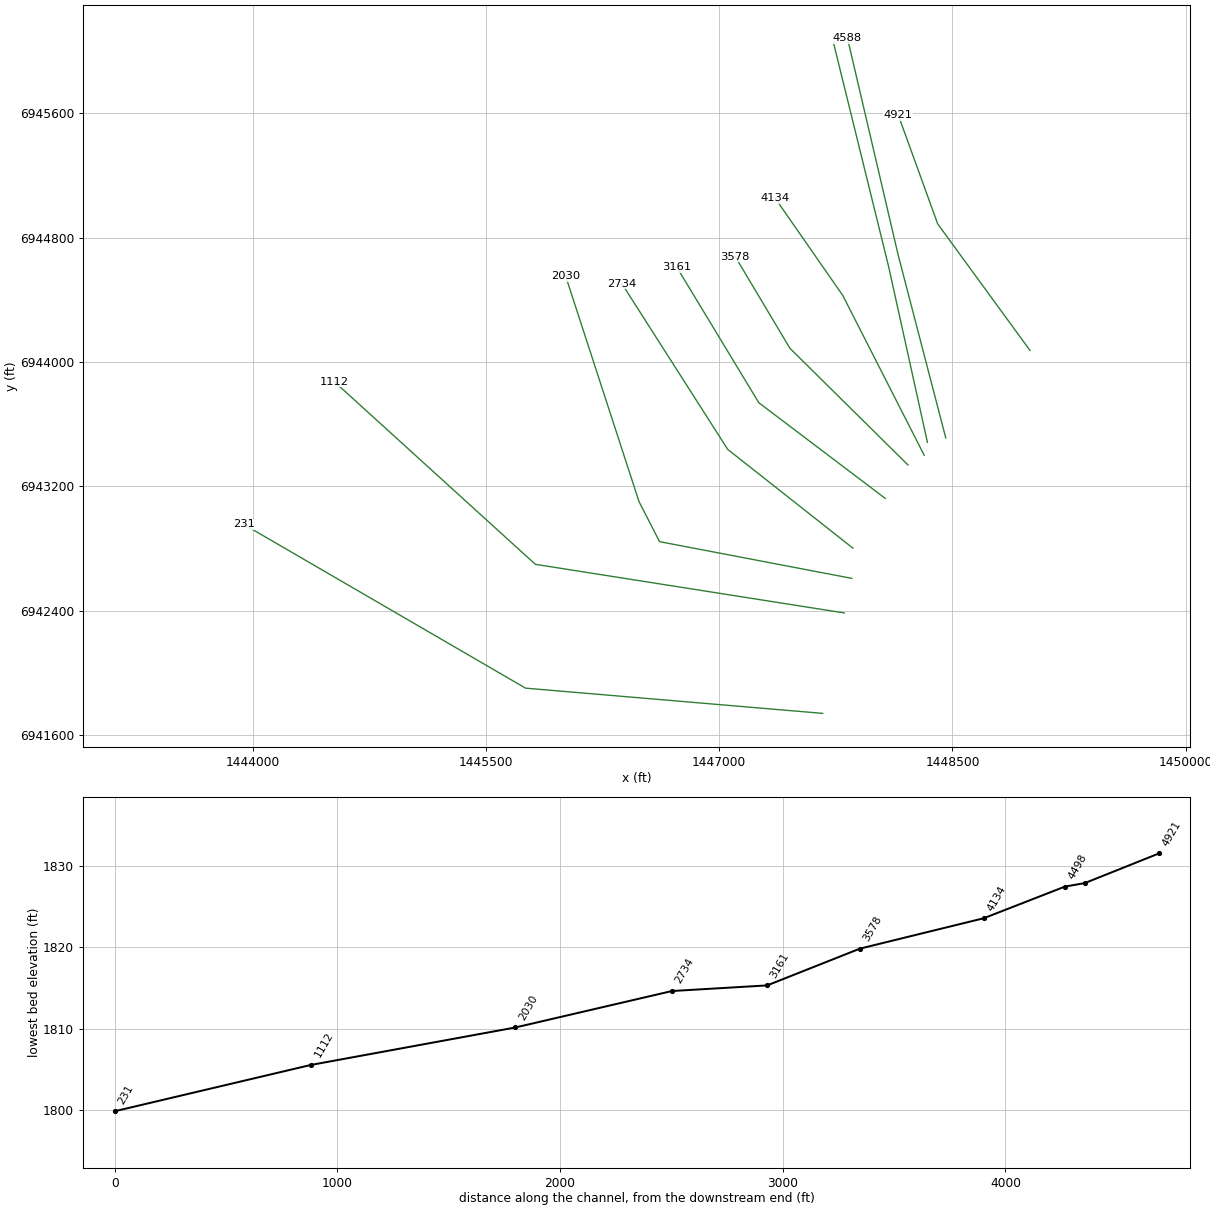
HEC-RAS study Clear Fork Trib9.prj: Clear Fork Trib9 Base Level Engineering

--- Clear Fork Trib9.g01 (geometry) --- (continued)

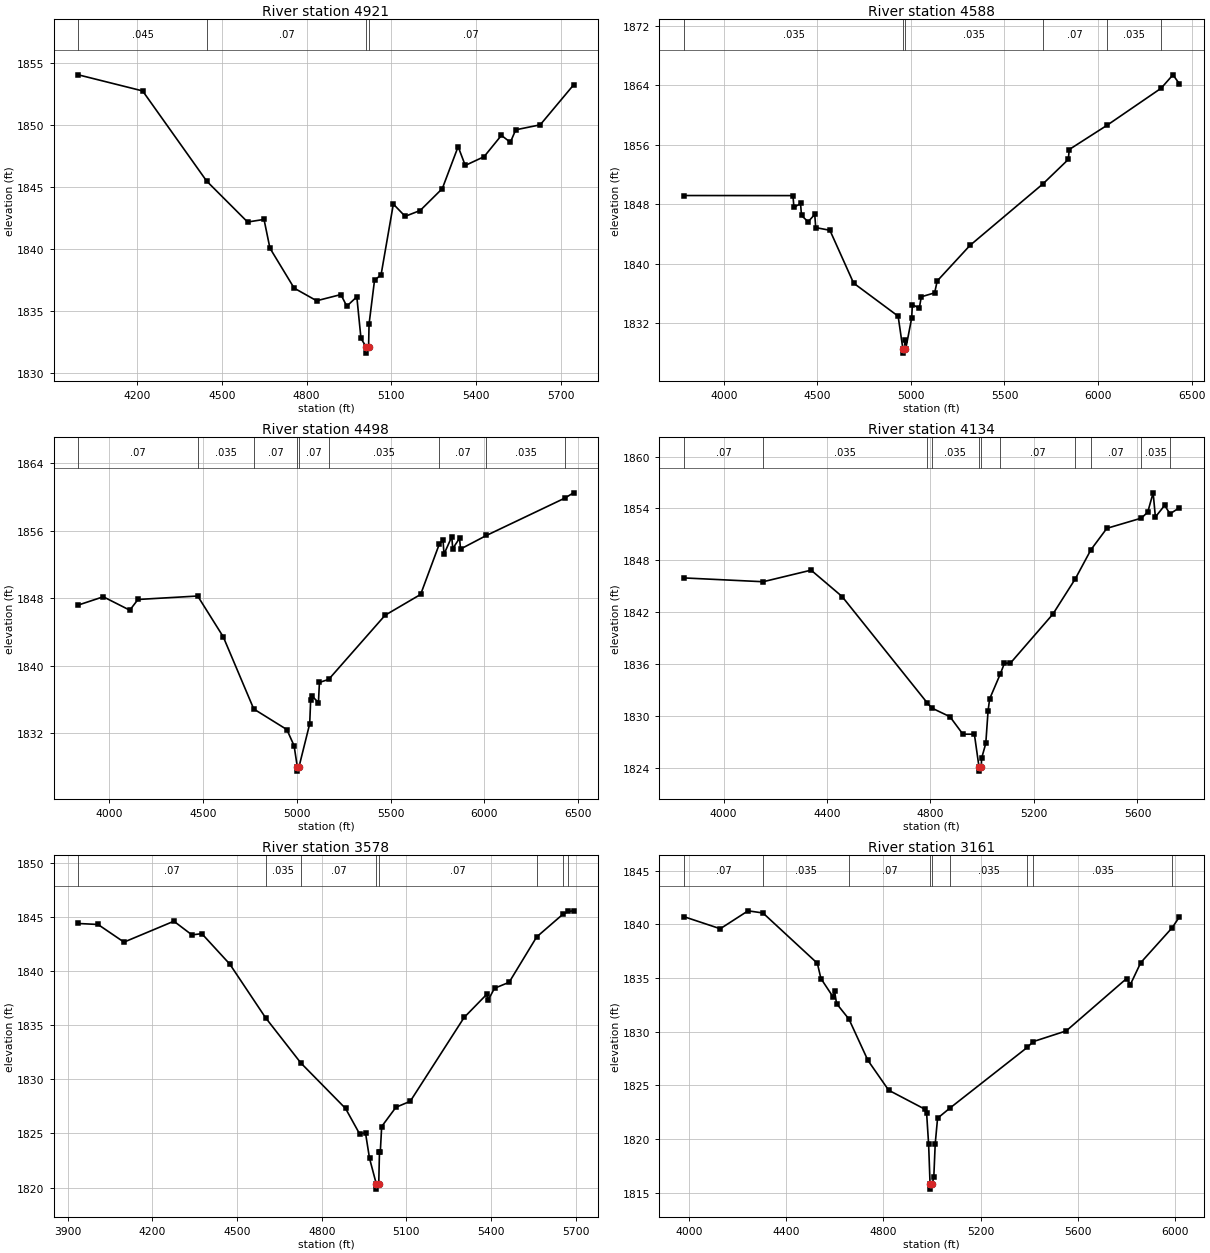
Type RM Length L Ch R = 1,4921,333,333,333
BEGIN DESCRIPTION:
Clear Fork Trib9 7.0
END DESCRIPTION:
XS GIS Cut Line= 3
      1448998.61      6944074.18      1448405.00      6944888.00
      1448151.40      6945588.07
#Sta/Elev= 30
  3992.7 1854.06  4220.2 1852.76  4446.7 1845.48  4591.6 1842.17  4649.7 1842.38
  4670.6 1840.06  4756.3 1836.83  4835.9 1835.81  4921.6 1836.31  4942.5 1835.37
  4978.0 1836.13  4992.7 1832.77  5011.1 1832.08  5011.6 1831.58  5019.6 1832.08
  5021.3 1833.93  5040.6 1837.46  5063.8 1837.91  5107.2 1843.62  5148.9 1842.63
  5202.1 1843.10  5280.4 1844.87  5336.4 1848.26  5361.6 1846.74  5428.3 1847.45
  5489.5 1849.17  5521.2 1848.61  5540.2 1849.62  5626.7 1850.02  5744.6 1853.24
#Mann=4,-1,0
  3992.7   0.045       0  4446.7    0.07       0  5011.1    0.07       0
  5019.6    0.07       0
Bank Sta=5011.1,5019.6
Exp/Cntr=0.3,0.1

Type RM Length L Ch R = 1,4588,90,90,90
BEGIN DESCRIPTION:
Mapping XS e6c60d14
END DESCRIPTION:
XS GIS Cut Line= 3
      1448456.98      6943511.61      1448151.42      6944685.25
      1447825.02      6946081.13
#Sta/Elev= 30
  3787.9 1849.16  4369.6 1849.15  4374.8 1847.56  4410.1 1848.09  4415.3 1846.47
  4450.7 1845.62  4486.0 1846.62  4491.2 1844.84  4567.0 1844.48  4693.7 1837.36
  4931.6 1832.91  4957.4 1828.43  4957.9 1827.93  4966.2 1828.43  4967.0 1829.64
  4972.5 1828.54  5003.8 1832.63  5007.8 1834.47  5044.6 1833.98  5055.4 1835.52
  5126.7 1836.05  5140.4 1837.65  5315.5 1842.44  5705.5 1850.73  5840.9 1854.02
  5846.1 1855.36  6047.2 1858.61  6336.8 1863.61  6400.2 1865.42  6434.2 1864.23
#Mann=6,-1,0
  3787.9   0.035       0  4957.4   0.035       0  4966.2   0.035       0
  5705.5    0.07       0  6047.2   0.035       0  6336.8    0.07       0
Bank Sta=4957.4,4966.2
Exp/Cntr=0.3,0.1

Type RM Length L Ch R = 1,4498,364,364,364
BEGIN DESCRIPTION:
Mapping XS 8f7f0d65
END DESCRIPTION:
XS GIS Cut Line= 3
      1448338.92      6943483.82      1448088.92      6944615.81
      1447734.79      6946053.16
#Sta/Elev= 30
  3835.7 1847.19  3968.9 1848.17  4110.1 1846.58  4153.8 1847.85  4472.0 1848.26
  4608.1 1843.43  4770.9 1834.86  4947.3 1832.42  4985.9 1830.50  5003.1 1827.99
  5003.6 1827.49  5011.9 1827.99  5069.1 1833.10  5074.3 1835.98  5079.6 1836.43
  5115.7 1835.63  5120.9 1838.01  5170.3 1838.37  5471.0 1845.98  5660.4 1848.45
  5759.9 1854.42  5779.7 1854.89  5784.9 1853.22  5826.4 1855.30  5831.5 1853.88
  5867.9 1855.12  5873.0 1853.83  6010.8 1855.44  6428.7 1859.87  6475.3 1860.50
#Mann=9,-1,0
  3835.7    0.07       0  4472.0   0.035       0  4770.9    0.07       0
  5003.1    0.07       0  5011.9    0.07       0  5170.3   0.035       0
  5759.9    0.07       0  6010.8   0.035       0  6428.7    0.07       0
Bank Sta=5003.1,5011.9
Exp/Cntr=0.3,0.1

Type RM Length L Ch R = 1,4134,556,556,556
BEGIN DESCRIPTION:
Clear Fork Trib9 5.0
END DESCRIPTION:
XS GIS Cut Line= 3
      1448318.06      6943400.57      1447794.94      6944427.39
      1447360.00      6945052.95
#Sta/Elev= 30
  3847.6 1845.96  4153.1 1845.52  4338.5 1846.86  4458.3 1843.81  4787.7 1831.49
  4804.5 1830.91  4875.2 1829.90  4925.2 1827.88  4969.7 1827.87  4987.5 1824.10
  4988.0 1823.60  4996.4 1824.10  4997.5 1825.07  5013.8 1826.81  5022.6 1830.58
  5028.7 1831.96  5069.5 1834.82  5086.0 1836.10  5109.0 1836.10  5273.1 1841.77
  5359.7 1845.85  5420.4 1849.23  5481.7 1851.70  5615.0 1852.88  5639.7 1853.57
  5660.7 1855.81  5669.4 1853.01  5705.2 1854.36  5725.9 1853.38  5761.9 1854.08
#Mann=11,-1,0
  3847.6    0.07       0  4153.1   0.035       0  4787.7    0.07       0
  4804.5   0.035       0  4987.5   0.035       0  4996.4   0.035       0
  5069.5    0.07       0  5359.7   0.035       0  5420.4    0.07       0
  5615.0   0.035       0  5725.9    0.07       0
Bank Sta=4987.5,4996.4
Exp/Cntr=0.3,0.1

Type RM Length L Ch R = 1,3578,417,417,417
BEGIN DESCRIPTION:
Clear Fork Trib9 4.0
END DESCRIPTION:
XS GIS Cut Line= 3
      1448213.90      6943338.05      1447455.00      6944088.00
      1447102.82      6944678.28
#Sta/Elev= 30
  3937.7 1844.39  4007.6 1844.30  4099.5 1842.67  4276.3 1844.60  4340.0 1843.34
  4375.3 1843.45  4474.3 1840.64  4601.0 1835.69  4726.4 1831.50  4884.4 1827.31
  4934.0 1824.97  4955.1 1825.05  4969.3 1822.71  4993.1 1820.36  4993.6 1819.86
  5002.0 1820.36  5004.6 1823.29  5007.5 1823.29  5012.4 1825.64  5062.9 1827.42
  5113.6 1827.97  5304.4 1835.71  5384.2 1837.84  5390.0 1837.34  5412.2 1838.41
  5463.9 1838.96  5561.5 1843.15  5653.7 1845.23  5673.6 1845.50  5692.0 1845.56
#Mann=8,-1,0
  3937.7    0.07       0  4601.0   0.035       0  4726.4    0.07       0
  4993.1    0.07       0  5002.0    0.07       0  5561.5   0.035       0
  5653.7    0.07       0  5673.6   0.035       0
Bank Sta=4993.1,5002
Exp/Cntr=0.3,0.1

Type RM Length L Ch R = 1,3161,427,427,427
BEGIN DESCRIPTION:
Clear Fork Trib9 3.0
END DESCRIPTION:
XS GIS Cut Line= 3
      1448068.07      6943122.76      1447255.00      6943738.00
      1446727.81      6944608.85
#Sta/Elev= 30
  3980.4 1840.72  4129.2 1839.60  4243.6 1841.27  4304.8 1841.07  4528.7 1836.38
  4543.3 1834.96  4593.2 1833.25  4599.5 1833.78  4607.8 1832.62  4658.6 1831.18
  4736.7 1827.33  4822.1 1824.55  4971.9 1822.77  4978.2 1822.42  4986.5 1819.51
  4992.4 1815.83  4992.9 1815.33  5001.4 1815.83  5007.8 1816.44  5013.6 1819.55
  5023.3 1821.94  5075.0 1822.90  5392.3 1828.54  5416.9 1829.08  5552.8 1830.08
  5801.1 1834.96  5816.6 1834.40  5859.3 1836.44  5988.4 1839.69  6018.0 1840.69
#Mann=9,-1,0
  3980.4    0.07       0  4304.8   0.035       0  4658.6    0.07       0
  4992.4    0.07       0  5001.4    0.07       0  5075.0   0.035       0
  5392.3    0.07       0  5416.9   0.035       0  5988.4    0.07       0
Bank Sta=4992.4,5001.4
Exp/Cntr=0.3,0.1

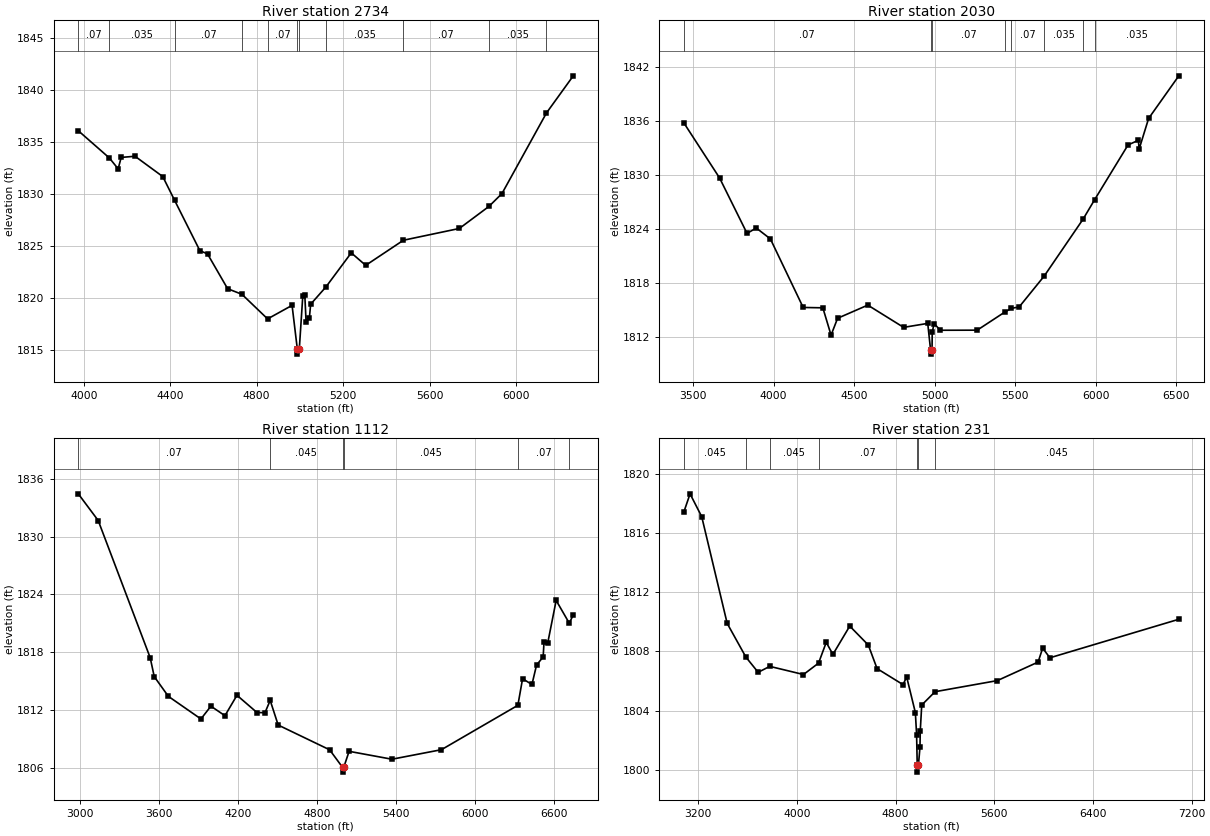
Type RM Length L Ch R = 1,2734,704,704,704
BEGIN DESCRIPTION:
Clear Fork Trib9 2.0
END DESCRIPTION:
XS GIS Cut Line= 3
      1447859.78      6942803.28      1447055.00      6943438.00
      1446374.18      6944503.85
#Sta/Elev= 30
  3974.8 1836.08  4118.4 1833.47  4159.2 1832.42  4173.2 1833.52  4237.3 1833.63
  4365.6 1831.68  4420.6 1829.39  4537.2 1824.57  4572.5 1824.26  4665.5 1820.92
  4731.9 1820.38  4850.5 1818.02  4963.7 1819.32  4987.9 1815.14  4988.4 1814.64
  4997.2 1815.14  5013.3 1820.24  5022.6 1820.30  5028.5 1817.75  5043.7 1818.10
  5049.7 1819.43  5120.4 1821.09  5237.5 1824.36  5304.3 1823.16  5478.7 1825.57
  5737.5 1826.70  5874.0 1828.81  5934.6 1830.05  6140.6 1837.79  6264.5 1841.35
#Mann=11,-1,0
  3974.8    0.07       0  4118.4   0.035       0  4420.6    0.07       0
  4731.9   0.035       0  4850.5    0.07       0  4987.9    0.07       0
  4997.2    0.07       0  5120.4   0.035       0  5478.7    0.07       0
  5874.0   0.035       0  6140.6    0.07       0
Bank Sta=4987.9,4997.2
Exp/Cntr=0.3,0.1

Type RM Length L Ch R = 1,2030,918,918,918
BEGIN DESCRIPTION:
Mapping XS 2f135719
END DESCRIPTION:
XS GIS Cut Line= 4
      1447852.84      6942608.86      1446616.69      6942844.97
      1446484.75      6943101.92      1446012.56      6944553.20
#Sta/Elev= 30
  3442.8 1835.82  3664.6 1829.71  3835.3 1823.55  3892.5 1824.15  3980.2 1822.94
  4183.8 1815.33  4306.0 1815.29  4356.9 1812.26  4397.6 1814.13  4585.1 1815.59
  4807.5 1813.12  4957.2 1813.56  4974.7 1810.65  4975.2 1810.15  4984.0 1810.65
  4985.1 1812.57  4996.5 1813.54  5035.6 1812.80  5264.4 1812.81  5436.0 1814.82
  5476.5 1815.23  5525.1 1815.39  5680.6 1818.82  5922.1 1825.14  5992.8 1827.27
  6201.0 1833.37  6264.9 1833.88  6270.1 1832.92  6328.7 1836.31  6516.3 1841.04
#Mann=8,-1,0
  3442.8    0.07       0  4974.7    0.07       0  4984.0    0.07       0
  5436.0   0.035       0  5476.5    0.07       0  5680.6   0.035       0
  5922.1    0.07       0  5992.8   0.035       0
Bank Sta=4974.7,4984
Exp/Cntr=0.3,0.1

Type RM Length L Ch R = 1,1112,881,881,881
BEGIN DESCRIPTION:
Mapping XS 7c4fa13b
END DESCRIPTION:
XS GIS Cut Line= 3
      1447804.18      6942386.64      1445818.08      6942699.14
      1444526.45      6943872.72
#Sta/Elev= 30
  2988.3 1834.44  3139.3 1831.67  3534.1 1817.41  3564.5 1815.46  3671.7 1813.41
  3918.8 1811.06  3994.5 1812.39  4101.0 1811.40  4192.2 1813.52  4344.0 1811.73
  4404.7 1811.71  4444.3 1812.99  4504.9 1810.43  4895.3 1807.86  4993.2 1806.04
  4993.7 1805.54  5002.6 1806.04  5043.0 1807.70  5368.0 1806.88  5743.7 1807.87
  6323.6 1812.48  6359.3 1815.24  6430.3 1814.64  6465.4 1816.66  6515.4 1817.50
  6522.2 1819.10  6550.6 1818.98  6614.1 1823.37  6713.5 1821.01  6744.0 1821.87
#Mann=6,-1,0
  2988.3    0.07       0  4444.3   0.045       0  4993.2   0.045       0
  5002.6   0.045       0  6323.6    0.07       0  6713.5   0.035       0
Bank Sta=4993.2,5002.6
Exp/Cntr=0.3,0.1

Type RM Length L Ch R = 1,231,0,0,0
BEGIN DESCRIPTION:
Clear Fork Trib9 1.0
END DESCRIPTION:
XS GIS Cut Line= 3
      1447665.27      6941740.81      1445754.84      6941903.06
      1443943.04      6942956.11
#Sta/Elev= 30
  3082.7 1817.40  3133.1 1818.63  3227.6 1817.09  3434.2 1809.88  3585.6 1807.61
  3685.1 1806.58  3779.4 1806.98  4052.7 1806.43  4174.8 1807.20  4237.1 1808.60
  4291.3 1807.79  4427.8 1809.70  4578.3 1808.42  4649.2 1806.83  4859.3 1805.75
  4889.4 1806.26  4959.7 1803.86  4969.7 1802.38  4974.8 1800.34  4975.3 1799.84
  4984.8 1800.34  4997.0 1801.51  4999.6 1802.65  5011.4 1804.37  5119.4 1805.27
  5624.4 1806.02  5954.6 1807.27  5991.8 1808.21  6050.6 1807.56  7095.6 1810.16
#Mann=7,-1,0
  3082.7   0.045       0  3585.6    0.07       0  3779.4   0.045       0
  4174.8    0.07       0  4974.8    0.07       0  4984.8    0.07       0
  5119.4   0.045       0
Bank Sta=4974.8,4984.8
Exp/Cntr=0.3,0.1

Chan Stop Cuts=-1