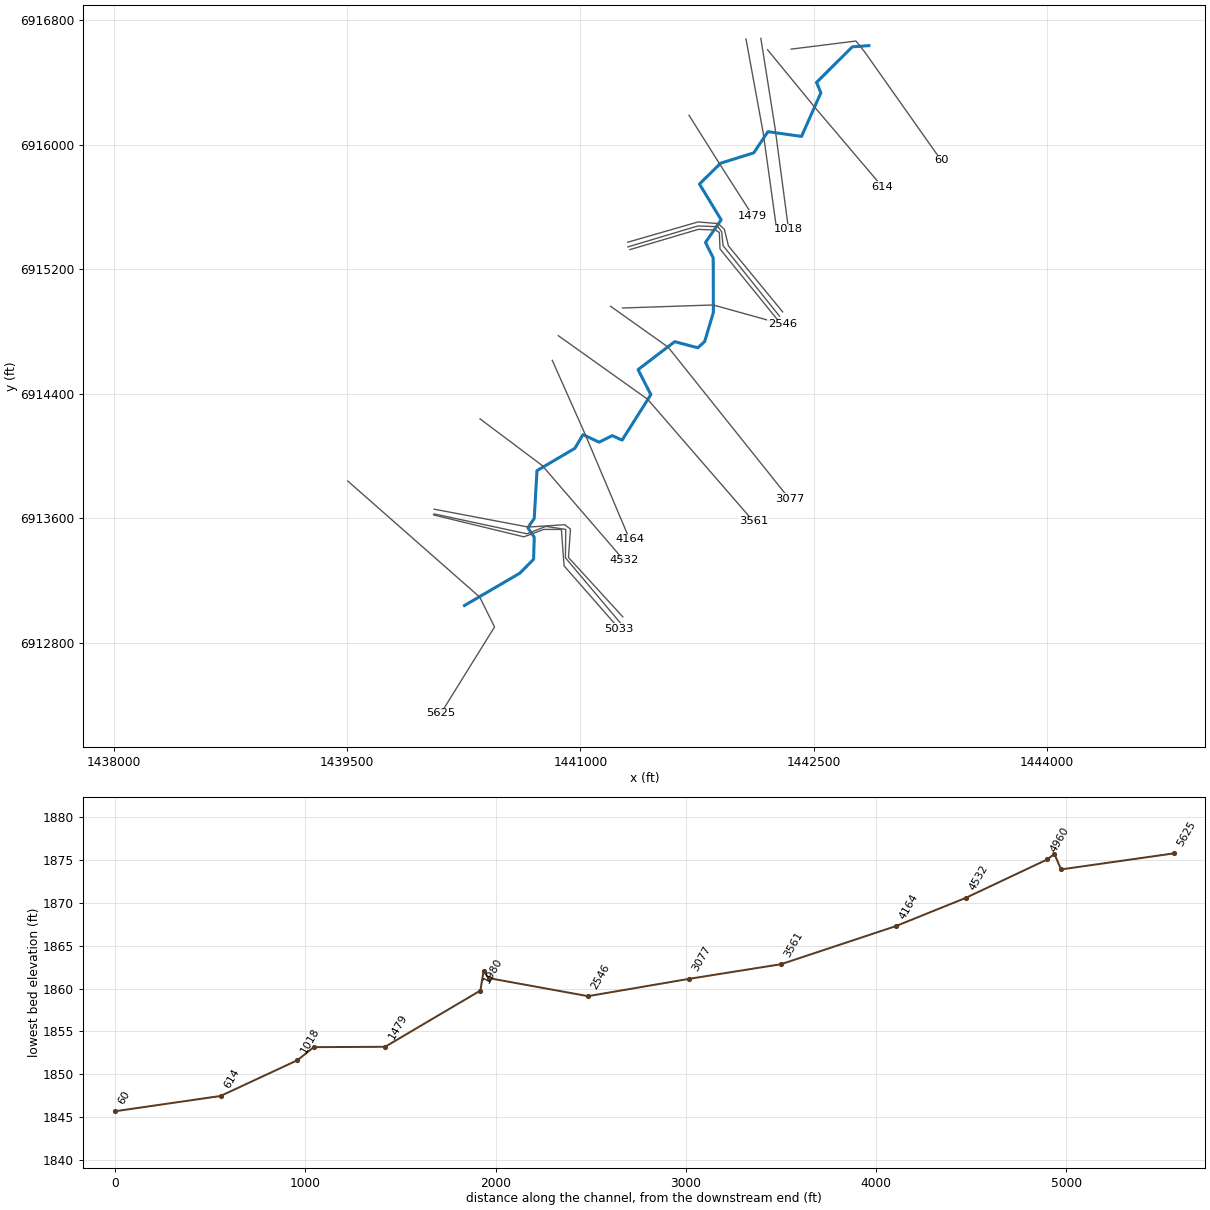
--- Dry Creek Trib1.prj (project) ---

Proj Title=Dry Creek Trib1 Base Level Engineering
Current Plan=p01
Default Exp/Contr=0.3,0.1
English Units
Geom File=g01
Flow File=f01
Plan File=p01
BEGIN DESCRIPTION:
Dry Creek Trib1
END DESCRIPTION:

--- Dry Creek Trib1.p01 (plan) ---

Plan Title=Multiple Run
Short Identifier=Multiple
Geom File=g01
Flow File=f01
Subcritical Flow
K Sum by GR= 0
Std Step Tol= 0.01
Critical Tol= 0.01
Num of Std Step Trials= 20
Max Error Tol= 0.3
Flow Tol Ratio= 0.001
Split Flow NTrial= 30
Split Flow Tol= 0.02
Split Flow Ratio= 0.02
Log Output Level= 0
Friction Slope Method= 1
Unsteady Friction Slope Method= 2
Unsteady Bridges Friction Slope Method= 1
Parabolic Critical Depth
Global Vel Dist=  1 , 1 , 1
Global Log Level= 0
CheckData=True
Encroach Param= -1, 0, 0, 0
BEGIN DESCRIPTION:
Multiple Run
END DESCRIPTION:

--- Dry Creek Trib1.f01 (steady flow) ---

Flow Title=Multiple
Number of Profiles=7
Profile Names=10-year,25-year,50-year,1pct_min,100-year,1pct_plu,500-year
River Rch & RM= Dry Creek Trib1,Reach-1,5625
     161     218     264     159     318     634     465
River Rch & RM= Dry Creek Trib1,Reach-1,5033
     325     457     567     350     698    1393    1070
River Rch & RM= Dry Creek Trib1,Reach-1,2023
     348     491     611     378     754    1505    1162
Boundary for River Rch & Prof#=Dry Creek Trib1,Reach-1,1
Up Type=0
Dn Type=3
Dn Slope=0.005
Boundary for River Rch & Prof#=Dry Creek Trib1,Reach-1,2
Up Type=0
Dn Type=3
Dn Slope=0.005
Boundary for River Rch & Prof#=Dry Creek Trib1,Reach-1,3
Up Type=0
Dn Type=3
Dn Slope=0.005
Boundary for River Rch & Prof#=Dry Creek Trib1,Reach-1,4
Up Type=0
Dn Type=3
Dn Slope=0.005
Boundary for River Rch & Prof#=Dry Creek Trib1,Reach-1,5
Up Type=0
Dn Type=3
Dn Slope=0.005
Boundary for River Rch & Prof#=Dry Creek Trib1,Reach-1,6
Up Type=0
Dn Type=3
Dn Slope=0.005
Boundary for River Rch & Prof#=Dry Creek Trib1,Reach-1,7
Up Type=0
Dn Type=3
Dn Slope=0.005

--- Dry Creek Trib1.g01 (geometry) ---

Geom Title=Existing Conditions

River Reach=Dry Creek Trib1,Reach-1
Reach XY= 30
      1440255.00      6913038.00      1440611.19      6913245.86
      1440699.55      6913335.54      1440703.63      6913477.56
      1440662.56      6913538.00      1440703.62      6913598.44
      1440721.27      6913905.14      1440964.97      6914048.71
      1441017.02      6914136.80      1441120.40      6914088.17
      1441205.10      6914130.16      1441268.69      6914101.50
      1441453.41      6914394.05      1441371.20      6914554.67
      1441606.59      6914734.32      1441755.34      6914695.22
      1441799.48      6914735.02      1441855.43      6914922.82
      1441854.46      6915272.79      1441804.96      6915372.66
      1441905.37      6915517.80      1441765.96      6915748.00
      1441902.70      6915882.17      1442115.10      6915948.39
      1442206.25      6916084.56      1442422.16      6916054.10
      1442546.75      6916334.77      1442518.65      6916401.34
      1442748.78      6916630.26      1442855.00      6916638.00

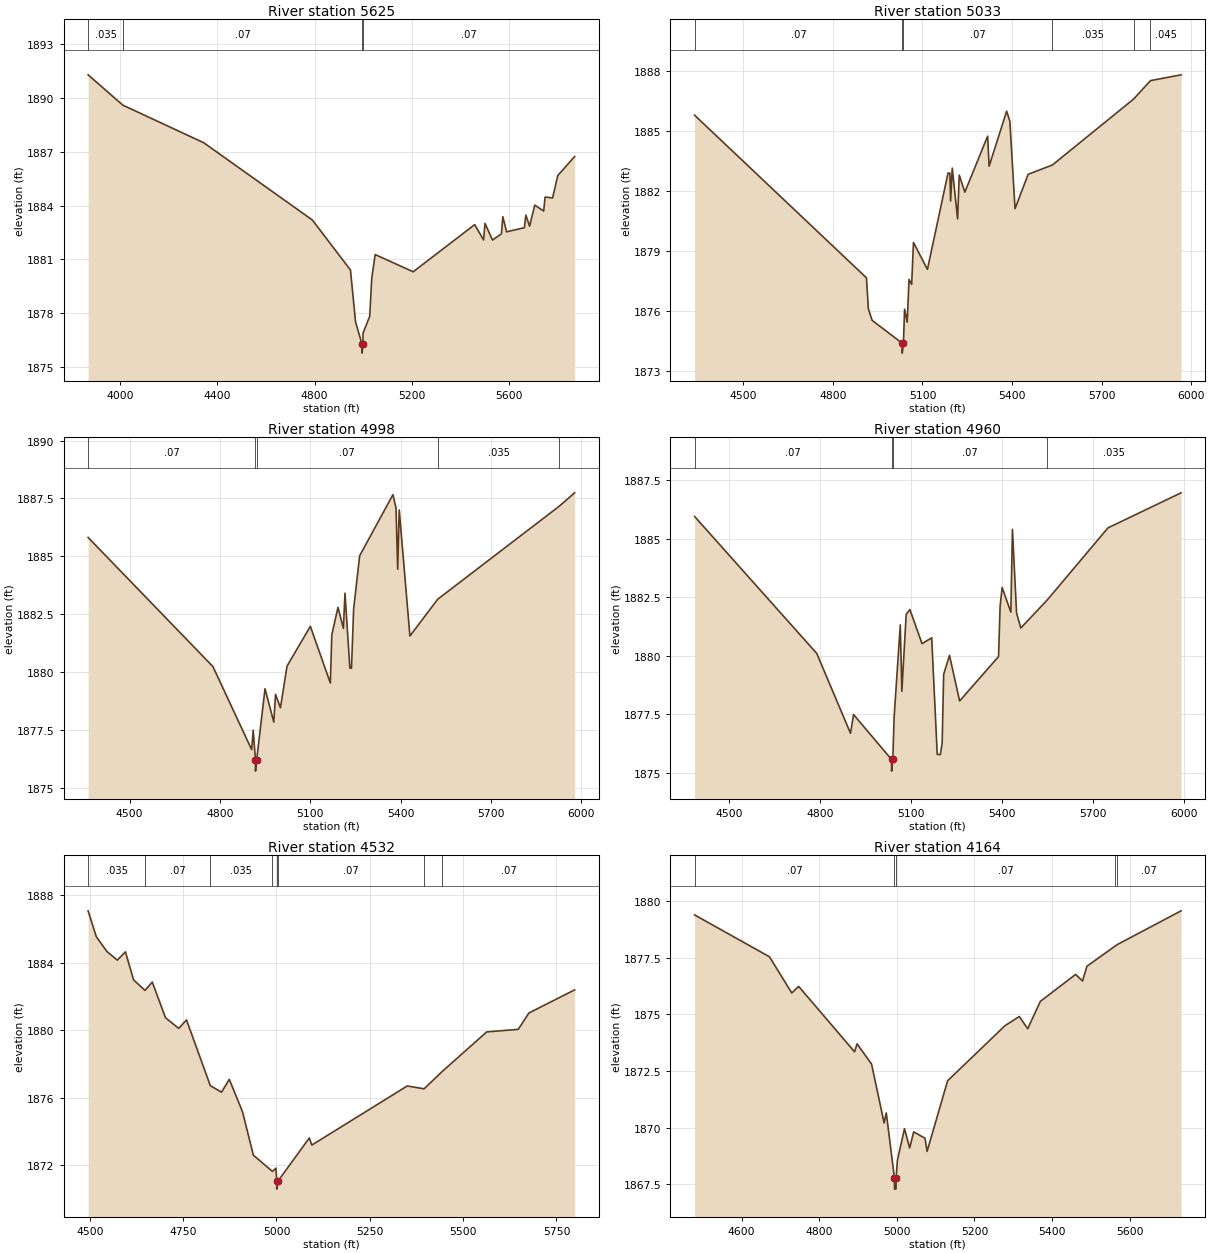
Type RM Length L Ch R = 1,5625,592,592,592
BEGIN DESCRIPTION:
Dry Creek Trib1 7.0
END DESCRIPTION:
XS GIS Cut Line= 4
      1439504.98      6913838.02      1440353.42      6913091.81
      1440448.38      6912900.06      1440103.30      6912344.47
#Sta/Elev= 30
  3870.1 1891.30  4012.5 1889.61  4345.0 1887.51  4790.9 1883.20  4947.5 1880.41
  4968.4 1877.51  4994.8 1876.27  4995.1 1875.77  4998.8 1876.27  4999.1 1876.89
  5026.6 1877.83  5034.8 1879.94  5048.9 1881.27  5205.1 1880.31  5457.5 1882.94
  5494.1 1882.09  5500.0 1883.01  5530.7 1882.08  5567.3 1882.43  5573.2 1883.38
  5588.6 1882.54  5661.8 1882.77  5667.7 1883.47  5683.1 1882.85  5704.3 1884.03
  5740.9 1883.70  5746.8 1884.48  5777.5 1884.43  5798.8 1885.68  5868.0 1886.74
#Mann=4,-1,0
  3870.1   0.035       0  4012.5    0.07       0  4994.8    0.07       0
  4998.8    0.07       0
Bank Sta=4994.8,4998.8
Exp/Cntr=0.3,0.1

Type RM Length L Ch R = 1,5033,35,35,35
BEGIN DESCRIPTION:
Mapping XS 79e02325
END DESCRIPTION:
XS GIS Cut Line= 6
      1440055.57      6913620.55      1440637.18      6913479.49
      1440765.22      6913527.23      1440878.06      6913527.23
      1440895.42      6913292.86      1441249.15      6912889.22
#Sta/Elev= 30
  4336.6 1885.81  4912.3 1877.67  4918.8 1876.12  4931.4 1875.54  5031.9 1874.40
  5032.2 1873.90  5036.2 1874.40  5040.1 1876.10  5048.9 1875.45  5055.0 1877.59
  5063.8 1877.34  5069.9 1879.44  5116.6 1878.09  5185.6 1882.91  5191.9 1882.91
  5194.3 1881.51  5199.8 1883.16  5217.7 1880.62  5223.2 1882.81  5242.0 1881.96
  5318.3 1884.76  5323.4 1883.26  5382.0 1886.01  5392.8 1885.51  5410.1 1881.13
  5454.0 1882.85  5535.6 1883.32  5807.6 1886.62  5863.9 1887.54  5966.4 1887.83
#Mann=6,-1,0
  4336.6    0.07       0  5031.9    0.07       0  5036.2    0.07       0
  5535.6   0.035       0  5807.6    0.07       0  5863.9   0.045       0
Bank Sta=5031.9,5036.2
Exp/Cntr=0.3,0.1

Type RM Length L Ch R = 1,4998,38,38,38
BEGIN DESCRIPTION:
Mapping XS fb252c1b
END DESCRIPTION:
XS GIS Cut Line= 6
      1440059.93      6913627.06      1440656.71      6913499.02
      1440778.24      6913546.76      1440906.27      6913527.23
      1440904.10      6913344.94      1441264.34      6912917.43
#Sta/Elev= 30
  4362.3 1885.81  4776.6 1880.23  4905.2 1876.64  4910.3 1877.48  4917.6 1876.21
  4917.9 1875.71  4921.9 1876.21  4949.5 1879.27  4978.7 1877.83  4984.4 1879.03
  5000.7 1878.45  5022.6 1880.25  5100.0 1881.97  5166.3 1879.52  5171.2 1881.60
  5191.7 1882.79  5209.7 1881.88  5214.9 1883.40  5231.2 1880.16  5236.5 1880.16
  5243.7 1882.73  5263.7 1885.02  5374.1 1887.66  5384.3 1887.09  5389.9 1884.44
  5395.0 1887.00  5430.5 1881.55  5522.7 1883.14  5926.0 1887.16  5977.2 1887.74
#Mann=5,-1,0
  4362.3    0.07       0  4917.6    0.07       0  4921.9    0.07       0
  5522.7   0.035       0  5926.0   0.045       0
Bank Sta=4917.6,4921.9
Exp/Cntr=0.3,0.1

Type RM Length L Ch R = 1,4960,428,428,428
BEGIN DESCRIPTION:
Mapping XS ead561bc
END DESCRIPTION:
XS GIS Cut Line= 6
      1440059.88      6913657.45      1440665.39      6913542.42
      1440899.76      6913557.61      1440936.66      6913529.40
      1440923.64      6913347.11      1441273.02      6912965.17
#Sta/Elev= 30
  4385.4 1885.95  4788.5 1880.09  4899.6 1876.68  4909.7 1877.48  5034.9 1875.56
  5035.2 1875.06  5039.2 1875.56  5043.4 1877.35  5063.8 1881.31  5069.0 1878.47
  5083.2 1881.76  5095.5 1881.97  5135.5 1880.51  5167.4 1880.76  5185.7 1875.77
  5195.8 1875.77  5201.9 1876.26  5206.9 1879.20  5226.1 1880.01  5259.5 1878.06
  5387.9 1879.96  5393.0 1882.10  5399.7 1882.91  5428.5 1881.86  5433.7 1885.40
  5447.3 1881.82  5461.3 1881.18  5547.9 1882.37  5748.6 1885.46  5989.9 1886.96
#Mann=4,-1,0
  4385.4    0.07       0  5034.9    0.07       0  5039.2    0.07       0
  5547.9   0.035       0
Bank Sta=5034.9,5039.2
Exp/Cntr=0.3,0.1

Type RM Length L Ch R = 1,4532,368,368,368
BEGIN DESCRIPTION:
Dry Creek Trib1 6.0
END DESCRIPTION:
XS GIS Cut Line= 3
      1440354.98      6914238.02      1440755.00      6913938.00
      1441279.53      6913329.76
#Sta/Elev= 30
  4495.5 1887.06  4517.4 1885.53  4545.5 1884.66  4573.7 1884.14  4595.5 1884.63
  4617.4 1882.97  4647.8 1882.35  4667.4 1882.84  4702.8 1880.73  4738.2 1880.10
  4759.1 1880.60  4822.8 1876.71  4852.8 1876.32  4873.7 1877.08  4909.1 1875.16
  4938.2 1872.59  4989.2 1871.63  4998.8 1871.82  5000.5 1871.08  5000.8 1870.58
  5004.9 1871.08  5088.0 1873.61  5094.8 1873.19  5350.4 1876.69  5395.4 1876.52
  5444.2 1877.55  5563.2 1879.89  5647.7 1880.04  5676.3 1881.01  5798.7 1882.38
#Mann=8,-1,0
  4495.5   0.035       0  4647.8    0.07       0  4822.8   0.035       0
  4989.2    0.07       0  5000.5    0.07       0  5004.9    0.07       0
  5395.4   0.035       0  5444.2    0.07       0
Bank Sta=5000.5,5004.9
Exp/Cntr=0.3,0.1

Type RM Length L Ch R = 1,4164,603,603,603
BEGIN DESCRIPTION:
Mapping XS f05b1b82
END DESCRIPTION:
XS GIS Cut Line= 3
      1440819.49      6914614.43      1441029.97      6914141.38
      1441316.45      6913464.25
#Sta/Elev= 30
  4479.1 1879.40  4671.9 1877.55  4729.4 1875.95  4747.2 1876.24  4891.1 1873.35
  4897.6 1873.70  4934.9 1872.81  4967.3 1870.20  4972.8 1870.65  4993.8 1867.78
  4994.1 1867.28  4997.9 1867.28  4998.2 1867.78  5001.5 1868.56  5019.7 1869.95
  5033.1 1869.10  5043.4 1869.81  5072.5 1869.53  5078.0 1868.95  5130.8 1872.07
  5278.3 1874.50  5315.4 1874.91  5337.1 1874.37  5369.7 1875.58  5460.5 1876.77
  5478.3 1876.48  5489.6 1877.13  5562.8 1878.03  5566.8 1878.08  5732.1 1879.58
#Mann=5,-1,0
  4479.1    0.07       0  4993.8    0.07       0  4998.2    0.07       0
  5562.8   0.045       0  5566.8    0.07       0
Bank Sta=4993.8,4998.2
Exp/Cntr=0.3,0.1

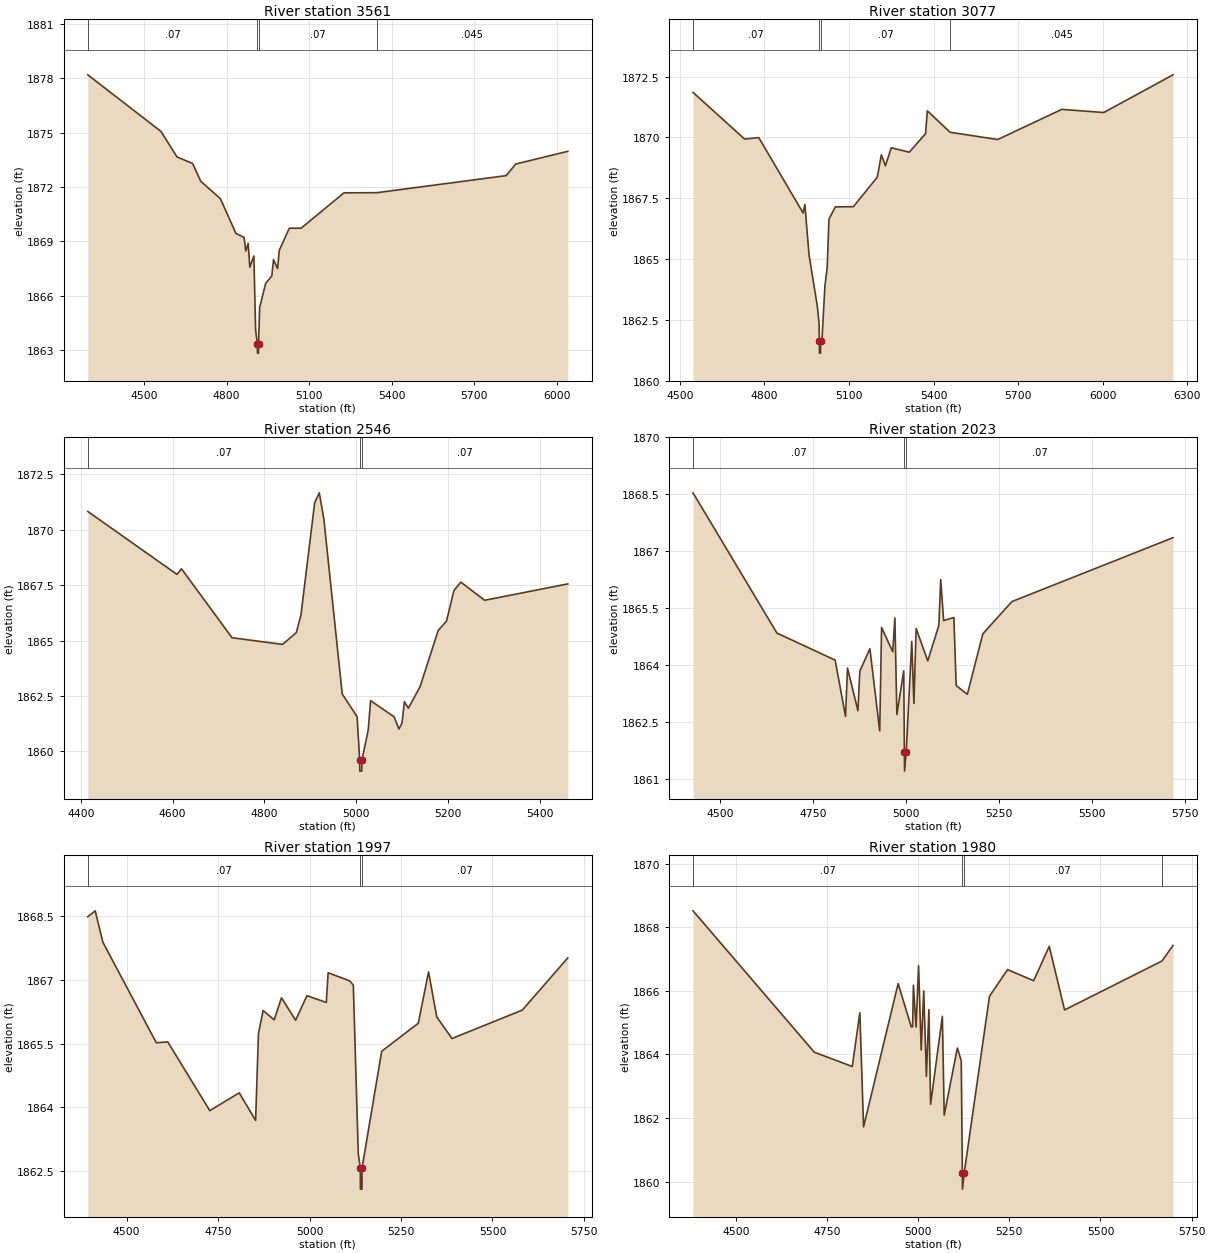
Type RM Length L Ch R = 1,3561,484,484,484
BEGIN DESCRIPTION:
Dry Creek Trib1 5.0
END DESCRIPTION:
XS GIS Cut Line= 3
      1440858.53      6914772.89      1441432.25      6914364.56
      1442112.90      6913579.28
#Sta/Elev= 30
  4295.8 1878.19  4561.5 1875.07  4620.0 1873.66  4676.6 1873.30  4706.1 1872.32
  4777.4 1871.36  4834.0 1869.44  4863.5 1869.22  4869.6 1868.47  4878.2 1868.89
  4884.4 1867.58  4899.1 1868.20  4905.3 1864.13  4911.7 1863.34  4912.0 1862.84
  4915.8 1862.84  4916.1 1863.34  4920.0 1865.36  4942.0 1866.69  4964.3 1867.10
  4970.4 1868.00  4985.2 1867.50  4991.3 1868.51  5027.8 1869.73  5070.6 1869.73
  5226.3 1871.68  5346.5 1871.69  5815.2 1872.63  5850.3 1873.27  6039.2 1873.97
#Mann=4,-1,0
  4295.8    0.07       0  4911.7    0.07       0  4916.1    0.07       0
  5346.5   0.045       0
Bank Sta=4911.7,4916.1
Exp/Cntr=0.3,0.1

Type RM Length L Ch R = 1,3077,531,531,531
BEGIN DESCRIPTION:
Dry Creek Trib1 4.0
END DESCRIPTION:
XS GIS Cut Line= 3
      1441194.88      6914961.71      1441564.52      6914699.16
      1442344.88      6913722.79
#Sta/Elev= 30
  4546.6 1871.85  4729.5 1869.93  4779.8 1869.99  4937.3 1866.89  4943.5 1867.24
  4958.2 1865.18  4987.8 1863.05  4993.9 1862.34  4995.0 1861.63  4995.3 1861.13
  4999.1 1861.13  4999.5 1861.63  5003.9 1861.63  5014.7 1863.89  5022.7 1864.67
  5029.1 1866.64  5051.6 1867.14  5115.6 1867.15  5200.4 1868.36  5214.9 1869.28
  5229.3 1868.83  5250.1 1869.57  5314.1 1869.39  5371.7 1870.15  5378.1 1871.09
  5458.7 1870.21  5627.9 1869.91  5855.2 1871.15  6004.1 1871.02  6249.9 1872.57
#Mann=4,-1,0
  4546.6    0.07       0  4995.0    0.07       0  4999.5    0.07       0
  5458.7   0.045       0
Bank Sta=4995,4999.5
Exp/Cntr=0.3,0.1

Type RM Length L Ch R = 1,2546,523,523,523
BEGIN DESCRIPTION:
Mapping XS bb507c97
END DESCRIPTION:
XS GIS Cut Line= 3
      1441270.91      6914950.84      1441854.63      6914970.37
      1442299.50      6914846.68
#Sta/Elev= 30
  4415.4 1870.83  4609.6 1867.99  4619.6 1868.24  4729.7 1865.13  4839.7 1864.83
  4869.7 1865.36  4879.8 1866.15  4909.8 1871.23  4919.8 1871.67  4929.8 1870.48
  4969.8 1862.59  5002.2 1861.57  5007.8 1859.61  5008.1 1859.11  5012.3 1859.11
  5012.7 1859.61  5026.4 1860.97  5031.6 1862.29  5082.9 1861.56  5093.2 1861.01
  5100.0 1861.27  5105.2 1862.24  5114.0 1861.95  5139.5 1862.93  5178.9 1865.46
  5197.0 1865.88  5213.1 1867.26  5228.2 1867.64  5280.1 1866.82  5461.2 1867.56
#Mann=3,-1,0
  4415.4    0.07       0  5007.8    0.07       0  5012.7    0.07       0
Bank Sta=5007.8,5012.7
Exp/Cntr=0.3,0.1

Type RM Length L Ch R = 1,2023,26,26,26
BEGIN DESCRIPTION:
Mapping XS 6ee91483
END DESCRIPTION:
XS GIS Cut Line= 6
      1441318.63      6915326.29      1441759.14      6915456.49
      1441867.65      6915452.14      1441893.69      6915436.95
      1441898.03      6915330.62      1442264.75      6914879.26
#Sta/Elev= 30
  4426.9 1868.54  4652.5 1864.85  4808.9 1864.14  4836.8 1862.66  4842.1 1863.93
  4870.1 1862.81  4875.3 1863.85  4902.3 1864.44  4928.7 1862.28  4933.7 1865.00
  4963.7 1864.36  4969.4 1865.25  4974.8 1862.71  4993.3 1863.86  4995.0 1861.72
  4995.4 1861.22  4999.9 1861.72  5014.8 1864.63  5020.6 1863.00  5026.6 1864.97
  5057.8 1864.12  5087.6 1865.05  5092.6 1866.26  5100.5 1865.18  5128.0 1865.26
  5134.2 1863.47  5164.2 1863.24  5205.8 1864.83  5284.1 1865.68  5717.0 1867.36
#Mann=3,-1,0
  4426.9    0.07       0  4995.0    0.07       0  4999.9    0.07       0
Bank Sta=4995,4999.9
Exp/Cntr=0.3,0.1

Type RM Length L Ch R = 1,1997,17,17,17
BEGIN DESCRIPTION:
Mapping XS 48ce3c95
END DESCRIPTION:
XS GIS Cut Line= 6
      1441305.56      6915343.63      1441754.80      6915478.19
      1441885.01      6915473.85      1441908.88      6915441.29
      1441917.56      6915352.32      1442279.95      6914898.78
#Sta/Elev= 30
  4393.9 1868.49  4414.2 1868.63  4435.1 1867.89  4581.2 1865.52  4612.5 1865.54
  4727.4 1863.92  4807.8 1864.34  4852.6 1863.69  4860.4 1865.74  4873.1 1866.28
  4903.3 1866.06  4923.3 1866.58  4961.9 1866.05  4992.9 1866.63  5045.8 1866.47
  5050.8 1867.17  5109.5 1866.98  5119.6 1866.88  5133.2 1862.91  5138.7 1862.57
  5139.1 1862.07  5143.3 1862.07  5143.6 1862.57  5197.2 1865.32  5297.2 1865.98
  5325.3 1867.19  5347.7 1866.13  5389.3 1865.62  5581.5 1866.29  5705.8 1867.52
#Mann=3,-1,0
  4393.9    0.07       0  5138.7    0.07       0  5143.6    0.07       0
Bank Sta=5138.7,5143.6
Exp/Cntr=0.3,0.1

Type RM Length L Ch R = 1,1980,501,501,501
BEGIN DESCRIPTION:
Mapping XS 01c4fe4b
END DESCRIPTION:
XS GIS Cut Line= 6
      1441305.55      6915374.01      1441756.97      6915504.23
      1441887.18      6915493.38      1441926.24      6915456.49
      1441952.28      6915350.15      1442300.82      6914925.84
#Sta/Elev= 30
  4382.9 1868.52  4715.4 1864.07  4819.5 1863.62  4840.3 1865.31  4850.5 1861.72
  4945.3 1866.23  4981.2 1864.87  4984.9 1864.87  4987.1 1866.18  4994.4 1864.86
  5001.3 1866.79  5008.5 1864.14  5015.4 1866.00  5022.7 1863.31  5029.6 1865.41
  5034.3 1862.43  5066.5 1865.20  5071.6 1862.09  5107.6 1864.20  5118.3 1863.80
  5121.4 1860.26  5121.7 1859.76  5126.3 1860.26  5195.7 1865.83  5245.2 1866.67
  5316.9 1866.32  5359.6 1867.40  5401.6 1865.40  5668.6 1866.94  5698.9 1867.43
#Mann=4,-1,0
  4382.9    0.07       0  5121.4    0.07       0  5126.3    0.07       0
  5668.6   0.035       0
Bank Sta=5121.4,5126.3
Exp/Cntr=0.3,0.1

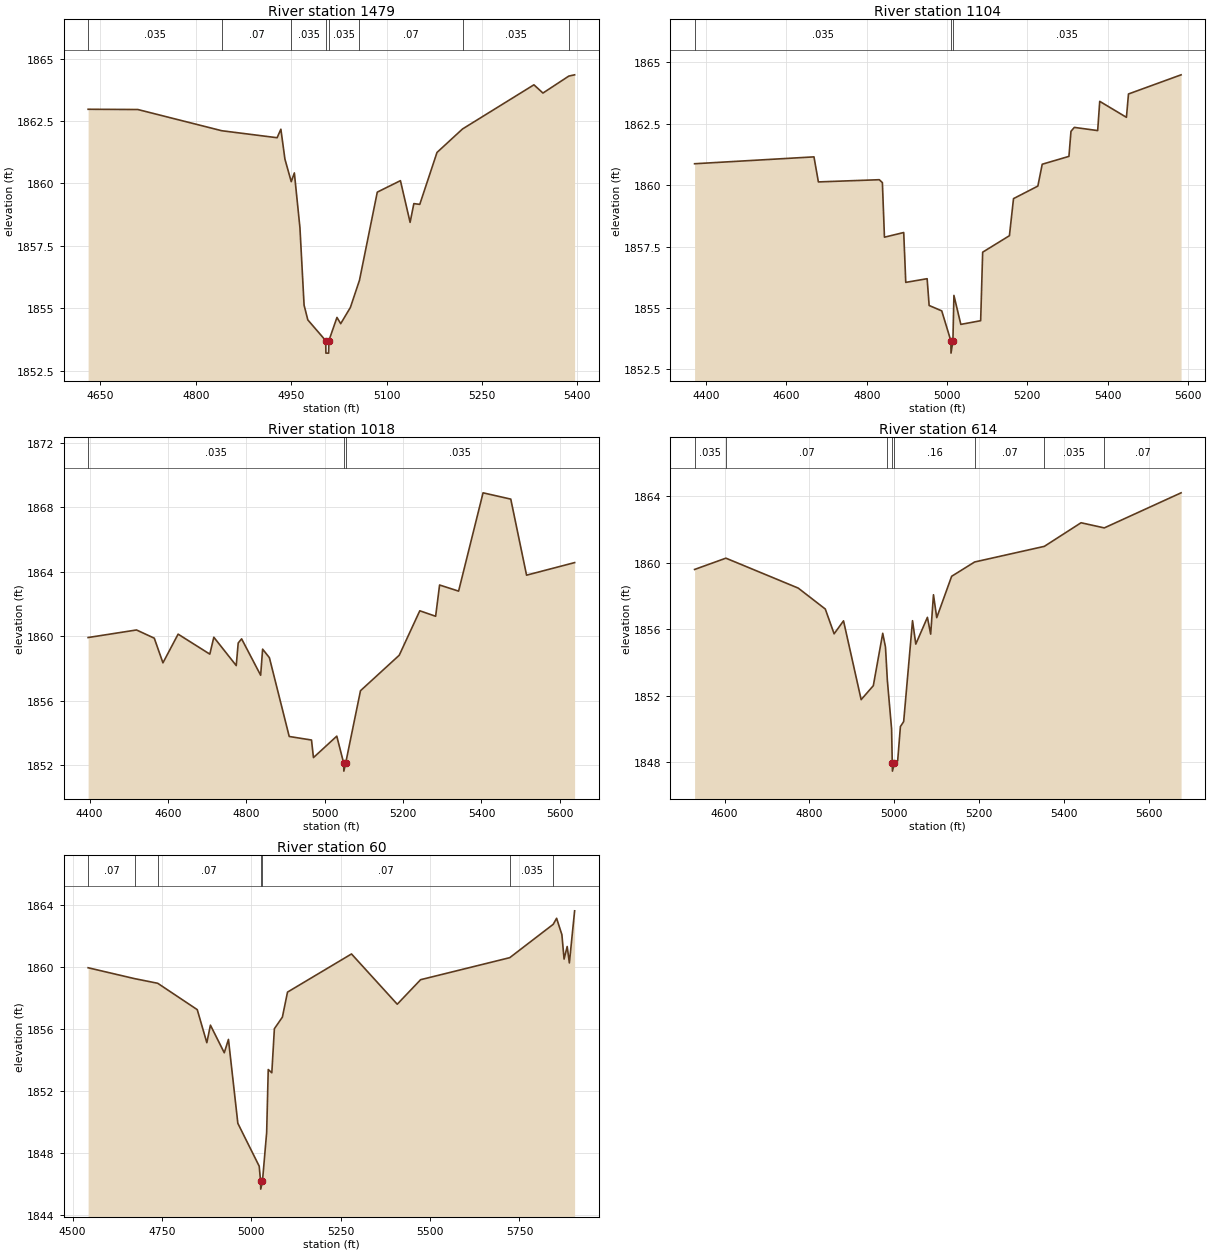
Type RM Length L Ch R = 1,1479,375,375,375
BEGIN DESCRIPTION:
Mapping XS dc0faa33
END DESCRIPTION:
XS GIS Cut Line= 3
      1441698.74      6916189.90      1441896.77      6915875.44
      1442108.74      6915544.05
#Sta/Elev= 30
  4630.7 1862.97  4708.9 1862.96  4840.9 1862.11  4927.9 1861.83  4933.8 1862.17
  4940.2 1860.97  4950.1 1860.07  4955.0 1860.42  4963.8 1858.22  4970.3 1855.12
  4976.2 1854.53  5004.3 1853.70  5004.6 1853.20  5008.9 1853.20  5009.3 1853.70
  5022.0 1854.63  5027.9 1854.38  5043.1 1855.03  5057.4 1856.12  5085.4 1859.65
  5121.8 1860.11  5137.0 1858.44  5142.9 1859.19  5152.2 1859.16  5179.3 1861.24
  5219.4 1862.18  5331.7 1863.95  5345.9 1863.62  5386.6 1864.30  5395.7 1864.35
#Mann=8,-1,0
  4630.7   0.035       0  4840.9    0.07       0  4950.1   0.035       0
  5004.3   0.035       0  5009.3   0.035       0  5057.4    0.07       0
  5219.4   0.035       0  5386.6    0.07       0
Bank Sta=5004.3,5009.3
Exp/Cntr=0.3,0.1

Type RM Length L Ch R = 1,1104,86,86,86
BEGIN DESCRIPTION:
Mapping XS 6ecefbe7
END DESCRIPTION:
XS GIS Cut Line= 3
      1442065.13      6916680.44      1442175.81      6916077.14
      1442258.27      6915484.72
#Sta/Elev= 30
  4371.4 1860.87  4668.7 1861.15  4679.7 1860.13  4831.4 1860.22  4839.1 1860.10
  4844.2 1857.88  4892.2 1858.07  4897.3 1856.04  4950.5 1856.19  4955.5 1855.10
  4986.9 1854.88  5009.6 1853.66  5010.0 1853.16  5014.7 1853.66  5017.2 1855.51
  5034.4 1854.33  5083.8 1854.48  5088.8 1857.27  5155.4 1857.94  5165.6 1859.45
  5226.2 1859.96  5237.1 1860.85  5303.6 1861.17  5308.7 1862.19  5317.1 1862.35
  5375.2 1862.22  5380.3 1863.41  5446.8 1862.76  5451.9 1863.71  5582.9 1864.49
#Mann=3,-1,0
  4371.4   0.035       0  5009.6   0.035       0  5014.7   0.035       0
Bank Sta=5009.6,5014.7
Exp/Cntr=0.3,0.1

Type RM Length L Ch R = 1,1018,404,404,404
BEGIN DESCRIPTION:
Mapping XS a7c1caae
END DESCRIPTION:
XS GIS Cut Line= 3
      1442160.62      6916684.75      1442251.76      6916109.70
      1442338.57      6915456.47
#Sta/Elev= 30
  4396.4 1859.92  4519.9 1860.39  4565.2 1859.88  4587.3 1858.35  4626.0 1860.13
  4706.9 1858.89  4717.1 1859.94  4774.3 1858.18  4779.3 1859.58  4788.0 1859.84
  4836.6 1857.58  4841.6 1859.20  4858.9 1858.67  4909.5 1853.78  4966.3 1853.56
  4971.3 1852.47  5030.8 1853.80  5048.4 1852.13  5048.8 1851.63  5053.5 1852.13
  5091.3 1856.62  5190.1 1858.82  5242.6 1861.58  5283.0 1861.24  5293.1 1863.18
  5341.6 1862.80  5404.0 1868.90  5474.7 1868.51  5515.0 1863.79  5637.6 1864.57
#Mann=3,-1,0
  4396.4   0.035       0  5048.4   0.035       0  5053.5   0.035       0
Bank Sta=5048.4,5053.5
Exp/Cntr=0.3,0.1

Type RM Length L Ch R = 1,614,554,554,554
BEGIN DESCRIPTION:
Mapping XS 3c16e32c
END DESCRIPTION:
XS GIS Cut Line= 3
      1442204.03      6916610.98      1442503.50      6916246.42
      1442940.94      6915731.02
#Sta/Elev= 30
  4529.0 1859.59  4602.9 1860.27  4773.5 1858.47  4837.4 1857.21  4858.2 1855.72
  4880.4 1856.50  4922.0 1851.76  4950.7 1852.60  4972.9 1855.75  4979.4 1854.92
  4983.8 1852.92  4993.8 1850.00  4995.4 1847.96  4995.8 1847.46  5000.6 1847.96
  5008.1 1848.07  5014.6 1850.14  5022.3 1850.44  5043.2 1856.51  5050.9 1855.10
  5078.3 1856.71  5086.0 1855.70  5092.6 1858.07  5100.3 1856.69  5135.5 1859.18
  5189.7 1860.04  5354.2 1860.98  5440.8 1862.40  5495.6 1862.09  5676.8 1864.20
#Mann=8,-1,0
  4529.0   0.035       0  4602.9    0.07       0  4983.8    0.16       0
  4995.4    0.07       0  5000.6    0.16       0  5189.7    0.07       0
  5354.2   0.035       0  5495.6    0.07       0
Bank Sta=4995.4,5000.6
Exp/Cntr=0.3,0.1

Type RM Length L Ch R = 1,60,0,0,0
BEGIN DESCRIPTION:
Dry Creek Trib1 1.0
END DESCRIPTION:
XS GIS Cut Line= 4
      1442355.45      6916615.33      1442772.16      6916667.42
      1442825.64      6916600.94      1443319.08      6915901.81
#Sta/Elev= 30
  4543.3 1859.95  4673.1 1859.25  4738.0 1858.95  4848.6 1857.25  4875.4 1855.12
  4885.5 1856.25  4924.2 1854.47  4935.9 1855.33  4962.2 1849.92  5021.9 1847.16
  5025.8 1846.18  5026.2 1845.68  5031.0 1846.18  5042.8 1849.34  5047.2 1853.39
  5057.2 1853.18  5064.4 1856.02  5086.8 1856.77  5101.1 1858.38  5280.1 1860.84
  5408.1 1857.60  5473.4 1859.18  5722.8 1860.60  5844.4 1862.75  5853.9 1863.14
  5868.7 1862.08  5874.8 1860.51  5883.5 1861.32  5889.6 1860.26  5904.3 1863.62
#Mann=7,-1,0
  4543.3    0.07       0  4673.1    0.16       0  4738.0    0.07       0
  5025.8    0.07       0  5031.0    0.07       0  5722.8   0.035       0
  5844.4    0.07       0
Bank Sta=5025.8,5031
Exp/Cntr=0.3,0.1

Chan Stop Cuts=-1