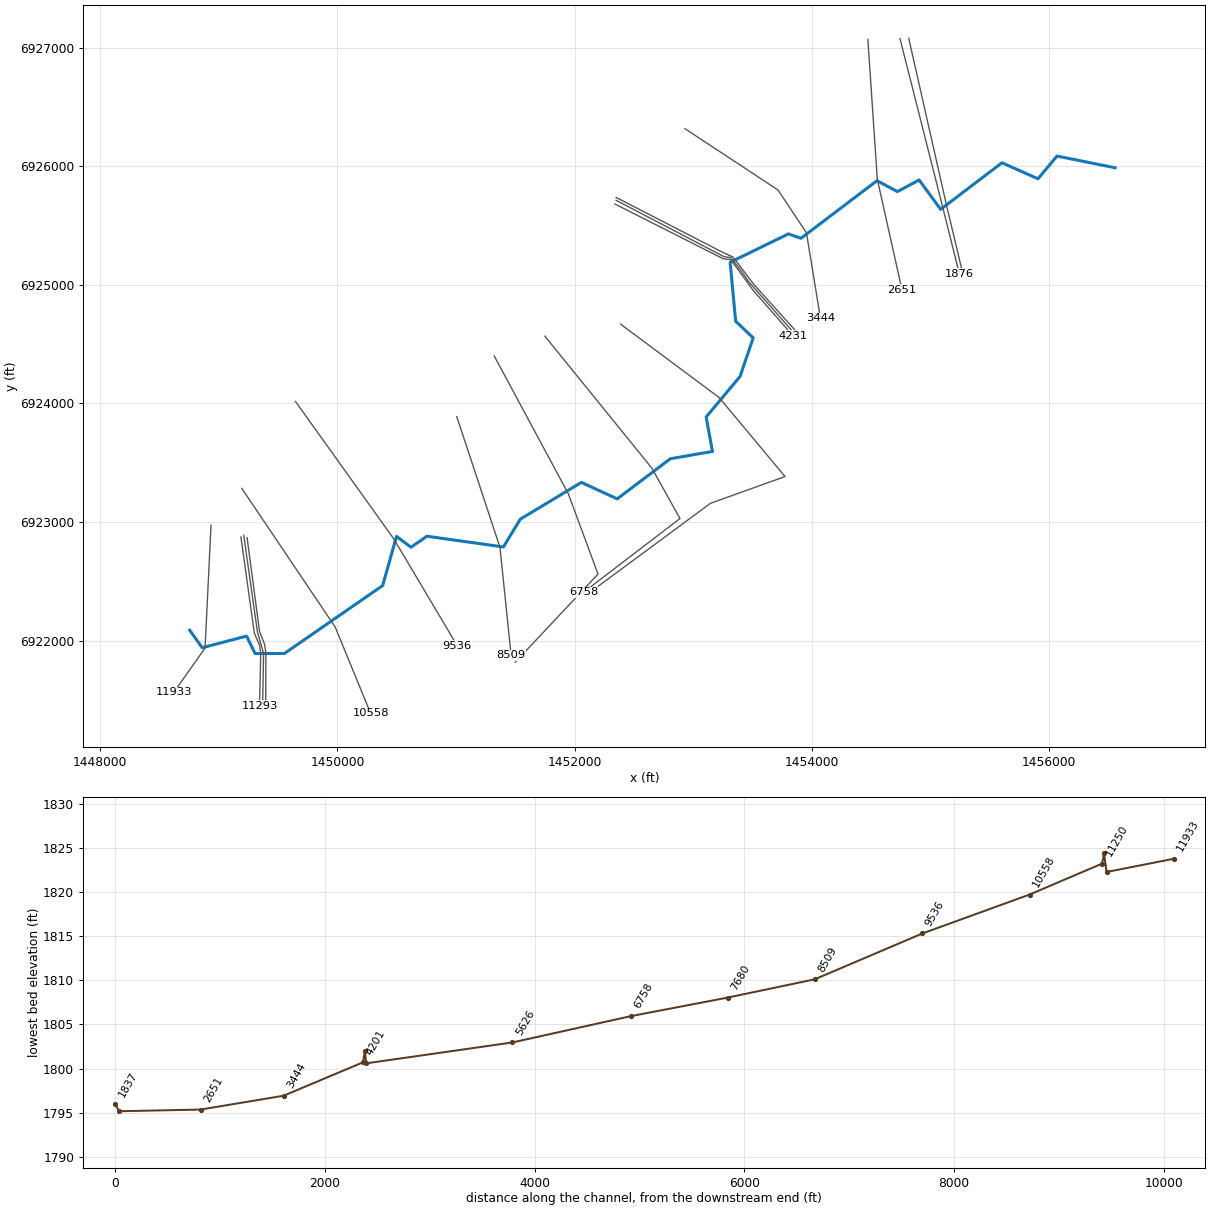
--- Dry Creek Trib2.prj (project) ---

Proj Title=Dry Creek Trib2 Base Level Engineering
Current Plan=p01
Default Exp/Contr=0.3,0.1
English Units
Geom File=g01
Flow File=f01
Plan File=p01
BEGIN DESCRIPTION:
Dry Creek Trib2
END DESCRIPTION:

--- Dry Creek Trib2.p01 (plan) ---

Plan Title=Multiple Run
Short Identifier=Multiple
Geom File=g01
Flow File=f01
Subcritical Flow
K Sum by GR= 0
Std Step Tol= 0.01
Critical Tol= 0.01
Num of Std Step Trials= 20
Max Error Tol= 0.3
Flow Tol Ratio= 0.001
Split Flow NTrial= 30
Split Flow Tol= 0.02
Split Flow Ratio= 0.02
Log Output Level= 0
Friction Slope Method= 1
Unsteady Friction Slope Method= 2
Unsteady Bridges Friction Slope Method= 1
Parabolic Critical Depth
Global Vel Dist=  1 , 1 , 1
Global Log Level= 0
CheckData=True
Encroach Param= -1, 0, 0, 0
BEGIN DESCRIPTION:
Multiple Run
END DESCRIPTION:

--- Dry Creek Trib2.f01 (steady flow) ---

Flow Title=Multiple
Number of Profiles=7
Profile Names=10-year,25-year,50-year,1pct_min,100-year,1pct_plu,500-year
River Rch & RM= Dry Creek Trib2,Reach-1,11933
     216     295     359     217     434     866     640
River Rch & RM= Dry Creek Trib2,Reach-1,11293
     296     410     503     306     611    1220     915
River Rch & RM= Dry Creek Trib2,Reach-1,3444
     313     435     535     326     651    1300     978
River Rch & RM= Dry Creek Trib2,Reach-1,2651
     375     526     651     400     798    1592    1214
Boundary for River Rch & Prof#=Dry Creek Trib2,Reach-1,1
Up Type=0
Dn Type=3
Dn Slope=0.005
Boundary for River Rch & Prof#=Dry Creek Trib2,Reach-1,2
Up Type=0
Dn Type=3
Dn Slope=0.005
Boundary for River Rch & Prof#=Dry Creek Trib2,Reach-1,3
Up Type=0
Dn Type=3
Dn Slope=0.005
Boundary for River Rch & Prof#=Dry Creek Trib2,Reach-1,4
Up Type=0
Dn Type=3
Dn Slope=0.005
Boundary for River Rch & Prof#=Dry Creek Trib2,Reach-1,5
Up Type=0
Dn Type=3
Dn Slope=0.005
Boundary for River Rch & Prof#=Dry Creek Trib2,Reach-1,6
Up Type=0
Dn Type=3
Dn Slope=0.005
Boundary for River Rch & Prof#=Dry Creek Trib2,Reach-1,7
Up Type=0
Dn Type=3
Dn Slope=0.005

--- Dry Creek Trib2.g01 (geometry) ---

Geom Title=Existing Conditions

River Reach=Dry Creek Trib2,Reach-1
Reach XY= 30
      1448755.00      6922088.00      1448860.85      6921940.04
      1449234.85      6922038.33      1449306.22      6921891.44
      1449553.75      6921891.45      1450381.99      6922464.53
      1450498.29      6922879.04      1450620.36      6922787.91
      1450755.00      6922880.45      1451399.35      6922789.97
      1451541.76      6923024.38      1452056.47      6923334.47
      1452358.33      6923195.60      1452806.58      6923534.18
      1453161.38      6923595.37      1453108.31      6923886.27
      1453393.76      6924228.00      1453504.99      6924553.47
      1453356.98      6924693.67      1453310.45      6925191.01
      1453801.60      6925430.17      1453907.28      6925393.13
      1454548.05      6925879.16      1454720.08      6925787.22
      1454903.57      6925884.99      1455084.77      6925637.50
      1455601.67      6926030.38      1455905.02      6925895.08
      1456065.28      6926087.01      1456555.00      6925988.00

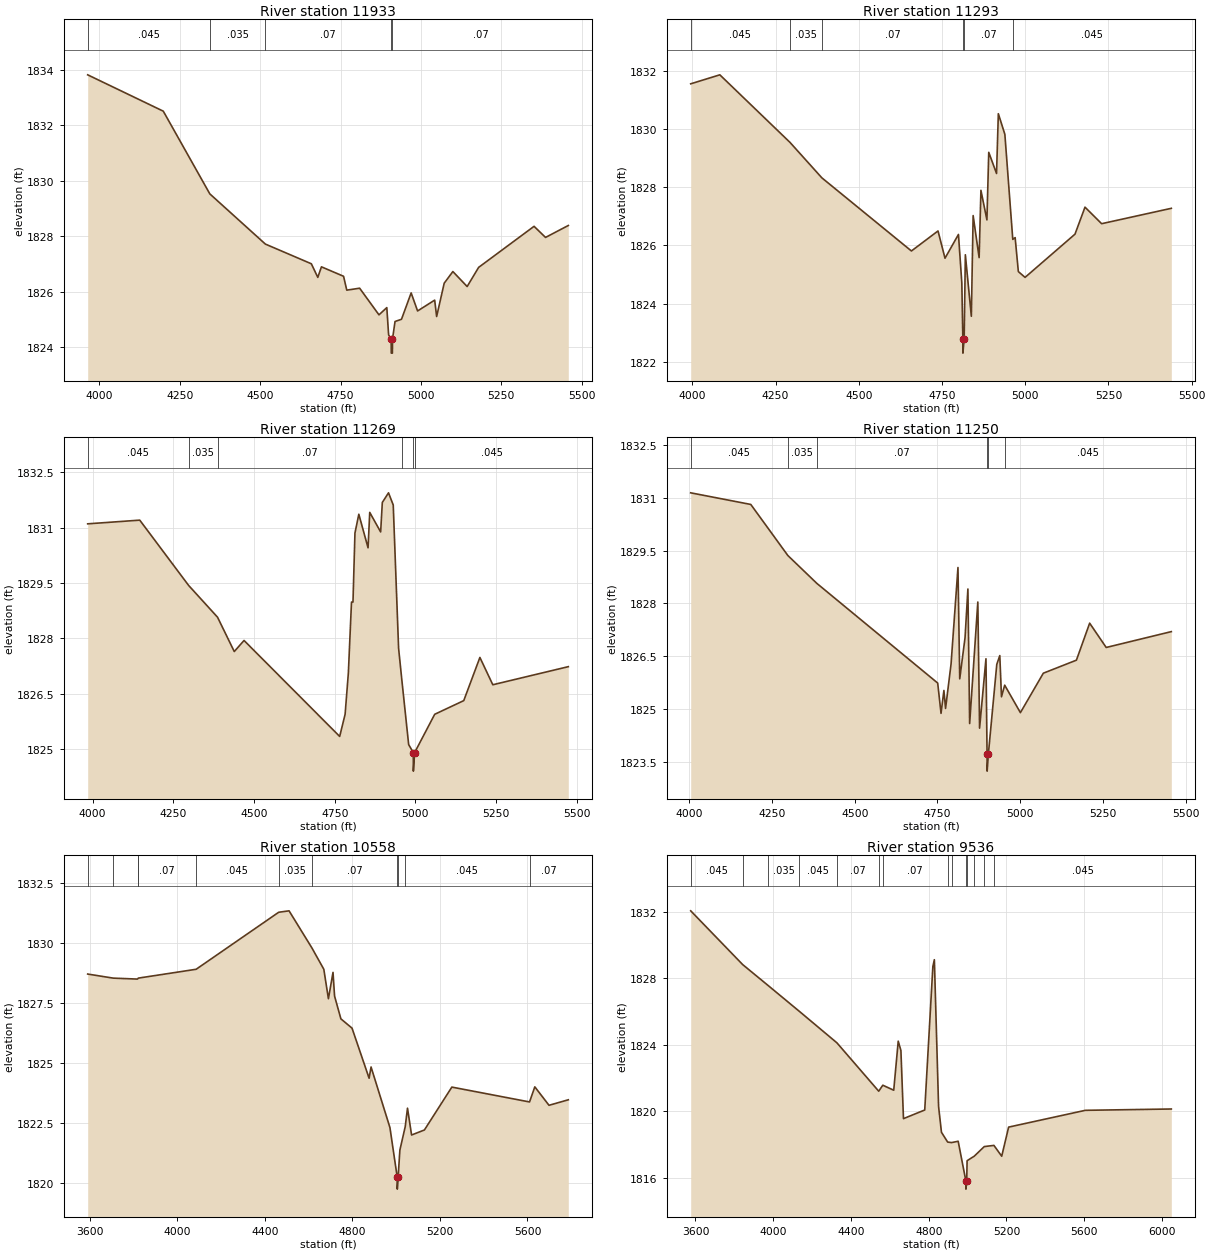
Type RM Length L Ch R = 1,11933,640,640,640
BEGIN DESCRIPTION:
Dry Creek Trib2 3.0
END DESCRIPTION:
XS GIS Cut Line= 3
      1448935.03      6922972.82      1448884.83      6921937.53
      1448620.72      6921562.99
#Sta/Elev= 30
  3963.5 1833.82  4198.6 1832.51  4343.3 1829.53  4516.1 1827.72  4659.1 1827.01
  4679.2 1826.52  4690.5 1826.90  4759.3 1826.56  4769.3 1826.06  4809.3 1826.13
  4869.4 1825.17  4893.8 1825.43  4899.4 1824.45  4907.4 1824.29  4907.7 1823.79
  4911.2 1823.79  4911.4 1824.29  4919.4 1824.93  4939.5 1825.01  4969.5 1825.96
  4989.5 1825.31  5042.7 1825.70  5048.8 1825.11  5072.3 1826.31  5099.3 1826.73
  5143.7 1826.19  5179.4 1826.88  5351.8 1828.36  5387.5 1827.96  5458.3 1828.39
#Mann=5,-1,0
  3963.5   0.045       0  4343.3   0.035       0  4516.1    0.07       0
  4907.4    0.07       0  4911.4    0.07       0
Bank Sta=4907.4,4911.4
Exp/Cntr=0.3,0.1

Type RM Length L Ch R = 1,11293,24,24,24
BEGIN DESCRIPTION:
Mapping XS 73b1d36f
END DESCRIPTION:
XS GIS Cut Line= 5
      1449187.11      6922874.65      1449299.96      6922062.98
      1449343.37      6921963.16      1449354.22      6921895.88
      1449343.37      6921448.78
#Sta/Elev= 30
  3995.2 1831.57  4082.7 1831.88  4293.6 1829.55  4389.2 1828.33  4658.2 1825.81
  4738.1 1826.50  4759.1 1825.56  4799.5 1826.38  4809.6 1824.71  4812.7 1822.79
  4812.9 1822.29  4816.7 1822.79  4820.2 1825.68  4838.2 1823.56  4843.6 1827.03
  4861.6 1825.58  4867.0 1827.90  4885.0 1826.88  4890.5 1829.21  4913.9 1828.48
  4919.3 1830.54  4938.9 1829.83  4962.7 1826.21  4969.8 1826.27  4979.4 1825.10
  4999.6 1824.90  5149.6 1826.39  5179.6 1827.32  5229.6 1826.75  5438.9 1827.28
#Mann=6,-1,0
  3995.2   0.045       0  4293.6   0.035       0  4389.2    0.07       0
  4812.7   0.045       0  4816.7    0.07       0  4962.7   0.045       0
Bank Sta=4812.7,4816.7
Exp/Cntr=0.3,0.1

Type RM Length L Ch R = 1,11269,19,19,19
BEGIN DESCRIPTION:
Mapping XS 62d041ea
END DESCRIPTION:
XS GIS Cut Line= 4
      1449210.98      6922887.67      1449326.01      6922073.83
      1449378.09      6921891.54      1449369.41      6921414.13
#Sta/Elev= 30
  3984.7 1831.10  4146.0 1831.20  4297.5 1829.43  4387.0 1828.57  4438.8 1827.64
  4469.1 1827.94  4765.4 1825.34  4782.2 1825.94  4792.3 1827.06  4802.0 1828.98
  4806.6 1828.98  4812.7 1830.85  4824.7 1831.36  4853.3 1830.45  4858.5 1831.41
  4892.3 1830.88  4897.5 1831.68  4916.7 1831.94  4931.3 1831.61  4947.9 1827.73
  4957.6 1826.90  4979.1 1825.12  4993.5 1824.90  4993.7 1824.40  4997.5 1824.90
  5059.8 1825.94  5149.8 1826.31  5199.8 1827.48  5239.8 1826.74  5473.7 1827.23
#Mann=6,-1,0
  3984.7   0.045       0  4297.5   0.035       0  4387.0    0.07       0
  4957.6   0.045       0  4993.5   0.045       0  4997.5   0.045       0
Bank Sta=4993.5,4997.5
Exp/Cntr=0.3,0.1

Type RM Length L Ch R = 1,11250,692,692,692
BEGIN DESCRIPTION:
Mapping XS 0a878273
END DESCRIPTION:
XS GIS Cut Line= 5
      1449239.20      6922868.08      1449343.37      6922080.34
      1449386.77      6921967.50      1449397.62      6921891.54
      1449395.46      6921431.17
#Sta/Elev= 30
  4004.1 1831.14  4185.7 1830.81  4297.8 1829.36  4385.3 1828.57  4750.6 1825.74
  4760.7 1824.88  4769.4 1825.53  4774.4 1825.02  4791.0 1826.28  4811.9 1829.02
  4817.2 1825.86  4833.3 1827.03  4841.9 1828.41  4847.2 1824.59  4871.9 1828.04
  4877.2 1824.46  4896.5 1826.43  4899.8 1823.74  4900.1 1823.24  4903.9 1823.74
  4929.2 1826.27  4938.3 1826.52  4943.4 1825.35  4953.1 1825.68  5000.6 1824.90
  5069.9 1826.02  5169.9 1826.39  5209.9 1827.44  5259.9 1826.75  5456.7 1827.20
#Mann=6,-1,0
  4004.1   0.045       0  4297.8   0.035       0  4385.3    0.07       0
  4899.8   0.045       0  4903.9    0.07       0  4953.1   0.045       0
Bank Sta=4899.8,4903.9
Exp/Cntr=0.3,0.1

Type RM Length L Ch R = 1,10558,1022,1022,1022
BEGIN DESCRIPTION:
Dry Creek Trib2 2.0
END DESCRIPTION:
XS GIS Cut Line= 3
      1449194.39      6923284.04      1449981.82      6922114.29
      1450280.23      6921386.38
#Sta/Elev= 30
  3589.9 1828.71  3706.5 1828.54  3817.8 1828.50  3821.2 1828.54  4085.7 1828.91
  4462.9 1831.29  4510.3 1831.35  4614.8 1829.80  4669.2 1828.91  4690.2 1827.68
  4711.2 1828.78  4718.3 1827.79  4747.2 1826.84  4798.2 1826.45  4876.2 1824.36
  4885.1 1824.83  4971.4 1822.30  5004.7 1820.23  5005.0 1819.73  5008.8 1820.23
  5016.9 1821.36  5041.3 1822.34  5051.7 1823.11  5070.3 1821.99  5129.0 1822.20
  5254.4 1823.99  5609.5 1823.37  5633.6 1824.00  5698.5 1823.23  5786.7 1823.46
#Mann=11,-1,0
  3589.9   0.045       0  3706.5   0.035       0  3817.8   0.045       0
  3821.2    0.07       0  4085.7   0.045       0  4462.9   0.035       0
  4614.8    0.07       0  5004.7    0.07       0  5008.8    0.07       0
  5041.3   0.045       0  5609.5    0.07       0
Bank Sta=5004.7,5008.8
Exp/Cntr=0.3,0.1

Type RM Length L Ch R = 1,9536,1027,1027,1027
BEGIN DESCRIPTION:
Dry Creek Trib2 1.0
END DESCRIPTION:
XS GIS Cut Line= 3
      1449646.35      6924017.66      1450474.84      6922858.99
      1451009.79      6921957.69
#Sta/Elev= 30
  3575.6 1832.06  3842.7 1828.83  3973.7 1827.57  4133.9 1826.02  4327.8 1824.12
  4542.9 1821.21  4563.8 1821.57  4620.1 1821.27  4643.2 1824.22  4657.0 1823.66
  4670.2 1819.56  4779.6 1820.08  4821.4 1828.71  4829.1 1829.12  4850.8 1820.29
  4865.6 1818.74  4897.5 1818.15  4917.9 1818.12  4951.6 1818.20  4991.1 1815.82
  4991.4 1815.32  4995.6 1815.82  4997.5 1817.03  5034.1 1817.30  5086.0 1817.88
  5135.5 1817.95  5175.6 1817.30  5211.2 1819.05  5605.8 1820.06  6048.1 1820.14
#Mann=14,-1,0
  3575.6   0.045       0  3842.7    0.07       0  3973.7   0.035       0
  4133.9   0.045       0  4327.8    0.07       0  4542.9   0.045       0
  4563.8    0.07       0  4897.5   0.045       0  4917.9    0.07       0
  4991.1    0.07       0  4995.6    0.07       0  5034.1   0.045       0
  5086.0    0.07       0  5135.5   0.045       0
Bank Sta=4991.1,4995.6
Exp/Cntr=0.3,0.1

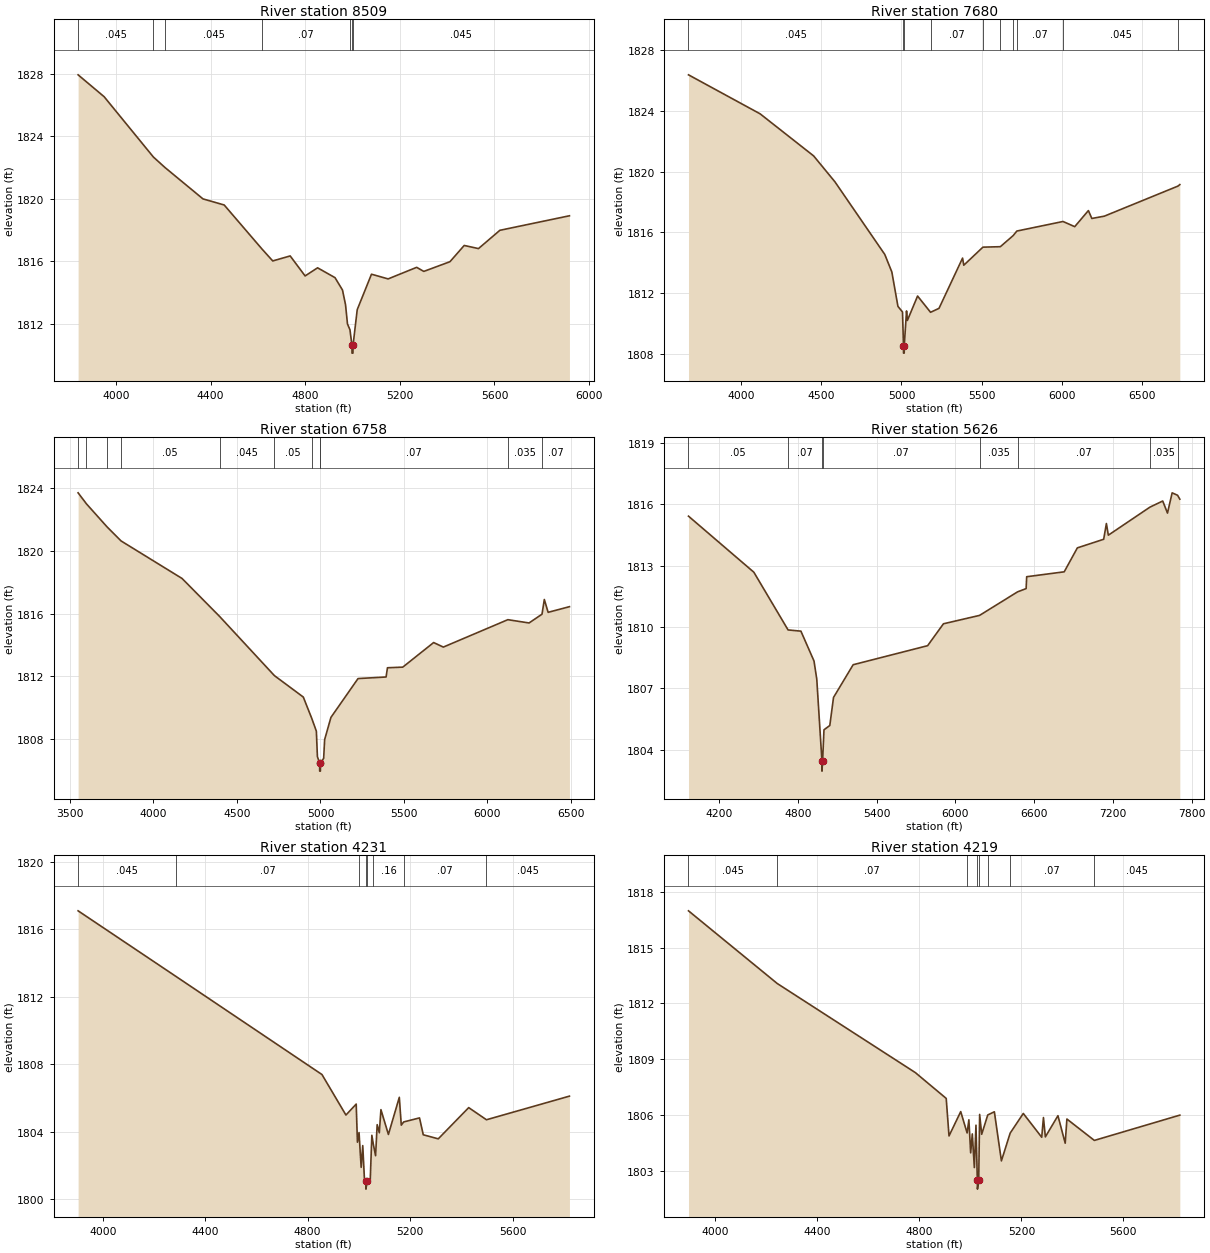
Type RM Length L Ch R = 1,8509,829,829,829
BEGIN DESCRIPTION:
Dry Creek Trib2 6.0
END DESCRIPTION:
XS GIS Cut Line= 3
      1451006.13      6923889.37      1451370.26      6922787.48
      1451464.47      6921875.44
#Sta/Elev= 30
  3839.5 1827.93  3949.5 1826.53  4157.8 1822.67  4206.7 1822.00  4367.5 1819.99
  4457.2 1819.60  4617.1 1816.78  4662.4 1816.02  4736.2 1816.34  4799.3 1815.06
  4852.0 1815.58  4925.7 1814.95  4957.3 1814.16  4970.2 1813.22  4978.4 1811.99
  4989.0 1811.61  4997.3 1810.62  4997.6 1810.12  5001.6 1810.12  5001.9 1810.62
  5019.6 1812.90  5079.9 1815.17  5150.3 1814.87  5270.9 1815.61  5301.1 1815.35
  5411.7 1815.97  5472.0 1817.01  5532.3 1816.81  5622.8 1817.98  5916.9 1818.91
#Mann=7,-1,0
  3839.5   0.045       0  4157.8   0.035       0  4206.7   0.045       0
  4617.1    0.07       0  4989.0   0.045       0  4997.3   0.045       0
  5001.9   0.045       0
Bank Sta=4997.3,5001.9
Exp/Cntr=0.3,0.1

Type RM Length L Ch R = 1,7680,922,922,922
BEGIN DESCRIPTION:
Mapping XS 55ae77bb
END DESCRIPTION:
XS GIS Cut Line= 4
      1451321.75      6924401.19      1451946.75      6923237.99
      1452196.75      6922560.91      1451499.42      6921818.48
#Sta/Elev= 30
  3673.1 1826.38  4119.5 1823.81  4452.7 1821.04  4584.9 1819.34  4895.9 1814.55
  4939.8 1813.40  4977.9 1811.13  5006.3 1810.76  5012.5 1808.55  5012.9 1808.05
  5016.9 1808.05  5017.2 1808.55  5031.4 1810.83  5036.7 1810.20  5100.2 1811.81
  5181.1 1810.74  5233.7 1811.00  5380.5 1814.31  5388.0 1813.84  5507.4 1815.03
  5615.8 1815.06  5695.6 1815.79  5718.6 1816.09  6006.2 1816.72  6079.3 1816.38
  6164.3 1817.44  6185.8 1816.92  6263.4 1817.07  6721.9 1819.05  6733.9 1819.15
#Mann=10,-1,0
  3673.1   0.045       0  5012.5   0.045       0  5017.2   0.045       0
  5181.1    0.07       0  5507.4   0.035       0  5615.8    0.07       0
  5695.6   0.035       0  5718.6    0.07       0  6006.2   0.045       0
  6721.9    0.07       0
Bank Sta=5012.5,5017.2
Exp/Cntr=0.3,0.1

Type RM Length L Ch R = 1,6758,1132,1132,1132
BEGIN DESCRIPTION:
Mapping XS 78e9fa2a
END DESCRIPTION:
XS GIS Cut Line= 4
      1451748.84      6924567.85      1452651.61      6923453.27
      1452887.72      6923029.66      1452075.18      6922408.10
#Sta/Elev= 30
  3548.8 1823.72  3598.5 1823.02  3721.8 1821.55  3805.8 1820.65  4171.5 1818.25
  4395.9 1815.83  4724.2 1812.05  4897.3 1810.68  4948.3 1809.31  4975.6 1808.50
  4981.8 1806.88  4995.2 1806.45  4995.5 1805.95  4999.7 1805.95  5000.1 1806.45
  5019.3 1806.77  5025.1 1807.96  5062.8 1809.38  5225.1 1811.86  5393.1 1811.96
  5401.3 1812.55  5493.0 1812.59  5677.9 1814.16  5735.9 1813.87  6122.3 1815.62
  6249.2 1815.41  6326.8 1815.97  6340.7 1816.91  6363.5 1816.09  6491.1 1816.45
#Mann=11,-1,0
  3548.8   0.045       0  3598.5    0.05       0  3721.8   0.035       0
  3805.8    0.05       0  4395.9   0.045       0  4724.2    0.05       0
  4948.3    0.07       0  4995.2    0.07       0  5000.1    0.07       0
  6122.3   0.035       0  6326.8    0.07       0
Bank Sta=4995.2,5000.1
Exp/Cntr=0.3,0.1

Type RM Length L Ch R = 1,5626,1395,1395,1395
BEGIN DESCRIPTION:
Mapping XS db03f2ee
END DESCRIPTION:
XS GIS Cut Line= 5
      1452387.73      6924668.54      1453217.58      6924050.49
      1453773.14      6923383.83      1453144.67      6923158.13
      1452200.25      6922460.23
#Sta/Elev= 30
  3965.5 1815.42  4463.7 1812.68  4724.5 1809.86  4822.4 1809.80  4922.2 1808.34
  4943.3 1807.45  4982.5 1803.46  4982.9 1802.96  4987.6 1803.46  4998.1 1804.98
  5042.5 1805.19  5070.8 1806.56  5220.5 1808.16  5788.0 1809.09  5908.5 1810.16
  6183.7 1810.57  6473.3 1811.72  6538.7 1811.88  6543.0 1812.46  6829.0 1812.70
  6929.2 1813.87  7129.7 1814.29  7150.5 1815.06  7165.2 1814.49  7482.2 1815.86
  7579.8 1816.16  7616.1 1815.57  7651.6 1816.56  7693.0 1816.44  7710.1 1816.25
#Mann=8,-1,0
  3965.5    0.05       0  4724.5    0.07       0  4982.5    0.07       0
  4987.6    0.07       0  6183.7   0.035       0  6473.3    0.07       0
  7482.2   0.035       0  7693.0    0.07       0
Bank Sta=4982.5,4987.6
Exp/Cntr=0.3,0.1

Type RM Length L Ch R = 1,4231,12,12,12
BEGIN DESCRIPTION:
Mapping XS 3b97278b
END DESCRIPTION:
XS GIS Cut Line= 6
      1452339.13      6925682.43      1453252.31      6925220.63
      1453314.81      6925213.69      1453384.25      6925119.94
      1453502.31      6924956.74      1453841.32      6924569.30
#Sta/Elev= 30
  3903.3 1817.08  4285.8 1813.19  4855.8 1807.38  4949.4 1804.98  4989.5 1805.63
  4994.3 1803.37  5000.6 1803.94  5008.9 1801.88  5015.1 1803.17  5021.5 1801.23
  5027.1 1801.09  5027.5 1800.59  5032.5 1801.09  5044.4 1801.15  5050.6 1803.78
  5056.6 1803.23  5065.2 1802.57  5071.4 1804.41  5079.8 1803.93  5086.1 1805.30
  5115.3 1803.83  5157.9 1806.03  5165.6 1804.38  5174.8 1804.57  5236.8 1804.81
  5251.5 1803.81  5310.1 1803.57  5428.9 1805.42  5498.3 1804.70  5822.4 1806.10
#Mann=8,-1,0
  3903.3   0.045       0  4285.8    0.07       0  5000.6   0.045       0
  5027.1    0.07       0  5032.5   0.045       0  5056.6    0.16       0
  5174.8    0.07       0  5498.3   0.045       0
Bank Sta=5027.1,5032.5
Exp/Cntr=0.3,0.1

Type RM Length L Ch R = 1,4219,18,18,18
BEGIN DESCRIPTION:
Mapping XS 7e1fcdf2
END DESCRIPTION:
XS GIS Cut Line= 6
      1452349.50      6925713.70      1453259.25      6925237.99
      1453314.81      6925231.05      1453398.14      6925126.88
      1453467.58      6925026.19      1453856.48      6924585.20
#Sta/Elev= 30
  3894.9 1816.98  4242.9 1813.07  4784.1 1808.28  4905.3 1806.89  4916.3 1804.87
  4962.2 1806.18  4987.3 1805.03  4994.2 1805.74  5001.2 1803.96  5007.6 1804.98
  5015.6 1803.17  5022.0 1805.45  5027.3 1802.51  5027.8 1802.01  5032.7 1802.51
  5036.4 1806.03  5044.4 1804.96  5068.2 1806.00  5094.1 1806.17  5121.7 1803.53
  5156.0 1805.02  5207.5 1806.08  5279.8 1804.80  5286.5 1805.86  5294.0 1804.82
  5343.4 1805.96  5371.8 1804.48  5378.5 1805.78  5486.1 1804.63  5821.2 1805.99
#Mann=8,-1,0
  3894.9   0.045       0  4242.9    0.07       0  4987.3   0.045       0
  5027.3   0.045       0  5032.7   0.045       0  5068.2    0.16       0
  5156.0    0.07       0  5486.1   0.045       0
Bank Sta=5027.3,5032.7
Exp/Cntr=0.3,0.1

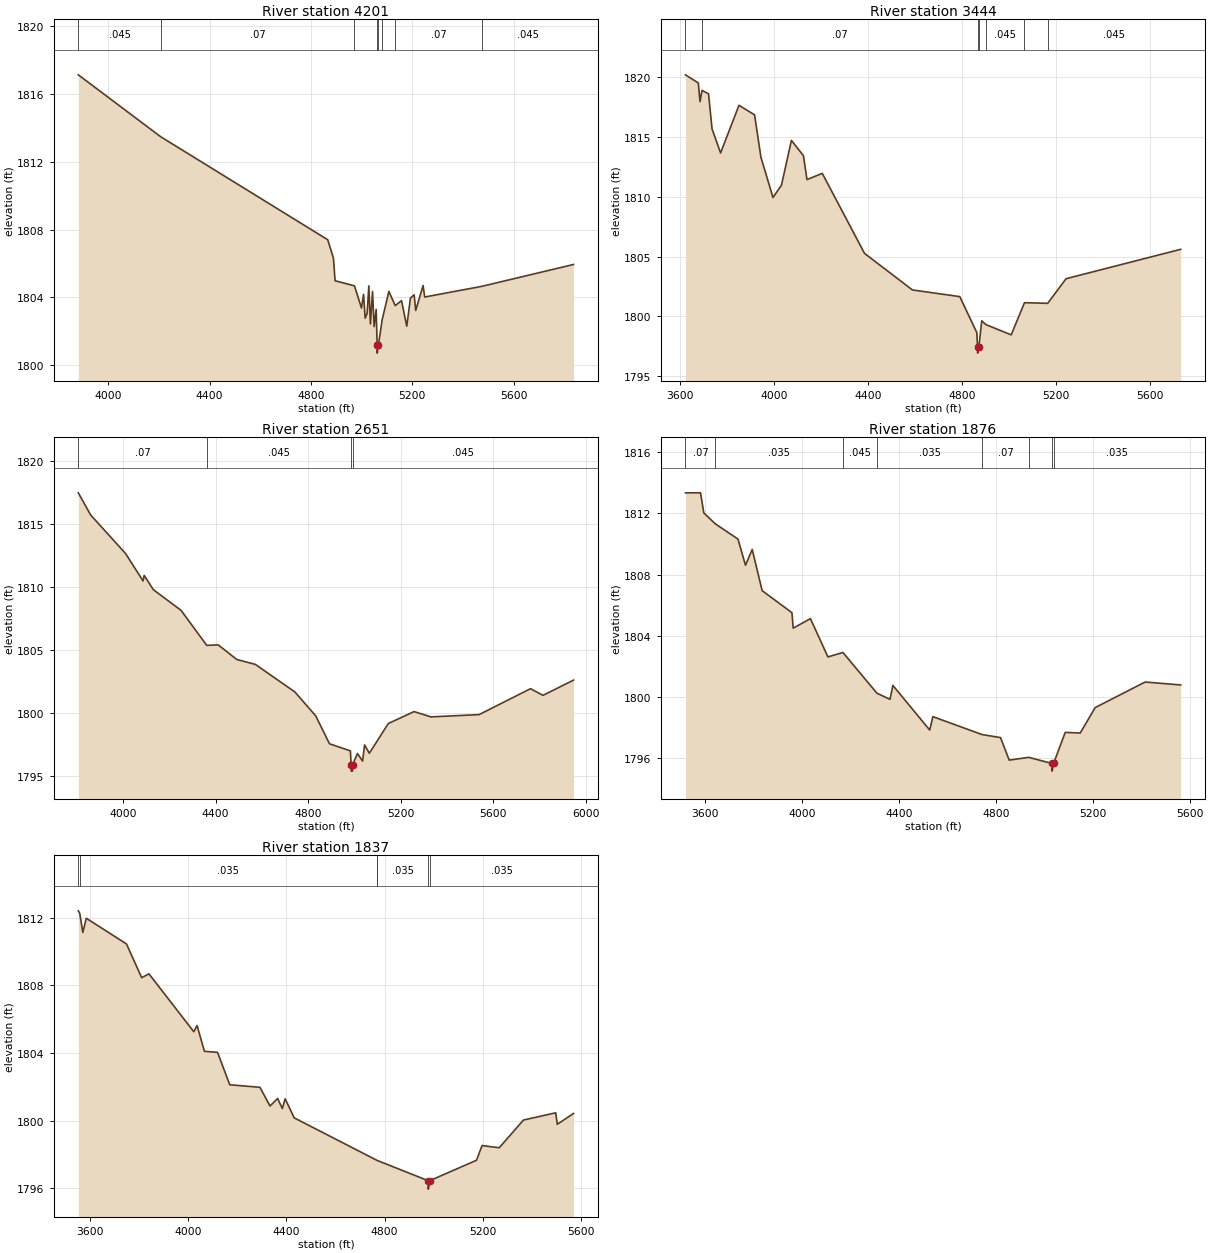
Type RM Length L Ch R = 1,4201,757,757,757
BEGIN DESCRIPTION:
Mapping XS 639486ff
END DESCRIPTION:
XS GIS Cut Line= 6
      1452349.51      6925738.01      1453252.31      6925272.72
      1453335.64      6925234.52      1453401.61      6925147.72
      1453509.25      6925005.36      1453884.26      6924588.68
#Sta/Elev= 30
  3881.4 1817.13  4206.5 1813.48  4866.3 1807.40  4888.8 1806.32  4895.4 1804.98
  4971.9 1804.68  4999.6 1803.37  5007.8 1804.18  5014.1 1802.77  5022.0 1803.06
  5028.6 1804.68  5034.9 1802.43  5043.2 1804.35  5049.5 1802.28  5057.7 1803.29
  5061.3 1801.21  5061.7 1800.71  5066.7 1801.21  5081.3 1802.68  5107.7 1804.35
  5133.0 1803.51  5157.6 1803.81  5178.4 1802.30  5193.0 1803.96  5207.5 1804.15
  5213.8 1803.23  5242.9 1804.70  5249.2 1804.02  5474.6 1804.65  5836.8 1805.94
#Mann=8,-1,0
  3881.4   0.045       0  4206.5    0.07       0  4971.9   0.045       0
  5061.3   0.045       0  5066.7   0.045       0  5081.3    0.16       0
  5133.0    0.07       0  5474.6   0.045       0
Bank Sta=5061.3,5066.7
Exp/Cntr=0.3,0.1

Type RM Length L Ch R = 1,3444,793,793,793
BEGIN DESCRIPTION:
Mapping XS ace56c99
END DESCRIPTION:
XS GIS Cut Line= 4
      1452929.39      6926317.85      1453714.11      6925800.49
      1453953.70      6925439.38      1454071.75      6924717.14
#Sta/Elev= 30
  3624.3 1820.22  3678.9 1819.54  3686.3 1817.98  3694.8 1818.92  3722.4 1818.63
  3737.5 1815.68  3773.6 1813.68  3851.9 1817.67  3918.1 1816.87  3945.2 1813.32
  3996.4 1809.95  4032.5 1810.98  4074.7 1814.73  4125.9 1813.45  4140.9 1811.45
  4205.9 1811.97  4385.6 1805.27  4589.1 1802.21  4790.6 1801.65  4862.8 1798.64
  4866.0 1797.42  4866.4 1796.92  4871.6 1797.42  4883.8 1799.63  4901.3 1799.31
  5009.1 1798.45  5065.5 1801.14  5164.3 1801.09  5242.2 1803.15  5729.4 1805.61
#Mann=7,-1,0
  3624.3   0.045       0  3694.8    0.07       0  4866.0   0.045       0
  4871.6    0.07       0  4901.3   0.045       0  5065.5    0.07       0
  5164.3   0.045       0
Bank Sta=4866,4871.6
Exp/Cntr=0.3,0.1

Type RM Length L Ch R = 1,2651,775,775,775
BEGIN DESCRIPTION:
Mapping XS 71bb0df4
END DESCRIPTION:
XS GIS Cut Line= 3
      1454471.06      6927071.32      1454550.92      6925890.77
      1454759.25      6924956.77
#Sta/Elev= 30
  3806.5 1817.46  3859.9 1815.70  4010.3 1812.65  4086.3 1810.46  4091.3 1810.90
  4130.6 1809.77  4250.8 1808.12  4361.7 1805.34  4411.2 1805.38  4491.4 1804.22
  4571.6 1803.83  4742.0 1801.65  4832.6 1799.74  4892.3 1797.52  4982.5 1796.96
  4985.5 1795.85  4986.0 1795.35  4991.2 1795.35  4991.7 1795.85  5013.1 1796.75
  5035.1 1796.15  5043.8 1797.43  5064.3 1796.77  5146.3 1799.13  5257.5 1800.08
  5330.7 1799.66  5538.7 1799.84  5761.0 1801.90  5814.9 1801.37  5946.7 1802.58
#Mann=4,-1,0
  3806.5    0.07       0  4361.7   0.045       0  4985.5   0.045       0
  4991.7   0.045       0
Bank Sta=4985.5,4991.7
Exp/Cntr=0.3,0.1

Type RM Length L Ch R = 1,1876,39,39,39
BEGIN DESCRIPTION:
Mapping XS 69beaee4
END DESCRIPTION:
XS GIS Cut Line= 3
      1454741.88      6927078.30      1455103.00      6925651.19
      1455241.88      6925095.68
#Sta/Elev= 30
  3518.5 1813.34  3580.7 1813.34  3594.3 1812.03  3641.3 1811.32  3735.4 1810.32
  3766.4 1808.61  3794.2 1809.64  3835.2 1806.95  3958.2 1805.51  3963.4 1804.50
  4034.6 1805.12  4106.8 1802.62  4168.8 1802.91  4309.2 1800.25  4363.2 1799.85
  4375.0 1800.76  4527.2 1797.84  4540.0 1798.72  4742.8 1797.55  4819.5 1797.35
  4855.3 1795.88  4936.1 1796.06  5031.9 1795.66  5032.4 1795.16  5038.4 1795.66
  5086.7 1797.69  5148.5 1797.65  5210.3 1799.31  5416.5 1800.98  5563.2 1800.79
#Mann=8,-1,0
  3518.5    0.07       0  3641.3   0.035       0  4168.8   0.045       0
  4309.2   0.035       0  4742.8    0.07       0  4936.1   0.035       0
  5031.9   0.035       0  5038.4   0.035       0
Bank Sta=5031.9,5038.4
Exp/Cntr=0.3,0.1

Type RM Length L Ch R = 1,1837,0,0,0
BEGIN DESCRIPTION:
Mapping XS c5e604ef
END DESCRIPTION:
XS GIS Cut Line= 3
      1454815.68      6927079.82      1455135.16      6925667.40
      1455267.06      6925113.70
#Sta/Elev= 30
  3551.9 1812.42  3557.8 1812.27  3570.3 1811.14  3584.5 1811.98  3748.1 1810.46
  3810.1 1808.46  3839.6 1808.69  4022.5 1805.26  4035.6 1805.63  4065.7 1804.10
  4119.1 1804.04  4168.9 1802.12  4291.8 1801.97  4333.0 1800.86  4363.7 1801.31
  4383.2 1800.71  4394.5 1801.29  4431.5 1800.16  4769.2 1797.64  4769.3 1797.64
  4977.1 1796.44  4977.6 1795.94  4983.6 1796.44  5174.1 1797.65  5196.7 1798.52
  5266.7 1798.39  5365.2 1800.03  5496.8 1800.46  5503.1 1799.78  5569.2 1800.42
#Mann=6,-1,0
  3551.9    0.07       0  3557.8   0.035       0  4769.2    0.07       0
  4769.3   0.035       0  4977.1   0.035       0  4983.6   0.035       0
Bank Sta=4977.1,4983.6
Exp/Cntr=0.3,0.1

Chan Stop Cuts=-1