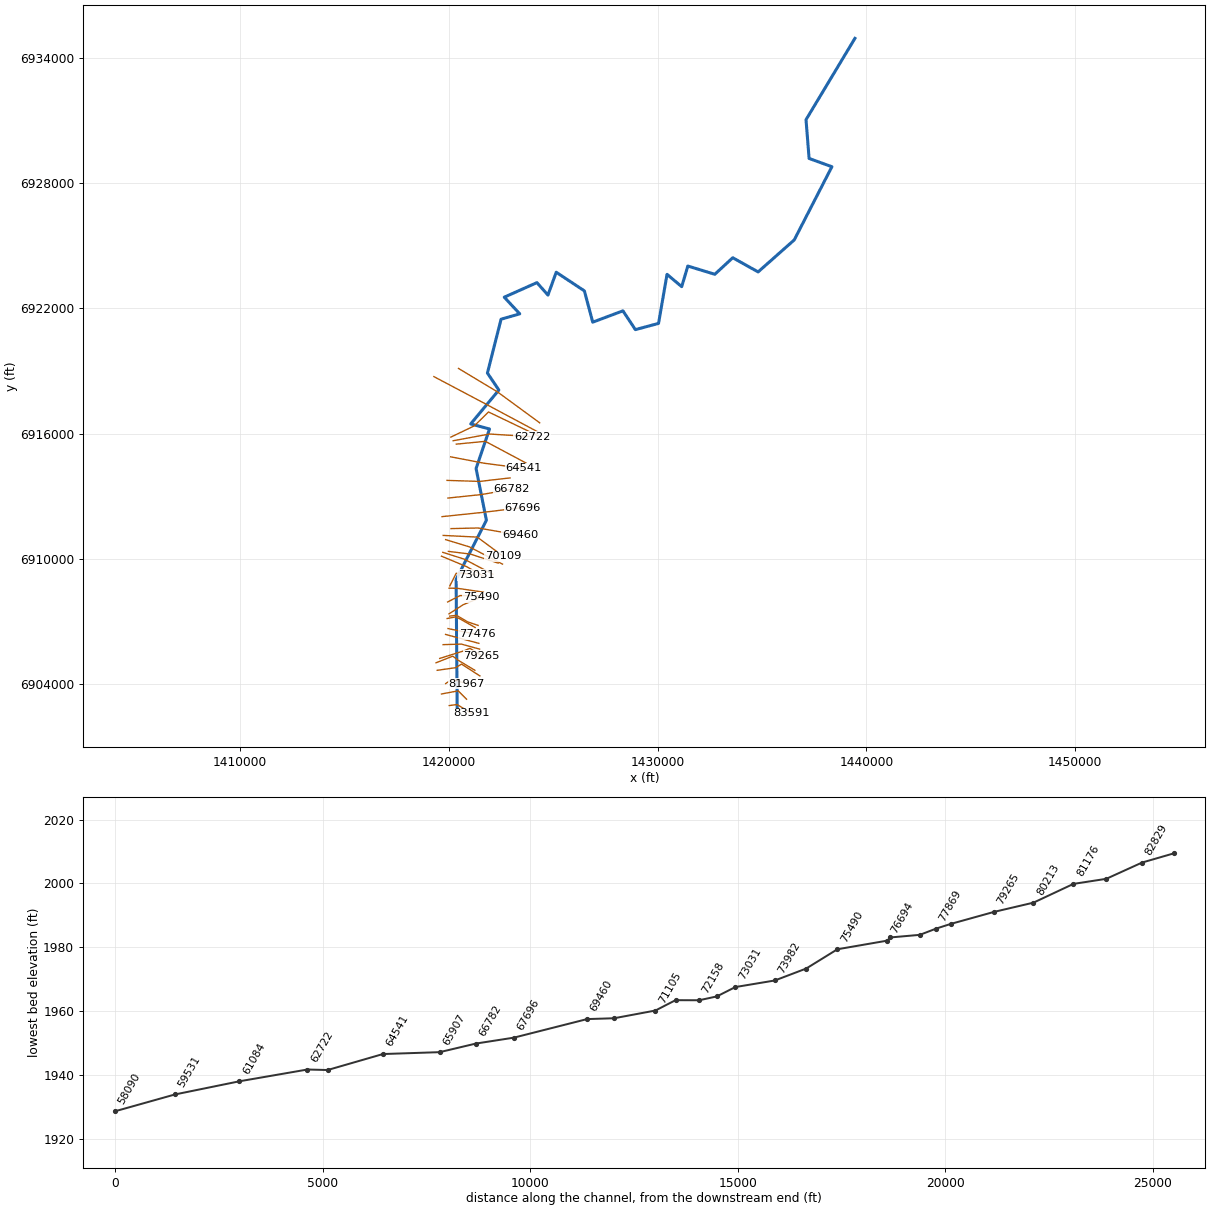
--- East China Creek.prj (project) ---

Proj Title=East China Creek Base Level Engineering
Current Plan=p01
Default Exp/Contr=0.3,0.1
English Units
Geom File=g01
Flow File=f01
Plan File=p01
Y Axis Title=Elevation
X Axis Title(PF)=Main Channel Distance
X Axis Title(XS)=Station
BEGIN DESCRIPTION:
East China Creek
END DESCRIPTION:
DSS Export Rating Curves= 0
DSS Export Rating Curve Sorted= 0
DSS Export Volume Flow Curves= 0
DXF OffsetX= 0
DXF OffsetY= 0
DXF ScaleX= 1
DXF ScaleY= 10

--- East China Creek.p01 (plan) ---

Plan Title=Multiple Run
Short Identifier=Multiple
Geom File=g01
Flow File=f01
Subcritical Flow
K Sum by GR= 0
Std Step Tol= 0.01
Critical Tol= 0.01
Num of Std Step Trials= 20
Max Error Tol= 0.3
Flow Tol Ratio= 0.001
Split Flow NTrial= 30
Split Flow Tol= 0.02
Split Flow Ratio= 0.02
Log Output Level= 0
Friction Slope Method= 1
Unsteady Friction Slope Method= 2
Unsteady Bridges Friction Slope Method= 1
Parabolic Critical Depth
Global Vel Dist=  1 , 1 , 1
Global Log Level= 0
CheckData=True
Encroach Param= -1, 0, 0, 0
BEGIN DESCRIPTION:
Multiple Run
END DESCRIPTION:

--- East China Creek.f01 (steady flow) ---

Flow Title=Multiple
Program Version=4.10
Number of Profiles= 7
Profile Names=10-year,25-year,50-year,1pct_min,100-year,1pct_plu,500-year
River Rch & RM=East China Creek,Reach-1         ,83591
     262     372     464     288     576    1148     896
River Rch & RM=East China Creek,Reach-1         ,82829
     438     639     812     513    1024    2043    1649
River Rch & RM=East China Creek,Reach-1         ,81176
     503     732     929     585    1168    2331    1871
River Rch & RM=East China Creek,Reach-1         ,72586
     946    1413    1826    1168    2331    4651    3852
River Rch & RM=East China Creek,Reach-1         ,64541
     992    1480    1910    1220    2435    4858    4013
River Rch & RM=East China Creek,Reach-1         ,58090
    1031    1535    1979    1262    2519    5026    4137
River Rch & RM=East China Creek,Reach-1         ,49160
    1053    1563    2010    1279    2552    5091    4168
River Rch & RM=East China Creek,Reach-1         ,38564
    1055    1565    2011    1279    2552    5091    4165
River Rch & RM=East China Creek,Reach-1         ,35344
    1175    1745    2246    1429    2852    5690    4661
River Rch & RM=East China Creek,Reach-1         ,21154
    1202    1787    2301    1465    2922    5831    4780
River Rch & RM=East China Creek,Reach-1         ,20434
    1368    2041    2632    1679    3349    6683    5497
River Rch & RM=East China Creek,Reach-1         ,9714
    1446    2150    2769    1763    3518    7019    5752
River Rch & RM=East China Creek,Reach-1         ,7844
    1637    2443    3154    2012    4014    8009    6587
Boundary for River Rch & Prof#=East China Creek,Reach-1         , 1
Up Type= 0
Dn Type= 3
Dn Slope=0.00178
Boundary for River Rch & Prof#=East China Creek,Reach-1         , 2
Up Type= 0
Dn Type= 3
Dn Slope=0.00178
Boundary for River Rch & Prof#=East China Creek,Reach-1         , 3
Up Type= 0
Dn Type= 3
Dn Slope=0.00178
Boundary for River Rch & Prof#=East China Creek,Reach-1         , 4
Up Type= 0
Dn Type= 3
Dn Slope=0.00178
Boundary for River Rch & Prof#=East China Creek,Reach-1         , 5
Up Type= 0
Dn Type= 3
Dn Slope=0.00178
Boundary for River Rch & Prof#=East China Creek,Reach-1         , 6
Up Type= 0
Dn Type= 3
Dn Slope=0.00178
Boundary for River Rch & Prof#=East China Creek,Reach-1         , 7
Up Type= 0
Dn Type= 3
Dn Slope=0.00178
DSS Import GetInterval= 0
DSS Import GetPeak= 0
DSS Import FillOption= 0

--- East China Creek.g01 (geometry) ---

Geom Title=Existing Conditions
Program Version=4.10

River Reach=East China Creek,Reach-1
Reach XY= 30
        1420405.        6902938.      1420355.48      6909027.53
      1421805.52      6911858.04      1421311.88      6914338.03
       1421953.8       6916227.5      1421054.87      6916472.58
      1422403.04      6918093.89      1421854.23      6918908.33
      1422508.52      6921486.54      1423403.15      6921743.75
      1422660.73      6922540.55      1424225.24       6923238.5
      1424753.72      6922641.37      1425149.02      6923735.84
      1426497.52      6922844.06      1426898.32      6921345.45
      1428344.72      6921887.41      1428939.79       6920987.9
      1430049.55      6921285.55      1430456.22      6923634.63
      1431158.66      6923045.48      1431452.15       6924032.2
      1432744.38      6923638.59      1433604.72      6924430.55
      1434818.39      6923751.41      1436547.19      6925281.79
       1438351.9      6928789.65      1437260.08      6929185.69
      1437112.43      6931041.36        1439455.        6934938.

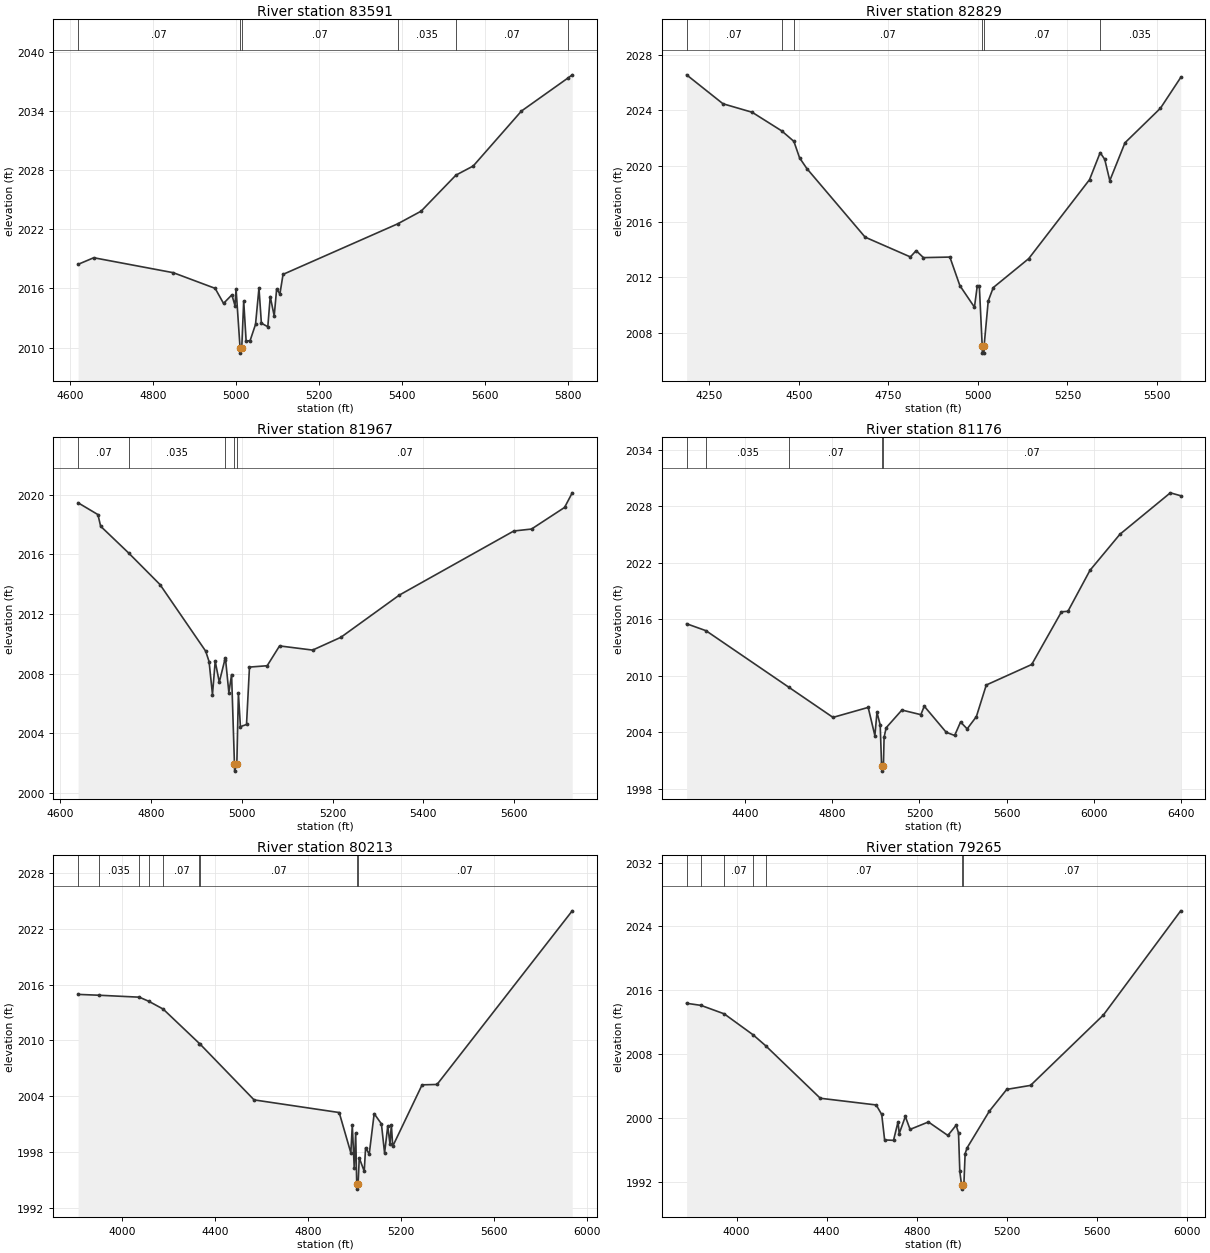
Type RM Length L Ch R = 1 ,83591   ,762,762,762
BEGIN DESCRIPTION:
East China Creek 60.0
END DESCRIPTION:
XS GIS Cut Line= 3
      1420027.57      6902984.59      1420405.08      6903033.03
      1421095.33      6902609.57
#Sta/Elev= 30
  4619.4 2018.45  4657.1 2019.12  4848.7  2017.6  4949.5 2016.01  4969.7 2014.48
  4989.8 2015.35  4997.3 2014.26  4999.9 2015.94  5009.6 2009.93  5009.9 2009.43
  5013.6 2009.93  5018.3 2014.73  5024.2 2010.63  5033.8 2010.71  5046.8 2012.35
  5055.1 2016.05  5060.9 2012.47  5076.4 2012.11  5082.2 2015.18  5091.8 2013.21
  5097.7 2015.96  5105.5 2015.43  5113.1 2017.43  5389.1 2022.56  5445.7 2023.85
  5529.6 2027.51  5571.3 2028.44  5687.4 2034.02  5800.6 2037.41  5809.8  2037.7
#Mann= 6 ,-1 , 0
  4619.4     .07       0  5009.6     .07       0  5013.6     .07       0
  5389.1    .035       0  5529.6     .07       0  5800.6    .035       0
Bank Sta=5009.6,5013.6
XS Rating Curve= 0 ,0
Exp/Cntr=0.3,0.1

Type RM Length L Ch R = 1 ,82829   ,862,862,862
BEGIN DESCRIPTION:
East China Creek 59.0
END DESCRIPTION:
XS GIS Cut Line= 3
      1419655.03      6903538.01        1420455.        6903688.
      1420855.01      6903287.99
#Sta/Elev= 30
  4186.5 2026.55  4288.2 2024.47  4369.6 2023.86  4452.3 2022.52  4486.1 2021.77
  4501.9 2020.59  4522.2 2019.82    4685 2014.89  4811.3 2013.47  4827.4 2013.92
  4847.8 2013.42  4921.6 2013.46  4949.5 2011.41  4990.2 2009.86  4997.9 2011.35
  5003.9 2011.35  5011.9 2007.06  5012.3 2006.56  5016.7 2006.56  5017.1 2007.06
  5028.7 2010.31  5042.8 2011.27  5141.8 2013.35  5311.5 2019.02  5341.2 2020.96
    5354 2020.48  5368.1 2018.95  5410.5 2021.67  5509.5 2024.15  5566.1 2026.36
#Mann= 6 ,-1 , 0
  4186.5     .07       0  4452.3    .035       0  4486.1     .07       0
  5011.9     .07       0  5017.1     .07       0  5341.2    .035       0
Bank Sta=5011.9,5017.1
XS Rating Curve= 0 ,0
Exp/Cntr=0.3,0.1

Type RM Length L Ch R = 1 ,81967   ,791,791,791
BEGIN DESCRIPTION:
East China Creek 58.0
END DESCRIPTION:
XS GIS Cut Line= 3
      1419854.96      6904037.98        1420155.        6904238.
      1420854.99        6904038.
#Sta/Elev= 30
  4639.4 2019.46    4683 2018.67    4689 2017.89  4750.5  2016.1  4819.7 2013.98
  4920.4 2009.51  4927.9 2008.81  4935.4  2006.6  4941.4 2008.83  4950.4 2007.43
  4962.4  2008.9  4963.9 2009.06  4971.5 2006.73  4977.5 2007.94  4983.8 2001.96
  4984.2 2001.46  4989.1 2001.96  4992.5  2006.7    4997 2004.44  5010.4 2004.59
  5016.9 2008.44  5055.9 2008.53  5083.2 2009.86    5156 2009.58  5218.4 2010.44
  5347.1 2013.27  5599.3 2017.57  5638.3  2017.7  5711.1 2019.15    5728 2020.13
#Mann= 5 ,-1 , 0
  4639.4     .07       0  4750.5    .035       0  4962.4     .07       0
  4983.8     .07       0  4989.1     .07       0
Bank Sta=4983.8,4989.1
XS Rating Curve= 0 ,0
Exp/Cntr=0.3,0.1

Type RM Length L Ch R = 1 ,81176   ,963,963,963
BEGIN DESCRIPTION:
Mapping XS dcb70d05
END DESCRIPTION:
XS GIS Cut Line= 4
      1419449.46      6904672.09      1420329.67      6904797.09
      1420616.13      6904968.97      1421494.98      6904402.14
#Sta/Elev= 30
  4130.6 2015.53  4219.7 2014.79  4600.3 2008.78  4802.8 2005.58  4964.4 2006.64
  4995.2 2003.64  5004.8 2006.11  5019.6 2004.78  5025.6 2000.77  5028.6 2000.37
    5029 1999.87  5034.3 2000.37  5037.5 2003.47    5047 2004.48  5119.2 2006.36
  5206.3 2005.87  5221.9 2006.77    5323 2003.99  5361.5 2003.66  5388.6 2005.09
  5418.9 2004.36  5461.2 2005.66  5506.7 2009.02  5715.3  2011.2  5852.1  2016.8
  5881.6 2016.85    5983 2021.21  6120.5 2025.04  6351.9 2029.44  6399.5 2029.13
#Mann= 5 ,-1 , 0
  4130.6     .07       0  4219.7    .035       0  4600.3     .07       0
  5028.6     .07       0  5034.3     .07       0
Bank Sta=5028.6,5034.3
XS Rating Curve= 0 ,0
Exp/Cntr=0.3,0.1

Type RM Length L Ch R = 1 ,80213   ,948,948,948
BEGIN DESCRIPTION:
Mapping XS febaeceb
END DESCRIPTION:
XS GIS Cut Line= 4
      1419392.14      6905031.46      1420194.26      6905349.18
      1420459.88      6905151.26      1421256.03      6904672.53
#Sta/Elev= 30
  3812.8 2014.94  3902.2 2014.85  4075.8 2014.64  4117.1 2014.19  4178.2 2013.36
  4334.2 2009.65  4338.4 2009.55  4568.8 2003.59  4934.5 2002.23  4984.6 1997.89
  4990.8 2000.87  4999.2 1996.26  5005.3 2000.05  5009.9 1994.49  5010.3 1993.99
  5015.7 1994.49  5020.7 1997.35  5042.1 1995.91  5047.9 1998.44  5063.5 1997.75
  5084.8 2002.11  5115.9 2001.01  5129.5 1997.87  5143.1 2000.77  5152.8 1998.84
  5158.6 2000.92  5164.5  1998.6  5290.7 2005.21  5354.9 2005.25  5935.8 2023.93
#Mann= 9 ,-1 , 0
  3812.8     .07       0  3902.2    .035       0  4075.8     .07       0
  4117.1    .035       0  4178.2     .07       0  4334.2    .035       0
  4338.4     .07       0  5009.9     .07       0  5015.7     .07       0
Bank Sta=5009.9,5015.7
XS Rating Curve= 0 ,0
Exp/Cntr=0.3,0.1

Type RM Length L Ch R = 1 ,79265   ,1043,1043,1043
BEGIN DESCRIPTION:
Mapping XS 9b309074
END DESCRIPTION:
XS GIS Cut Line= 4
      1419569.23      6905239.79      1420709.88      6905599.18
      1421017.17      6905724.18      1421579.69        6905370.
#Sta/Elev= 30
  3778.5 2014.37  3842.4 2014.11  3945.3 2013.05  4073.8 2010.42  4128.8 2009.07
  4371.7 2002.48  4619.6 2001.64  4644.3 2000.45  4657.2 1997.26  4696.7 1997.21
  4716.7 1999.53  4721.9 1998.05  4749.1  2000.2  4770.1 1998.58  4851.4 1999.51
  4937.9 1997.82  4974.4  1999.1    4985 1998.14  4990.8 1993.31  4998.6  1991.6
  4999.1  1991.1  5004.5  1991.6    5009 1991.81  5014.4 1995.55  5023.1 1996.27
  5121.5 2000.85  5199.1 2003.59  5304.6 2004.09    5628 2012.91  5970.9 2025.95
#Mann= 7 ,-1 , 0
  3778.5     .07       0  3842.4    .035       0  3945.3     .07       0
  4073.8    .035       0  4128.8     .07       0  4998.6     .07       0
  5004.5     .07       0
Bank Sta=4998.6,5004.5
XS Rating Curve= 0 ,0
Exp/Cntr=0.3,0.1

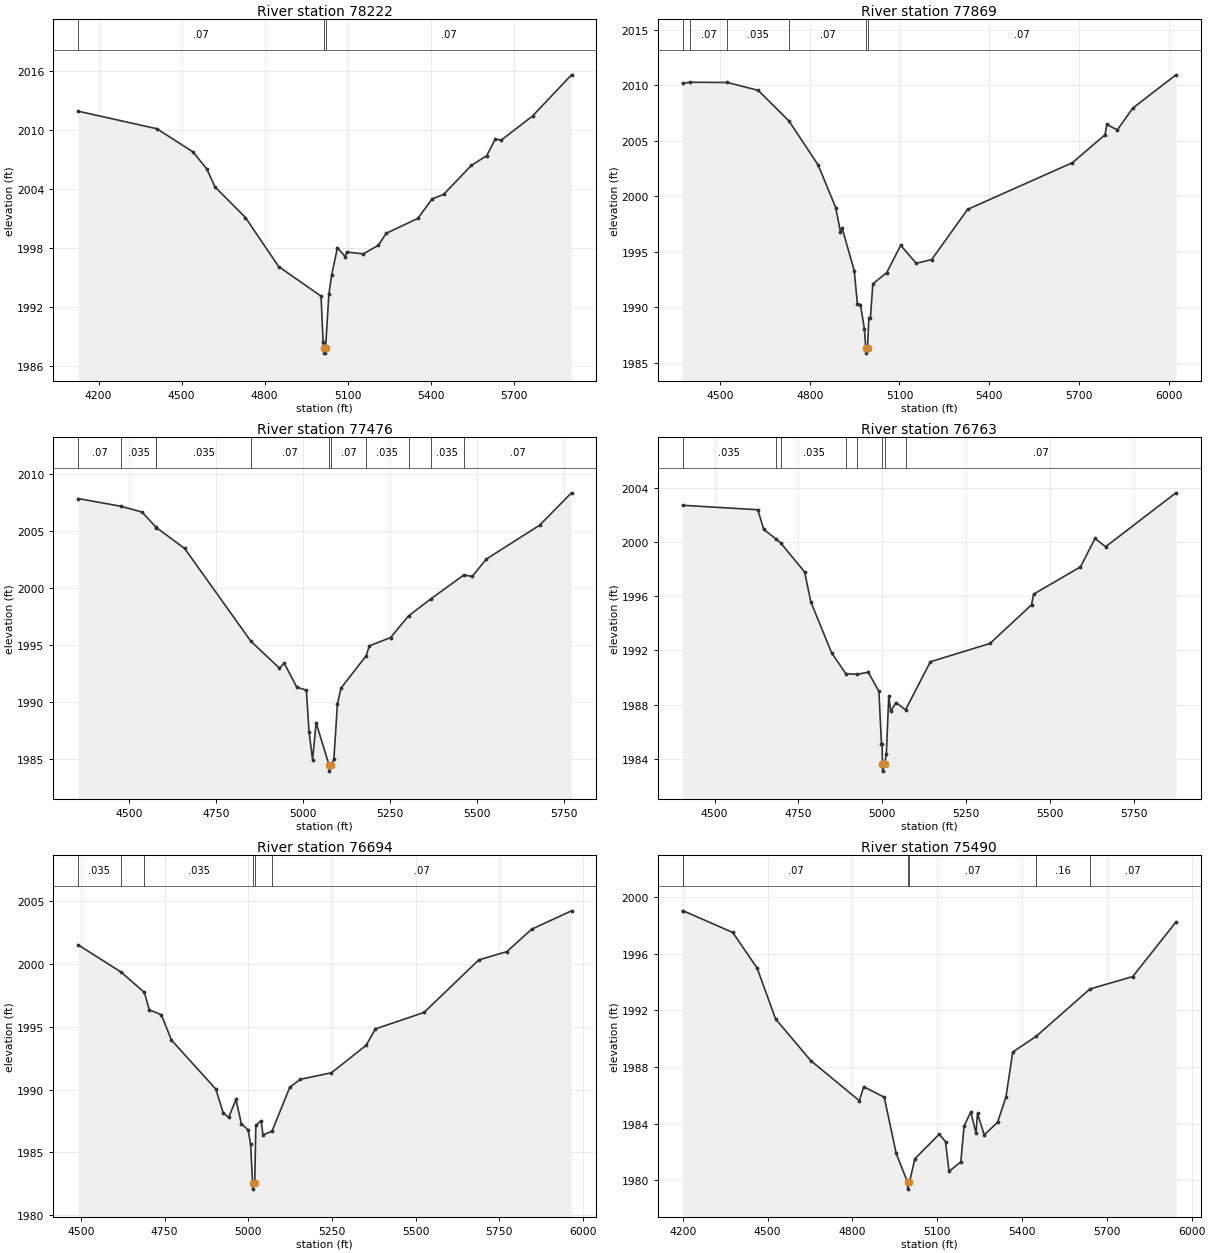
Type RM Length L Ch R = 1 ,78222   ,353,353,353
BEGIN DESCRIPTION:
Mapping XS 3b0065a9
END DESCRIPTION:
XS GIS Cut Line= 3
      1419730.69      6905901.26      1420605.72       6905927.3
       1421480.4       6905687.8
#Sta/Elev= 30
    4126 2011.88  4410.4  2010.1  4540.5 2007.76  4590.5 2006.04  4620.5  2004.2
  4730.6 2001.09  4850.6 1996.11  5003.6 1993.11    5011 1988.48    5014 1987.83
  5014.5 1987.33  5019.4 1987.33  5019.9 1987.83  5031.8  1993.3  5042.1 1995.29
  5062.9 1998.04  5091.1 1997.11  5096.3 1997.59  5156.2  1997.4  5210.1 1998.26
  5239.1 1999.49  5353.2    2001    5405 2002.98  5446.5 2003.44  5546.4 2006.38
    5602 2007.36  5633.1 2009.07  5653.9 2008.93  5767.9  2011.4  5908.3 2015.57
#Mann= 3 ,-1 , 0
    4126     .07       0    5014     .07       0  5019.9     .07       0
Bank Sta=5014,5019.9
XS Rating Curve= 0 ,0
Exp/Cntr=0.3,0.1

Type RM Length L Ch R = 1 ,77869   ,393,393,393
BEGIN DESCRIPTION:
East China Creek 52.0
END DESCRIPTION:
XS GIS Cut Line= 3
      1419850.52      6906390.84       1420454.5      6906227.79
      1421444.29      6905963.75
#Sta/Elev= 30
  4374.4 2010.18  4400.8 2010.28    4524 2010.26  4627.6 2009.55  4730.7 2006.78
  4828.1 2002.82  4886.6 1998.98  4902.7 1996.79  4907.9 1997.16  4948.7 1993.29
  4959.1 1990.33  4969.4 1990.23  4982.5 1988.07  4987.2 1986.36  4987.7 1985.86
  4993.2 1986.36  4997.7 1989.05  5002.8 1989.05  5010.9 1992.11  5057.4 1993.12
    5104 1995.58  5155.8 1993.96  5207.5 1994.29  5327.8 1998.82  5678.3 2003.03
  5787.1 2005.54  5793.4 2006.48  5828.3 2005.98  5880.2 2007.95  6024.4 2010.95
#Mann= 6 ,-1 , 0
  4374.4    .035       0  4400.8     .07       0    4524    .035       0
  4730.7     .07       0  4987.2     .07       0  4993.2     .07       0
Bank Sta=4987.2,4993.2
XS Rating Curve= 0 ,0
Exp/Cntr=0.3,0.1

Type RM Length L Ch R = 1 ,77476   ,713,713,713
BEGIN DESCRIPTION:
East China Creek 51.0
END DESCRIPTION:
XS GIS Cut Line= 3
      1419965.09      6906672.09        1420605.        6906538.
      1421355.03      6906387.99
#Sta/Elev= 30
  4353.9 2007.86    4477 2007.18  4537.7 2006.67  4578.6 2005.32  4578.8 2005.31
  4660.3 2003.47  4850.9 1995.31  4932.8 1992.95  4946.4 1993.39  4982.8 1991.28
  5010.3 1991.01  5017.9 1987.38  5028.1 1984.92  5038.3 1988.14  5075.9  1984.4
  5076.4  1983.9  5082.3  1984.4  5089.3 1984.95  5099.5 1989.78  5109.7 1991.19
  5182.2 1994.04  5191.3 1994.91  5252.5 1995.64  5303.9 1997.54  5368.2 1999.04
  5463.1 2001.14    5487 2001.01  5527.8 2002.54  5680.8 2005.51  5772.6 2008.36
#Mann= 11 ,-1 , 0
  4353.9     .07       0    4477    .035       0  4578.6     .07       0
  4578.8    .035       0  4850.9     .07       0  5075.9     .07       0
  5082.3     .07       0  5182.2    .035       0  5303.9     .07       0
  5368.2    .035       0  5463.1     .07       0
Bank Sta=5075.9,5082.3
XS Rating Curve= 0 ,0
Exp/Cntr=0.3,0.1

Type RM Length L Ch R = 1 ,76763   ,69,69,69
BEGIN DESCRIPTION:
East China Creek 50.0
END DESCRIPTION:
XS GIS Cut Line= 4
      1419926.67      6907152.58       1420306.9       6907222.9
      1420504.12      6907153.36      1421267.77      6906722.94
#Sta/Elev= 30
  4404.2 2002.72  4628.9 2002.39  4646.6 2000.94  4681.7 2000.26  4698.3 1999.91
  4768.6 1997.79  4787.4 1995.56    4849 1991.83  4891.5 1990.28  4925.5 1990.23
  4958.5 1990.39  4990.3 1988.97  4997.8 1985.11    5000 1985.11  5000.5 1983.58
    5001 1983.08    5007 1983.58  5012.5 1984.38  5019.7 1988.65  5025.4 1987.49
  5041.3 1988.15  5069.7 1987.61  5143.9 1991.16  5321.6 1992.51  5445.9 1995.37
  5451.6 1996.15  5591.8 1998.17  5635.1 2000.27  5666.8 1999.66  5876.6 2003.64
#Mann= 8 ,-1 , 0
  4404.2    .035       0  4681.7     .07       0  4698.3    .035       0
  4891.5     .07       0  4925.5    .035       0  5000.5    .035       0
    5007    .035       0  5069.7     .07       0
Bank Sta=5000.5,5007
XS Rating Curve= 0 ,0
Exp/Cntr=0.3,0.1

Type RM Length L Ch R = 1 ,76694   ,1204,1204,1204
BEGIN DESCRIPTION:
East China Creek 49.0
END DESCRIPTION:
XS GIS Cut Line= 5
      1420048.44      6907265.85      1420361.59      6907306.23
      1420531.29      6907214.82      1420913.67      6906988.53
       1421407.8      6906823.13
#Sta/Elev= 30
  4491.5 2001.49  4618.7 1999.35  4689.3 1997.72  4704.3 1996.33  4740.1 1995.94
  4770.3 1993.93    4903 1990.03  4924.9 1988.15  4941.2 1987.78  4963.1 1989.21
  4979.3 1987.27  4999.3  1986.8  5006.8 1985.66  5012.7 1982.59  5013.2 1982.09
  5019.2 1982.59  5022.5 1987.16  5038.1 1987.53  5043.9  1986.4  5070.8 1986.69
  5123.9 1990.18  5155.1 1990.81  5248.3 1991.33    5352 1993.51  5379.3 1994.81
  5524.8 1996.12  5688.3 2000.29  5772.1 2000.95  5846.4 2002.73  5965.4 2004.19
#Mann= 6 ,-1 , 0
  4491.5    .035       0  4618.7     .07       0  4689.3    .035       0
  5012.7    .035       0  5019.2    .035       0  5070.8     .07       0
Bank Sta=5012.7,5019.2
XS Rating Curve= 0 ,0
Exp/Cntr=0.3,0.1

Type RM Length L Ch R = 1 ,75490   ,751,751,751
BEGIN DESCRIPTION:
Mapping XS 5a1e1126
END DESCRIPTION:
XS GIS Cut Line= 3
      1420012.86      6907375.15      1420694.25       6907813.5
       1421557.1      6908173.38
#Sta/Elev= 30
  4199.4 1999.03  4202.1 1999.03  4377.3  1997.5  4463.5 1994.98  4528.5  1991.4
  4652.7 1988.46    4825 1985.62  4840.2 1986.61  4912.9 1985.87  4955.1  1981.9
  4995.2 1979.88  4995.7 1979.38  5002.1 1979.88  5021.3 1981.53  5107.4 1983.26
  5129.6 1982.73    5142 1980.63  5183.8 1981.31  5195.1 1983.82  5218.9 1984.84
  5237.3 1983.33  5242.7 1984.72  5266.6 1983.21  5313.8  1984.1  5343.5  1985.9
  5367.3 1989.06  5449.6 1990.16  5640.4 1993.51  5791.8 1994.39  5944.5 1998.24
#Mann= 6 ,-1 , 0
  4199.4    .035       0  4202.1     .07       0  4995.2     .07       0
  5002.1     .07       0  5449.6     .16       0  5640.4     .07       0
Bank Sta=4995.2,5002.1
XS Rating Curve= 0 ,0
Exp/Cntr=0.3,0.1

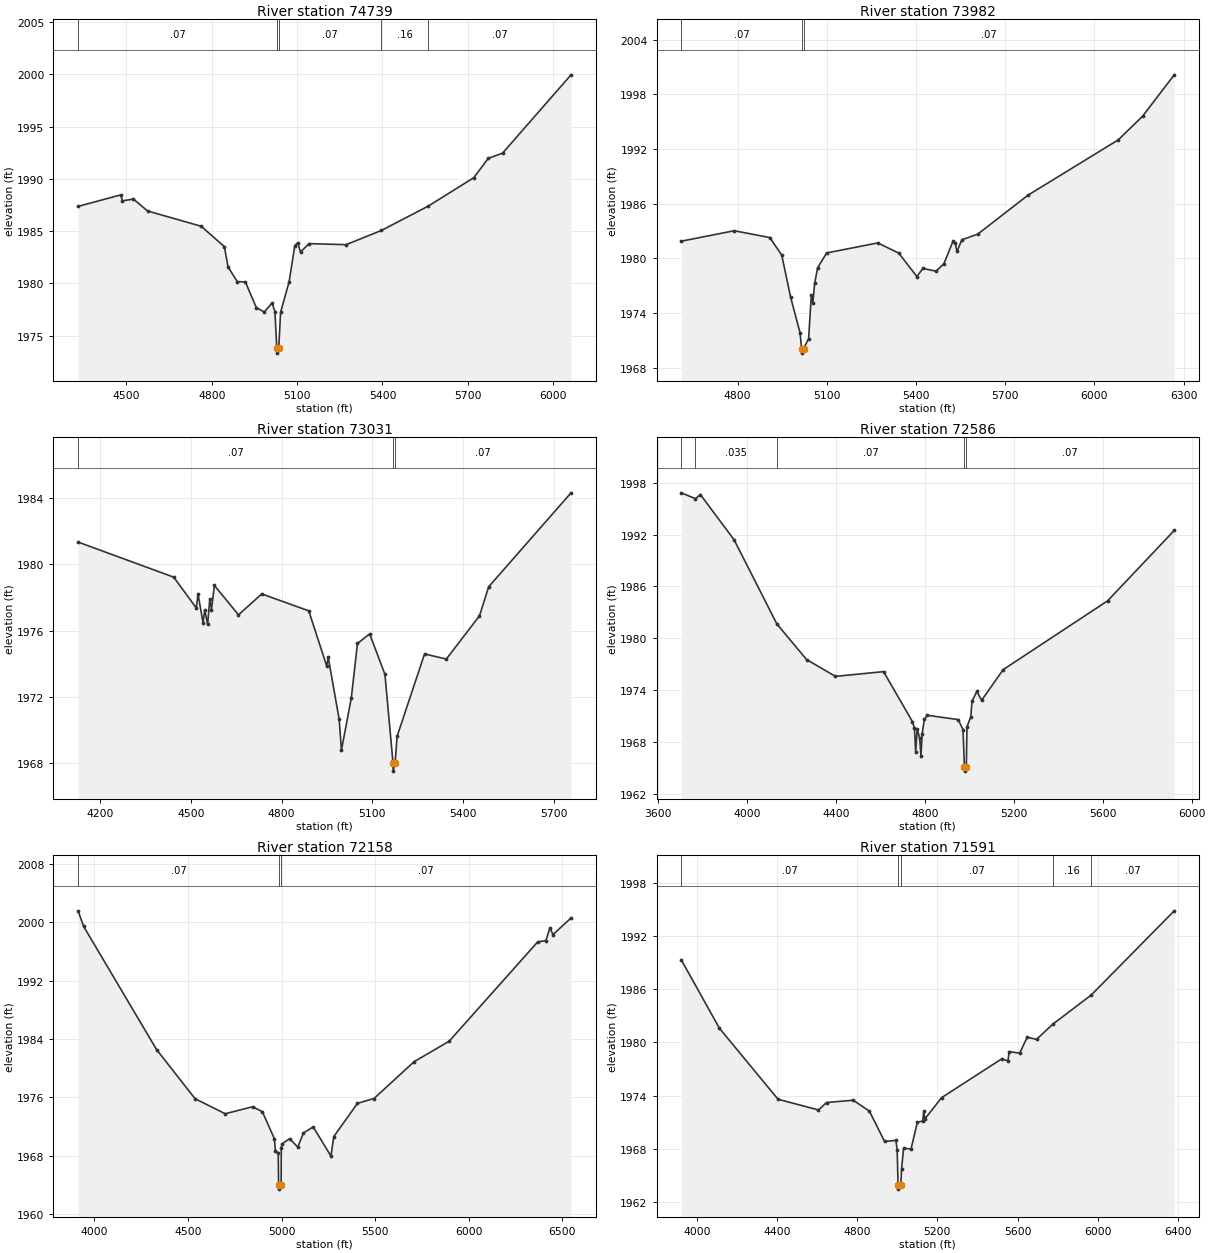
Type RM Length L Ch R = 1 ,74739   ,757,757,757
BEGIN DESCRIPTION:
Mapping XS 170df66a
END DESCRIPTION:
XS GIS Cut Line= 3
      1419947.69      6907943.69      1420546.69      6908251.87
      1421605.68      6908238.85
#Sta/Elev= 30
  4330.1 1987.37  4480.2 1988.47  4485.9  1987.9  4524.6 1988.07  4574.6 1986.93
  4762.9 1985.47  4844.4 1983.52  4857.2 1981.59  4889.4 1980.18  4918.1 1980.15
  4956.8 1977.69  4984.6 1977.27    5012 1978.13    5022 1977.32  5028.6 1973.84
  5029.1 1973.34  5035.5 1973.84    5042 1977.24    5072 1980.18    5092 1983.63
    5102 1983.89    5112 1983.01  5142.1 1983.81  5272.1 1983.71  5396.4 1985.07
  5561.8 1987.41  5721.2 1990.12  5772.1 1991.97  5822.1 1992.46  6062.8 1999.95
#Mann= 5 ,-1 , 0
  4330.1     .07       0  5028.6     .07       0  5035.5     .07       0
  5396.4     .16       0  5561.8     .07       0
Bank Sta=5028.6,5035.5
XS Rating Curve= 0 ,0
Exp/Cntr=0.3,0.1

Type RM Length L Ch R = 1 ,73982   ,951,951,951
BEGIN DESCRIPTION:
Mapping XS 75916205
END DESCRIPTION:
XS GIS Cut Line= 3
      1420017.18      6908603.43      1420416.48      6908599.09
       1421661.1      6908416.95
#Sta/Elev= 30
  4610.9 1981.88  4788.7 1983.03  4908.7 1982.28  4948.7 1980.35  4978.7  1975.7
  5010.2 1971.83  5015.4 1970.09  5015.9 1969.59  5022.3 1970.09    5039 1971.17
  5048.2 1975.96  5053.3  1975.1  5059.3 1977.25  5069.4 1978.97  5099.7 1980.59
  5271.5 1981.69  5342.2 1980.57  5402.9    1978  5423.1 1978.89  5467.6 1978.59
  5493.8 1979.41  5524.2 1981.86  5532.5 1981.68  5537.5 1980.75  5554.5 1982.04
  5607.4 1982.65  5776.8 1986.94    6080 1993.01  6161.6  1995.6  6268.1 2000.15
#Mann= 3 ,-1 , 0
  4610.9     .07       0  5015.4     .07       0  5022.3     .07       0
Bank Sta=5015.4,5022.3
XS Rating Curve= 0 ,0
Exp/Cntr=0.3,0.1

Type RM Length L Ch R = 1 ,73031   ,445,445,445
BEGIN DESCRIPTION:
East China Creek 44.0
END DESCRIPTION:
XS GIS Cut Line= 4
      1420053.78      6908715.16      1420355.87      6909316.73
        1420555.        6909338.      1421305.04        6909238.
#Sta/Elev= 30
  4126.9 1981.35  4443.4 1979.23  4517.9 1977.37  4523.5 1978.22  4540.2 1976.48
  4545.8 1977.26  4555.3 1976.38  4562.5 1977.92  4568.1 1977.28  4577.7 1978.73
  4657.4 1976.96  4734.3 1978.22  4889.7  1977.2  4949.1 1973.87  4954.2 1974.39
  4990.3 1970.65  4997.8 1968.79  5030.6 1971.97  5050.8 1975.23  5091.1 1975.81
  5141.6 1973.37  5168.3 1968.03  5168.8 1967.53  5175.3 1968.03  5181.9 1969.63
  5272.7  1974.6  5344.6 1974.29  5454.3  1976.9  5484.6 1978.65    5757 1984.32
#Mann= 3 ,-1 , 0
  4126.9     .07       0  5168.3     .07       0  5175.3     .07       0
Bank Sta=5168.3,5175.3
XS Rating Curve= 0 ,0
Exp/Cntr=0.3,0.1

Type RM Length L Ch R = 1 ,72586   ,428,428,428
BEGIN DESCRIPTION:
East China Creek 43.0
END DESCRIPTION:
XS GIS Cut Line= 3
      1419655.04      6910137.98        1420855.        6909638.
      1421654.97      6909188.02
#Sta/Elev= 30
  3703.8 1996.85  3767.8 1996.17  3789.9 1996.65  3942.1 1991.38  4133.8 1981.66
  4267.6 1977.53  4397.6 1975.58  4613.8 1976.13  4743.8 1970.34    4753 1969.58
  4758.4 1966.79  4765.4 1969.48  4776.3 1968.44  4782.2  1966.4  4787.6 1968.93
  4797.9 1970.66  4811.5 1971.07  4949.6 1970.57  4971.3 1969.42  4977.9  1965.1
  4978.4  1964.6  4986.3  1965.1  4989.1 1969.71  5006.6 1970.93  5011.7 1972.68
  5033.4 1973.83  5055.1 1972.81    5152 1976.36  5621.7 1984.33  5921.6 1992.49
#Mann= 5 ,-1 , 0
  3703.8     .07       0  3767.8    .035       0  4133.8     .07       0
  4977.9     .07       0  4986.3     .07       0
Bank Sta=4977.9,4986.3
XS Rating Curve= 0 ,0
Exp/Cntr=0.3,0.1

Type RM Length L Ch R = 1 ,72158   ,567,567,567
BEGIN DESCRIPTION:
Mapping XS 4f4a57e3
END DESCRIPTION:
XS GIS Cut Line= 3
       1419715.1      6910323.13      1420746.34      6909995.01
       1422120.7      6909271.39
#Sta/Elev= 30
  3912.2  2001.6    3942 1999.46  4331.9 1982.55  4537.9  1975.8    4699 1973.74
  4846.1 1974.71  4897.7 1974.01  4961.5 1970.32  4967.4 1968.68  4982.5 1968.35
  4984.3 1963.89  4984.8 1963.39  4997.8 1963.89  4998.6  1969.1  5004.3 1969.63
  5042.7 1970.32  5086.7 1969.17  5117.2  1971.1  5169.2 1971.93  5264.1 1967.93
  5279.4 1970.61  5405.9 1975.17  5494.1 1975.83  5708.8 1980.89  5895.8 1983.69
  6369.2 1997.33  6413.3 1997.51  6435.3 1999.29  6450.7 1998.33  6547.6 2000.62
#Mann= 3 ,-1 , 0
  3912.2     .07       0  4984.3     .07       0  4997.8     .07       0
Bank Sta=4984.3,4997.8
XS Rating Curve= 0 ,0
Exp/Cntr=0.3,0.1

Type RM Length L Ch R = 1 ,71591   ,486,486,486
BEGIN DESCRIPTION:
Mapping XS 97222346
END DESCRIPTION:
XS GIS Cut Line= 3
      1419985.95      6910368.27      1421048.42      6910236.33
      1422367.91      6909805.76
#Sta/Elev= 30
  3922.8 1989.34  4113.3  1981.6  4405.5 1973.58  4607.1 1972.37  4647.4 1973.21
  4780.2 1973.47  4861.1 1972.24  4936.9 1968.81  4993.4 1968.93  4999.6 1967.83
  5004.1 1963.92  5004.6 1963.42  5017.7 1963.92  5021.4 1965.66  5031.5 1968.04
  5068.7 1967.96  5100.6    1971  5126.6  1971.1  5132.5 1972.21  5137.7 1971.36
  5221.3 1973.76  5520.5 1978.14  5552.4 1977.92  5557.9 1978.97  5610.5 1978.79
  5648.1 1980.59  5694.6 1980.35  5777.1 1982.09  5967.9 1985.37  6381.4 1994.88
#Mann= 5 ,-1 , 0
  3922.8     .07       0  5004.1     .07       0  5017.7     .07       0
  5777.1     .16       0  5967.9     .07       0
Bank Sta=5004.1,5017.7
XS Rating Curve= 0 ,0
Exp/Cntr=0.3,0.1

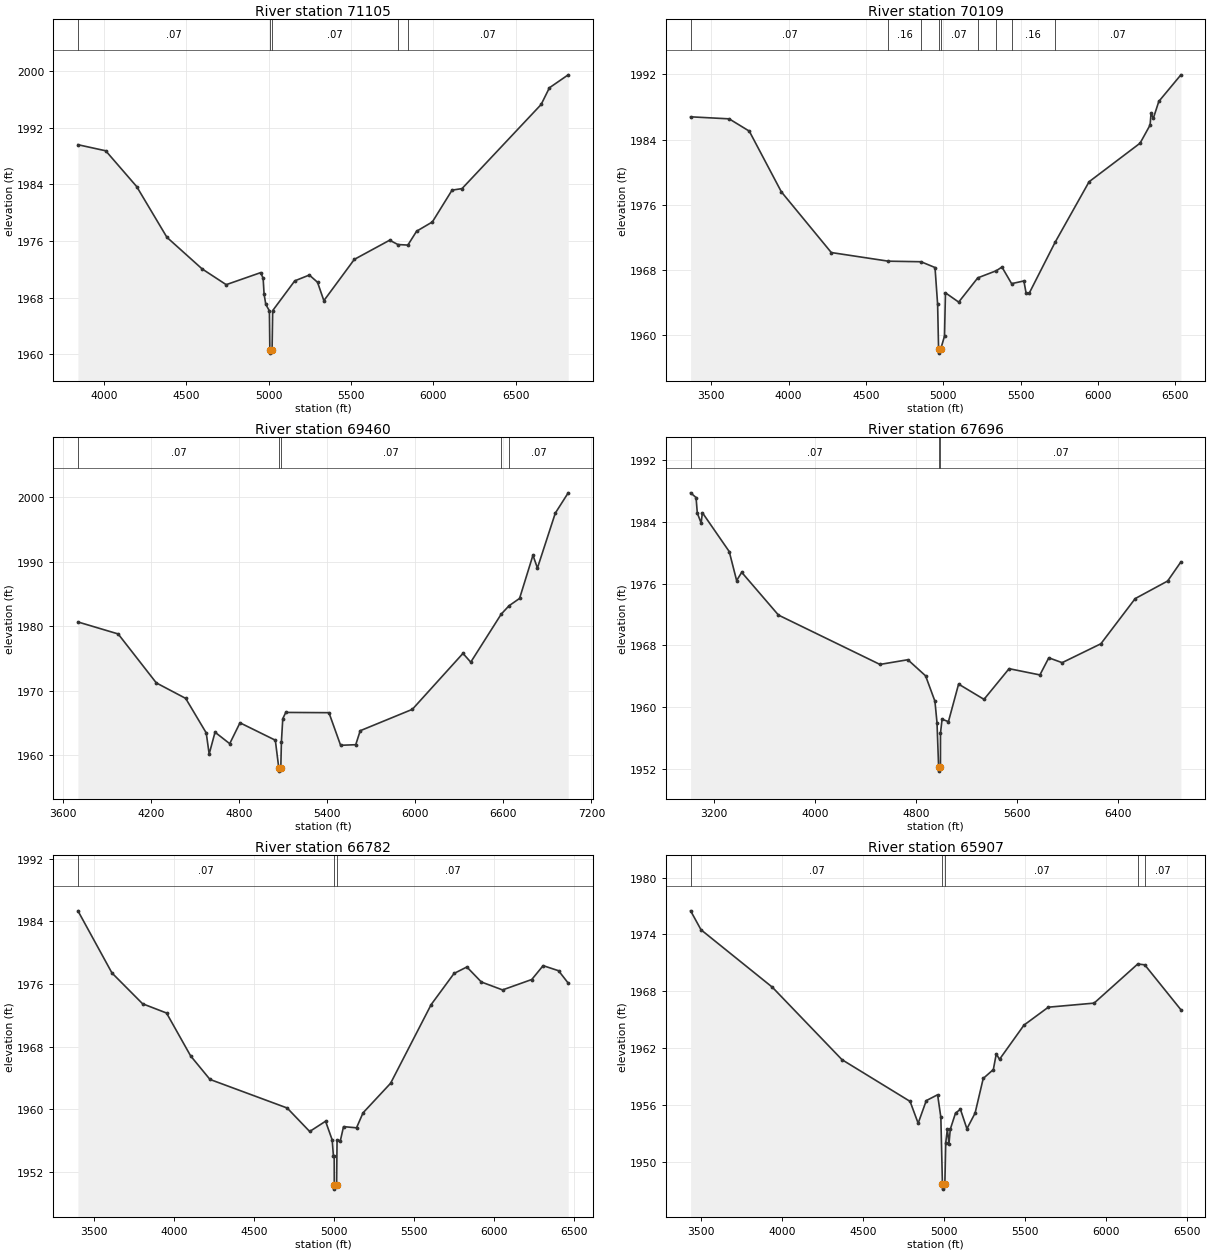
Type RM Length L Ch R = 1 ,71105   ,996,996,996
BEGIN DESCRIPTION:
Mapping XS edc928b6
END DESCRIPTION:
XS GIS Cut Line= 3
      1419853.95      6910930.78      1420992.87      6910583.55
       1422576.2      6909757.16
#Sta/Elev= 30
  3841.5 1989.61  4010.2 1988.75  4198.1  1983.7  4381.8 1976.53  4595.3 1972.07
  4741.7 1969.84  4950.8 1971.54    4966 1970.75  4971.7 1968.51  4982.1 1967.06
    5004 1966.14  5006.7 1960.67  5007.2 1960.17  5020.3 1960.67    5024 1966.18
    5158 1970.38  5246.4  1971.2  5296.2 1970.18  5334.7 1967.58  5519.6 1973.41
    5734 1976.12  5784.1 1975.51  5844.6 1975.43  5897.7 1977.39  5993.4  1978.7
  6112.9 1983.19  6173.5 1983.41  6653.8 1995.29    6704 1997.65  6818.2 1999.48
#Mann= 5 ,-1 , 0
  3841.5     .07       0  5006.7     .07       0  5020.3     .07       0
  5784.1     .16       0  5844.6     .07       0
Bank Sta=5006.7,5020.3
XS Rating Curve= 0 ,0
Exp/Cntr=0.3,0.1

Type RM Length L Ch R = 1 ,70109   ,649,649,649
BEGIN DESCRIPTION:
East China Creek 39.0
END DESCRIPTION:
XS GIS Cut Line= 3
      1419735.97      6911132.16      1421368.37      6911051.29
      1422604.98      6910138.01
#Sta/Elev= 30
  3365.6 1986.79  3614.9 1986.54  3745.1 1985.03  3952.6 1977.57  4275.7 1970.11
  4644.4 1969.05  4856.2 1968.98  4946.6 1968.27  4963.5 1963.74  4969.7 1958.25
  4970.2 1957.75  4983.5 1958.25    5008 1959.84  5014.2 1965.16  5099.8 1964.02
  5223.3    1967  5343.6 1967.88  5379.6 1968.33  5442.1 1966.29  5521.5 1966.62
  5536.2 1965.09    5557 1965.15  5723.2 1971.36  5943.3 1978.81  6273.2 1983.55
    6338 1985.78  6344.2 1987.23  6358.8  1986.6  6394.3 1988.68  6537.3 1991.95
#Mann= 9 ,-1 , 0
  3365.6     .07       0  4644.4     .16       0  4856.2     .07       0
  4969.7     .07       0  4983.5     .07       0  5223.3     .16       0
  5343.6     .07       0  5442.1     .16       0  5723.2     .07       0
Bank Sta=4969.7,4983.5
XS Rating Curve= 0 ,0
Exp/Cntr=0.3,0.1

Type RM Length L Ch R = 1 ,69460   ,1764,1764,1764
BEGIN DESCRIPTION:
East China Creek 38.0
END DESCRIPTION:
XS GIS Cut Line= 3
      1420110.94      6911458.55        1421405.        6911488.
       1423421.7       6911139.4
#Sta/Elev= 30
  3700.4 1980.64  3974.5 1978.78  4234.6 1971.18  4434.6 1968.78  4574.7 1963.42
  4594.7 1960.14  4634.7 1963.53  4734.7 1961.75  4804.7 1964.99  5045.5 1962.29
  5069.1 1957.99  5069.6 1957.49  5082.9 1957.99    5087 1962.03  5096.3 1965.63
  5116.6  1966.6  5410.9 1966.56  5490.4  1961.5  5593.5 1961.59    5624 1963.76
  5979.2 1967.08  6324.2 1975.76  6377.3  1974.4    6585 1981.86  6638.4 1983.16
  6709.9 1984.29  6801.2    1991  6831.6    1989  6953.4 1997.53  7041.4 2000.68
#Mann= 5 ,-1 , 0
  3700.4     .07       0  5069.1     .07       0  5082.9     .07       0
    6585    .035       0  6638.4     .07       0
Bank Sta=5069.1,5082.9
XS Rating Curve= 0 ,0
Exp/Cntr=0.3,0.1

Type RM Length L Ch R = 1 ,67696   ,914,914,914
BEGIN DESCRIPTION:
East China Creek 37.0
END DESCRIPTION:
XS GIS Cut Line= 3
      1419682.15      6912031.47        1421655.        6912238.
      1423544.93      6912465.49
#Sta/Elev= 30
  3012.3 1987.77  3055.4 1987.16  3065.4 1985.14  3095.6 1983.86  3105.7 1985.19
  3318.5 1980.15  3377.1 1976.39  3417.4 1977.46  3708.9 1971.91  4513.3 1965.51
  4734.5 1966.12  4875.3 1964.03  4949.3 1960.74  4965.8 1957.95  4978.7 1952.17
  4979.2 1951.67    4993 1952.17  4993.4  1956.6    5006  1958.4  5056.4 1958.09
  5136.9 1962.96  5338.4 1960.98  5537.3 1964.96  5781.6 1964.15  5852.1 1966.37
    5958 1965.74    6265 1968.19    6537 1974.05  6794.4 1976.33  6899.5 1978.81
#Mann= 3 ,-1 , 0
  3012.3     .07       0  4978.7     .07       0    4993     .07       0
Bank Sta=4978.7,4993
XS Rating Curve= 0 ,0
Exp/Cntr=0.3,0.1

Type RM Length L Ch R = 1 ,66782   ,875,875,875
BEGIN DESCRIPTION:
East China Creek 35.0
END DESCRIPTION:
XS GIS Cut Line= 3
      1419964.24      6912921.23        1421555.        6913088.
      1422999.58      6913333.07
#Sta/Elev= 30
  3400.9 1985.36  3613.8 1977.42  3805.2 1973.49  3954.7 1972.31  4105.5 1966.83
  4226.2 1963.83  4708.8 1960.18  4849.6 1957.18  4948.8 1958.49  4990.3  1956.1
  4997.9 1954.06  5002.9 1954.06  5003.3 1950.32  5003.8 1949.82  5017.8 1950.32
  5020.7 1956.12    5041 1955.98  5061.2  1957.8  5142.4 1957.65    5183 1959.56
  5355.4 1963.34    5609 1973.39  5751.9 1977.36  5832.1 1978.19  5922.7 1976.27
  6055.2 1975.26  6237.8 1976.59  6308.8 1978.36  6405.3 1977.71  6465.6 1976.13
#Mann= 3 ,-1 , 0
  3400.9     .07       0  5003.3     .07       0  5017.8     .07       0
Bank Sta=5003.3,5017.8
XS Rating Curve= 0 ,0
Exp/Cntr=0.3,0.1

Type RM Length L Ch R = 1 ,65907   ,1366,1366,1366
BEGIN DESCRIPTION:
East China Creek 34.0
END DESCRIPTION:
XS GIS Cut Line= 3
      1419920.79      6913767.58      1421484.51       6913718.2
      1422937.34      6913886.94
#Sta/Elev= 30
  3435.5 1976.49  3499.7 1974.49    3940 1968.43  4370.2 1960.78  4790.4 1956.38
  4840.4 1954.07  4890.4 1956.46  4960.5 1957.08  4980.5 1954.69  4990.3 1947.62
  4990.8 1947.12  5005.2 1947.62  5010.6 1952.02  5020.6 1953.43  5030.7 1951.92
  5038.7 1953.44    5071 1955.14  5101.2 1955.55  5141.4 1953.49  5191.8 1955.14
  5242.1  1958.8  5304.6 1959.74  5322.6 1961.39  5342.8 1960.82  5493.8 1964.43
    5644 1966.32  5926.7 1966.75  6196.3 1970.88  6239.4 1970.79  6462.6 1966.05
#Mann= 5 ,-1 , 0
  3435.5     .07       0  4990.3     .07       0  5005.2     .07       0
  6196.3    .035       0  6239.4     .07       0
Bank Sta=4990.3,5005.2
XS Rating Curve= 0 ,0
Exp/Cntr=0.3,0.1

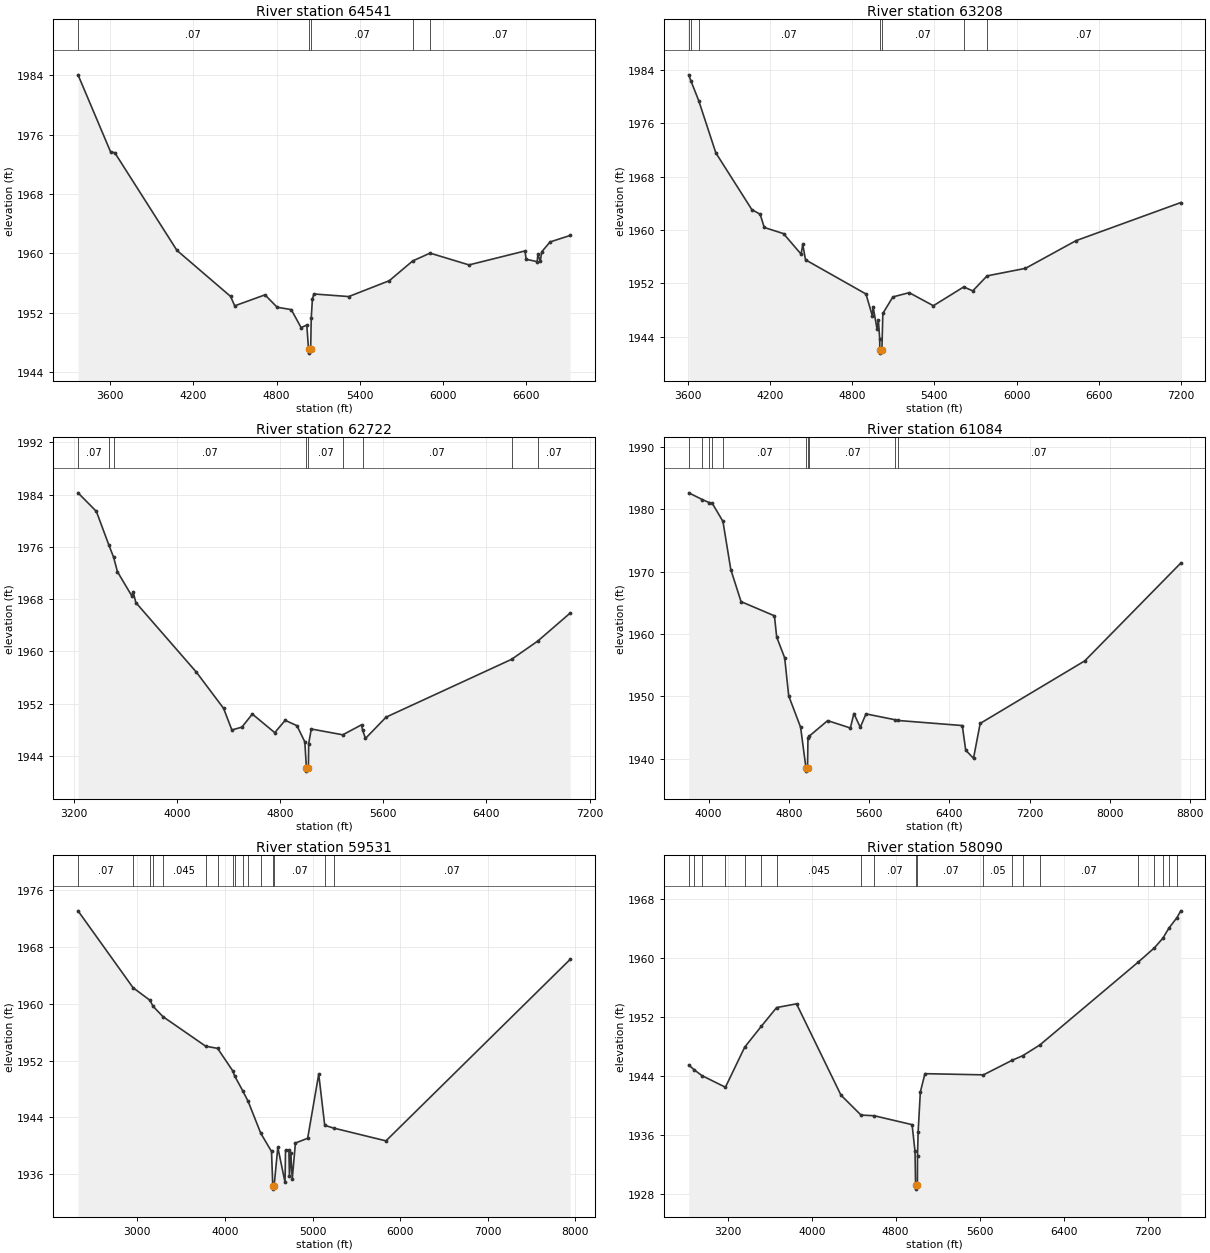
Type RM Length L Ch R = 1 ,64541   ,1333,1333,1333
BEGIN DESCRIPTION:
East China Creek 32.0
END DESCRIPTION:
XS GIS Cut Line= 3
      1420094.42      6914896.05        1421705.        6914588.
      1423597.91      6914342.83
#Sta/Elev= 30
  3367.9 1984.07  3602.7 1973.68  3633.2 1973.56  4081.2 1960.39  4468.1 1954.18
  4497.8 1952.91  4716.2 1954.39  4804.1 1952.72  4905.9  1952.4  4976.6 1949.97
  5017.8 1950.32  5030.3 1947.03  5030.8 1946.53  5045.6 1947.03  5049.8 1951.26
  5058.1 1953.79  5068.2 1954.51  5320.3 1954.16  5612.7  1956.3    5781 1958.96
  5906.7 1960.02  6187.4 1958.43  6590.8 1960.31  6599.8 1959.19    6679 1958.87
  6684.1 1959.84  6701.7 1958.93  6711.8  1960.2  6772.3 1961.53  6916.4  1962.4
#Mann= 5 ,-1 , 0
  3367.9     .07       0  5030.3     .07       0  5045.6     .07       0
    5781    .035       0  5906.7     .07       0
Bank Sta=5030.3,5045.6
XS Rating Curve= 0 ,0
Exp/Cntr=0.3,0.1

Type RM Length L Ch R = 1 ,63208   ,486,486,486
BEGIN DESCRIPTION:
East China Creek 31.0
END DESCRIPTION:
XS GIS Cut Line= 3
      1420365.67      6915503.69        1421755.        6915638.
      1423696.83       6914603.1
#Sta/Elev= 30
  3604.6 1983.27  3619.9 1982.39  3677.4  1979.4  3802.6 1971.56  4066.1 1963.04
  4126.3 1962.36  4156.5 1960.37  4297.1 1959.45  4425.8 1956.37  4437.8 1957.86
  4457.9 1955.52  4899.9 1950.39  4946.8 1947.09  4951.8 1948.49  4980.3 1945.19
  4990.4  1946.5  5000.4 1943.59  5000.9 1942.02  5001.4 1941.52  5016.3 1942.02
  5023.1 1947.47  5096.4 1949.95  5215.7 1950.59  5392.5 1948.63  5613.9 1951.45
  5680.3 1950.86  5785.1 1953.11  6065.6 1954.24  6434.7 1958.39  7200.8 1964.11
#Mann= 7 ,-1 , 0
  3604.6     .07       0  3619.9     .16       0  3677.4     .07       0
  5000.9     .07       0  5016.3     .07       0  5613.9    .035       0
  5785.1     .07       0
Bank Sta=5000.9,5016.3
XS Rating Curve= 0 ,0
Exp/Cntr=0.3,0.1

Type RM Length L Ch R = 1 ,62722   ,1638,1638,1638
BEGIN DESCRIPTION:
East China Creek 30.0
END DESCRIPTION:
XS GIS Cut Line= 3
      1420213.76      6915666.44        1421955.        6915988.
      1424000.32      6915861.79
#Sta/Elev= 30
  3229.3 1984.29  3371.7 1981.45  3469.9 1976.24  3505.8 1974.41  3535.6  1972.2
  3646.6 1968.52  3657.7 1969.11    3678 1967.49  4148.7 1956.82  4359.3 1951.29
  4423.6 1947.98  4501.7 1948.42  4582.5 1950.42  4756.6 1947.57  4837.3 1949.46
  4928.8 1948.64  4989.8 1946.17  5002.3 1942.18  5002.8 1941.68  5017.7 1942.18
    5020  1945.9  5040.1 1948.13  5284.9 1947.24  5430.8 1948.78  5438.1 1947.96
  5460.9 1946.69  5621.2 1949.95  6595.2  1958.8  6798.7  1961.6  7049.2 1965.87
#Mann= 9 ,-1 , 0
  3229.3     .07       0  3469.9     .16       0  3505.8     .07       0
  5002.3     .07       0  5017.7     .07       0  5284.9    .035       0
  5438.1     .07       0  6595.2     .16       0  6798.7     .07       0
Bank Sta=5002.3,5017.7
XS Rating Curve= 0 ,0
Exp/Cntr=0.3,0.1

Type RM Length L Ch R = 1 ,61084   ,1553,1553,1553
BEGIN DESCRIPTION:
Mapping XS a20b6ed4
END DESCRIPTION:
XS GIS Cut Line= 4
       1420105.3      6915840.07      1421233.75       6916382.6
       1421906.5      6917044.49       1424347.5      6915872.81
#Sta/Elev= 30
  3802.5 1982.63  3938.5 1981.54  4007.1 1981.06  4034.8    1981  4143.2 1978.05
  4221.5 1970.33  4323.7 1965.18  4656.5  1962.9  4678.7 1959.51  4758.7 1956.15
  4798.4 1950.07  4917.2 1945.03  4970.6 1938.49  4971.1 1937.99  4986.1 1938.49
  4990.6  1943.3    5003  1943.6  5186.6 1946.09  5412.9 1944.91  5448.3 1947.23
  5511.9 1945.01  5568.4 1947.17  5862.4 1946.22  5884.4 1946.12  6528.4  1945.3
  6562.4 1941.35  6640.1 1940.05  6706.6 1945.64  7749.3 1955.68    8706 1971.37
#Mann= 10 ,-1 , 0
  3802.5     .07       0  3938.5    .035       0  4007.1     .07       0
  4034.8    .035       0  4143.2     .07       0  4970.6     .07       0
  4986.1     .07       0    5003     .07       0  5862.4     .16       0
  5884.4     .07       0
Bank Sta=4970.6,4986.1
XS Rating Curve= 0 ,0
Exp/Cntr=0.3,0.1

Type RM Length L Ch R = 1 ,59531   ,1441,1441,1441
BEGIN DESCRIPTION:
East China Creek 28.0
END DESCRIPTION:
XS GIS Cut Line= 3
      1419291.47       6918737.2        1421655.        6917488.
      1424250.14      6916100.54
#Sta/Elev= 30
  2322.5 1973.13  2950.8 1962.28  3143.5 1960.51  3178.2 1959.67  3291.9  1958.2
  3779.4 1954.03  3915.7 1953.72    4088 1950.56  4108.7 1949.87  4201.7 1947.75
  4264.7 1946.23    4408 1941.75  4531.1 1939.17  4545.3 1934.36  4545.8 1933.86
  4560.9 1934.36  4602.8 1939.76  4685.2 1934.83  4690.8 1939.36  4729.2 1939.34
  4735.7 1935.76  4751.2 1939.01  4767.6 1935.27  4803.6 1940.36  4943.6 1941.04
  5069.8 1950.09  5138.1 1942.86  5238.9 1942.48  5837.1 1940.67  7938.6 1966.27
#Mann= 16 ,-1 , 0
  2322.5     .07       0  2950.8    .035       0  3143.5    .045       0
  3178.2    .035       0  3291.9    .045       0  3779.4     .07       0
  3915.7    .035       0    4088     .07       0  4108.7    .035       0
  4201.7     .07       0  4264.7    .035       0    4408     .07       0
  4545.3     .07       0  4560.9     .07       0  5138.1     .16       0
  5238.9     .07       0
Bank Sta=4545.3,4560.9
XS Rating Curve= 0 ,0
Exp/Cntr=0.3,0.1

Type RM Length L Ch R = 1 ,58090   ,1606,1606,1606
BEGIN DESCRIPTION:
East China Creek 25.0
END DESCRIPTION:
XS GIS Cut Line= 3
      1420467.51      6919130.76      1422328.41      6918011.25
      1424358.77      6916523.65
#Sta/Elev= 30
  2828.3 1945.44  2881.5 1944.79  2951.9 1944.02  3177.9 1942.43  3361.4 1947.87
  3519.2 1950.69  3665.5 1953.24  3855.1 1953.75  4278.6 1941.36  4469.7 1938.65
  4595.1 1938.56  4956.5 1937.35  4984.3 1933.72  4989.7  1929.1  4990.2  1928.6
    5007  1929.1    5008 1933.06  5014.2 1936.38    5035 1941.77    5079 1944.27
  5636.7 1944.11  5909.8 1946.09  6011.2 1946.71  6174.3 1948.17  7109.4 1959.39
    7265 1961.34  7346.4 1962.66  7402.9 1964.01  7480.7 1965.46    7517 1966.37
#Mann= 20 ,-1 , 0
  2828.3     .07       0  2881.5    .035       0  2951.9     .07       0
  3177.9    .035       0  3361.4    .045       0  3519.2    .035       0
  3665.5    .045       0  4469.7     .07       0  4595.1     .07       0
  4989.7     .07       0    5007     .07       0  5636.7     .05       0
  5909.8     .07       0  6011.2     .05       0  6174.3     .07       0
  7109.4     .07       0    7265    .035       0  7346.4     .07       0
  7402.9    .035       0  7480.7     .07       0
Bank Sta=4989.7,5007
XS Rating Curve= 0 ,0
Exp/Cntr=0.3,0.1