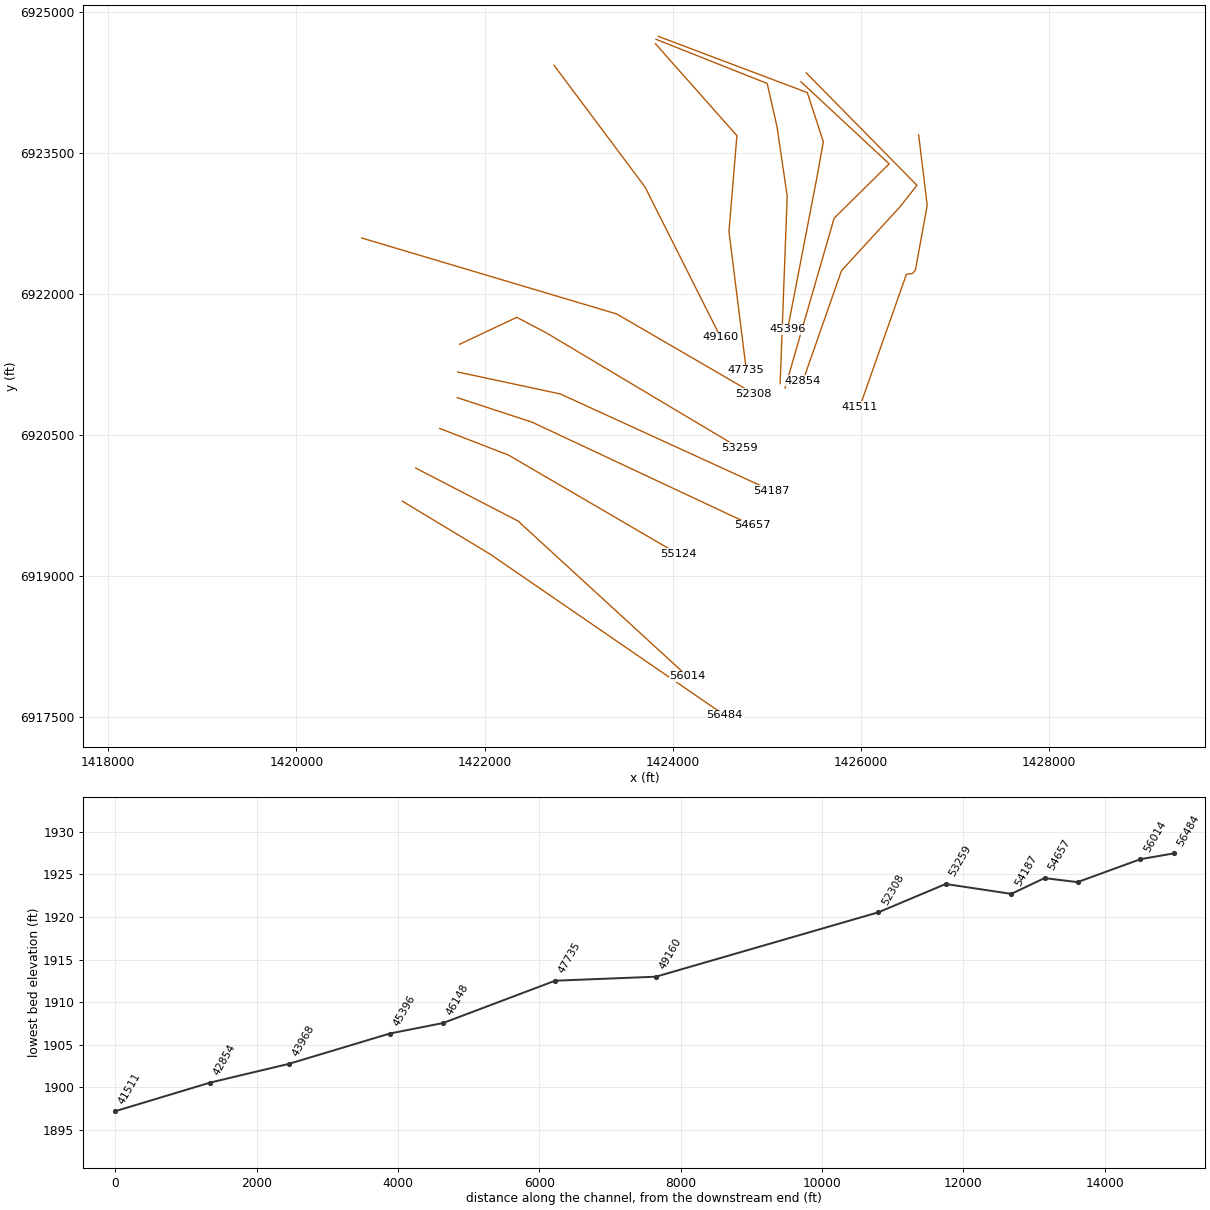
HEC-RAS study East China Creek.prj: East China Creek Base Level Engineering

--- East China Creek.g01 (geometry) --- (continued)

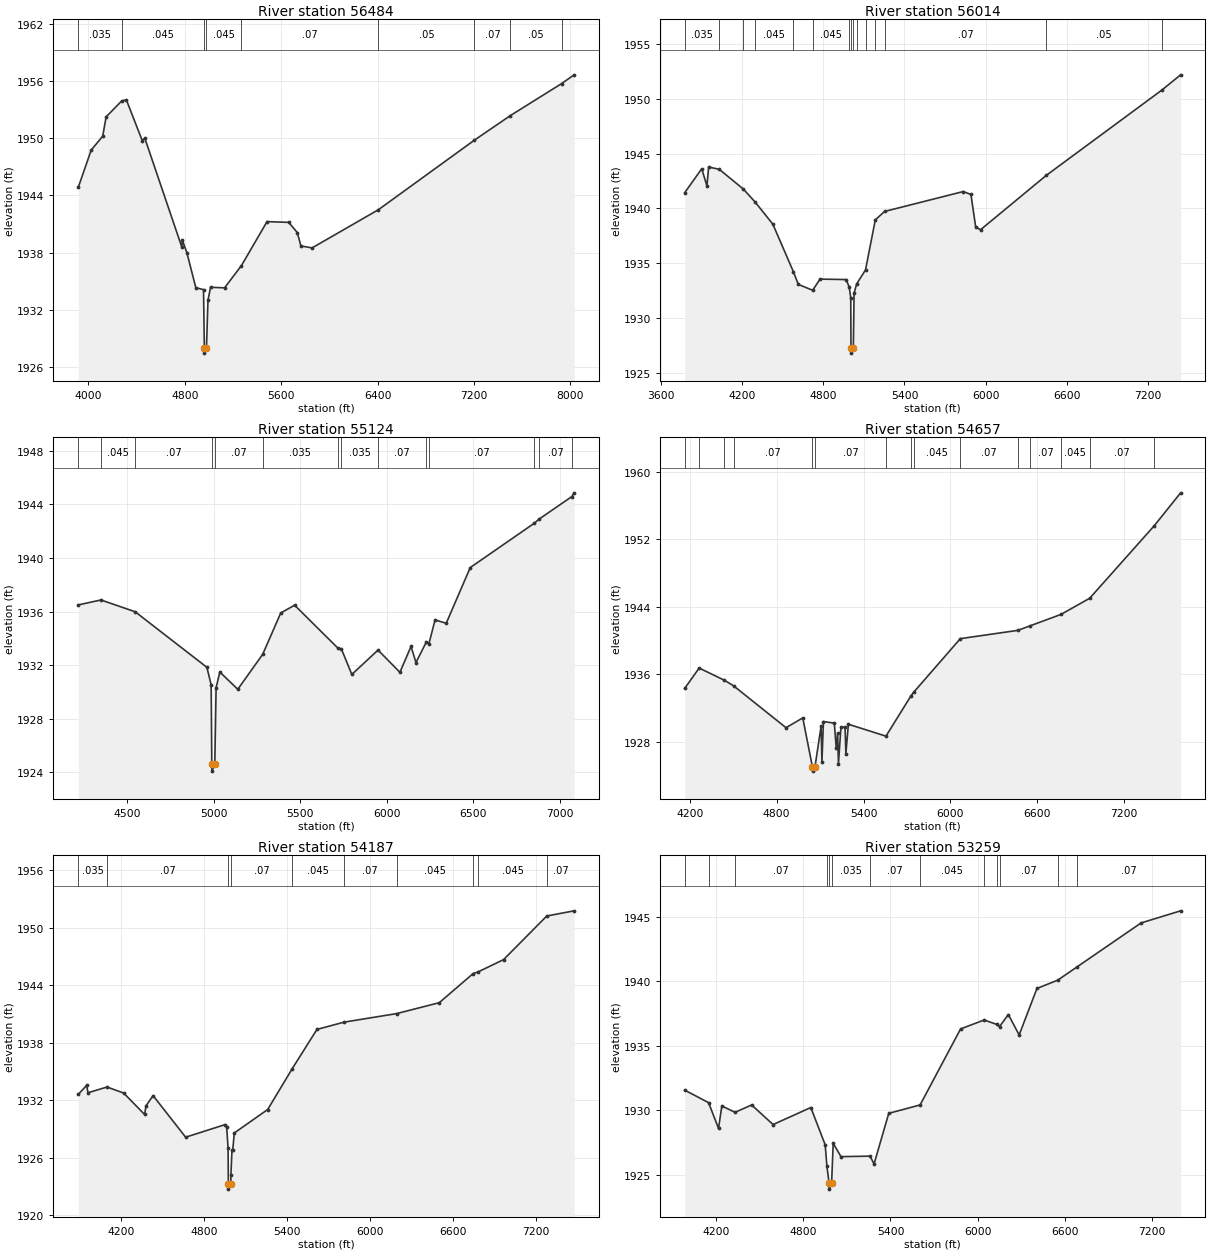
Type RM Length L Ch R = 1 ,56484   ,470,470,470
BEGIN DESCRIPTION:
East China Creek 24.0
END DESCRIPTION:
XS GIS Cut Line= 3
      1421126.63      6919798.41        1422055.        6919238.
      1424553.29      6917522.46
#Sta/Elev= 30
  3915.6 1944.84  4023.7 1948.77  4118.8 1950.22  4147.3 1952.25  4275.5 1953.91
  4314.9 1954.04  4446.8 1949.76  4468.2 1950.01  4774.9  1938.6  4780.7 1939.28
  4817.6 1937.98  4891.3 1934.33  4955.4 1934.12  4962.2 1927.96  4962.7 1927.46
  4979.6 1927.96  4992.2 1932.99  5013.5 1934.37  5129.9 1934.31  5270.2 1936.65
  5482.5 1941.26  5661.8 1941.18  5733.5 1940.11  5763.3 1938.71    5856  1938.5
  6405.6  1942.5  7203.5 1949.81  7502.2 1952.39  7926.3 1955.74  8030.6 1956.66
#Mann= 9 ,-1 , 0
  3915.6    .035       0  4275.5    .045       0  4962.2    .045       0
  4979.6    .045       0  5270.2     .07       0  6405.6     .05       0
  7203.5     .07       0  7502.2     .05       0  7926.3     .07       0
Bank Sta=4962.2,4979.6
XS Rating Curve= 0 ,0
Exp/Cntr=0.3,0.1

Type RM Length L Ch R = 1 ,56014   ,890,890,890
BEGIN DESCRIPTION:
East China Creek 23.0
END DESCRIPTION:
XS GIS Cut Line= 3
      1421267.77      6920150.77        1422355.        6919588.
      1424155.02      6917937.98
#Sta/Elev= 30
  3775.4 1941.43  3901.4 1943.62  3940.1 1942.05  3952.4 1943.78    4031 1943.57
  4207.8 1941.78  4294.3 1940.61  4427.1 1938.56  4579.6  1934.2  4615.1 1933.06
  4721.6 1932.52  4775.6 1933.54  4969.3  1933.5  4991.6 1932.81    5003 1931.82
  5004.8 1927.28  5005.3 1926.78  5022.2 1927.28  5027.7 1932.25  5046.6  1933.1
  5112.1 1934.38  5184.6 1938.95  5252.7 1939.72  5834.9 1941.54  5891.6 1941.27
  5926.7 1938.29  5962.5 1938.05  6447.9 1943.01  7303.2 1950.81  7441.5  1952.2
#Mann= 15 ,-1 , 0
  3775.4    .035       0    4031    .045       0  4207.8     .07       0
  4294.3    .045       0  4579.6    .035       0  4721.6    .045       0
  4991.6     .07       0  5004.8     .07       0  5022.2     .07       0
  5046.6    .045       0  5112.1     .07       0  5184.6    .035       0
  5252.7     .07       0  6447.9     .05       0  7303.2     .07       0
Bank Sta=5004.8,5022.2
XS Rating Curve= 0 ,0
Exp/Cntr=0.3,0.1

Type RM Length L Ch R = 1 ,55124   ,467,467,467
BEGIN DESCRIPTION:
East China Creek 21.0
END DESCRIPTION:
XS GIS Cut Line= 3
      1421524.18       6920570.9        1422255.        6920288.
      1424054.97      6919238.02
#Sta/Elev= 30
  4216.1  1936.5  4347.6 1936.87  4545.4 1935.99  4960.2 1931.84  4984.8 1930.53
  4988.4 1924.59  4988.9 1924.09  5005.8 1924.59  5013.4 1930.32  5034.9 1931.49
  5138.7  1930.2  5282.7 1932.81  5387.2  1935.9  5467.4 1936.48  5716.5 1933.29
  5737.8 1933.21  5798.2 1931.31  5949.7 1933.13    6076 1931.47  6140.5  1933.4
    6169  1932.2  6229.7 1933.75  6244.1 1933.61  6279.4 1935.38  6343.9 1935.13
  6482.9 1939.29  6850.9 1942.58  6882.4 1942.92  7070.1 1944.59  7083.6 1944.87
#Mann= 14 ,-1 , 0
  4216.1    .035       0  4347.6    .045       0  4545.4     .07       0
  4988.4     .07       0  5005.8     .07       0  5282.7    .035       0
  5716.5     .07       0  5737.8    .035       0  5949.7     .07       0
  6229.7    .035       0  6244.1     .07       0  6850.9    .045       0
  6882.4     .07       0  7070.1    .045       0
Bank Sta=4988.4,5005.8
XS Rating Curve= 0 ,0
Exp/Cntr=0.3,0.1

Type RM Length L Ch R = 1 ,54657   ,470,470,470
BEGIN DESCRIPTION:
East China Creek 20.0
END DESCRIPTION:
XS GIS Cut Line= 3
      1421710.53      6920898.78        1422505.        6920638.
      1424847.08      6919540.13
#Sta/Elev= 30
  4165.6 1934.35  4265.5 1936.76  4438.2 1935.33  4502.9 1934.66  4864.9  1929.7
  4980.6 1930.86  5047.3 1925.06  5047.8 1924.56  5064.8 1925.06  5107.2 1929.89
  5112.8 1925.63  5123.3 1930.43  5198.5 1930.24  5211.6 1927.29  5221.4 1929.05
  5226.9 1925.43  5244.2 1929.79  5272.5 1929.73  5278.1 1926.63  5295.4 1930.11
  5554.8  1928.7  5728.1 1933.49  5750.4 1933.98    6068 1940.24  6464.6 1941.22
    6550 1941.76  6762.9 1943.11  6960.7 1945.02  7405.7 1953.59  7588.4  1957.5
#Mann= 15 ,-1 , 0
  4165.6    .035       0  4265.5     .07       0  4438.2    .045       0
  4502.9     .07       0  5047.3     .07       0  5064.8     .07       0
  5554.8    .035       0  5728.1     .07       0  5750.4    .045       0
    6068     .07       0  6464.6    .035       0    6550     .07       0
  6762.9    .045       0  6960.7     .07       0  7405.7    .035       0
Bank Sta=5047.3,5064.8
XS Rating Curve= 0 ,0
Exp/Cntr=0.3,0.1

Type RM Length L Ch R = 1 ,54187   ,928,928,928
BEGIN DESCRIPTION:
East China Creek 19.0
END DESCRIPTION:
XS GIS Cut Line= 3
      1421715.68      6921171.07        1422805.        6920938.
      1425051.61       6919909.8
#Sta/Elev= 30
  3890.2 1932.59  3950.9 1933.54  3961.1 1932.77  4098.4 1933.37  4218.7 1932.74
  4370.1  1930.5  4380.4 1931.41  4431.5 1932.47  4666.7 1928.13    4953 1929.45
  4963.3 1929.17  4973.5 1926.99  4975.6 1923.21  4976.1 1922.71  4993.6 1923.21
    4994 1924.22  5001.6 1926.76  5006.9 1926.76  5018.4 1928.57  5259.6 1931.02
  5437.5 1935.29  5615.7 1939.38  5811.8 1940.14    6191 1941.03  6499.8 1942.17
  6744.7 1945.21  6781.3 1945.39  6964.9 1946.67    7277 1951.22  7474.9 1951.76
#Mann= 10 ,-1 , 0
  3890.2    .035       0  4098.4     .07       0  4975.6     .07       0
  4993.6     .07       0  5437.5    .045       0  5811.8     .07       0
    6191    .045       0  6744.7     .07       0  6781.3    .045       0
    7277     .07       0
Bank Sta=4975.6,4993.6
XS Rating Curve= 0 ,0
Exp/Cntr=0.3,0.1

Type RM Length L Ch R = 1 ,53259   ,951,951,951
BEGIN DESCRIPTION:
East China Creek 18.0
END DESCRIPTION:
XS GIS Cut Line= 4
      1421734.83      6921465.84      1422342.48      6921752.31
        1422655.        6921588.      1424705.97       6920364.8
#Sta/Elev= 30
  3983.9 1931.55  4148.3 1930.58  4216.8 1928.58  4239.5 1930.32  4330.6 1929.83
  4444.6  1930.4  4592.3 1928.88  4851.9  1930.2  4950.8 1927.31  4962.8 1925.65
  4977.1 1924.37  4977.6 1923.87  4995.2 1924.37  5005.9 1927.43  5059.4 1926.39
  5259.9 1926.43  5287.1 1925.82  5388.3 1929.75  5603.8  1930.4  5882.7  1936.3
  6044.4 1936.99  6131.5 1936.65  6150.4 1936.48  6211.6 1937.41  6285.6 1935.83
  6408.2 1939.44  6550.9 1940.08  6685.5 1941.12  7124.5 1944.52  7396.8 1945.46
#Mann= 13 ,-1 , 0
  3983.9     .05       0  4148.3    .035       0  4330.6     .07       0
  4962.8    .035       0  4977.1    .035       0  4995.2    .035       0
  5259.9     .07       0  5603.8    .045       0  6044.4     .07       0
  6131.5    .045       0  6150.4     .07       0  6550.9    .045       0
  6685.5     .07       0
Bank Sta=4977.1,4995.2
XS Rating Curve= 0 ,0
Exp/Cntr=0.3,0.1

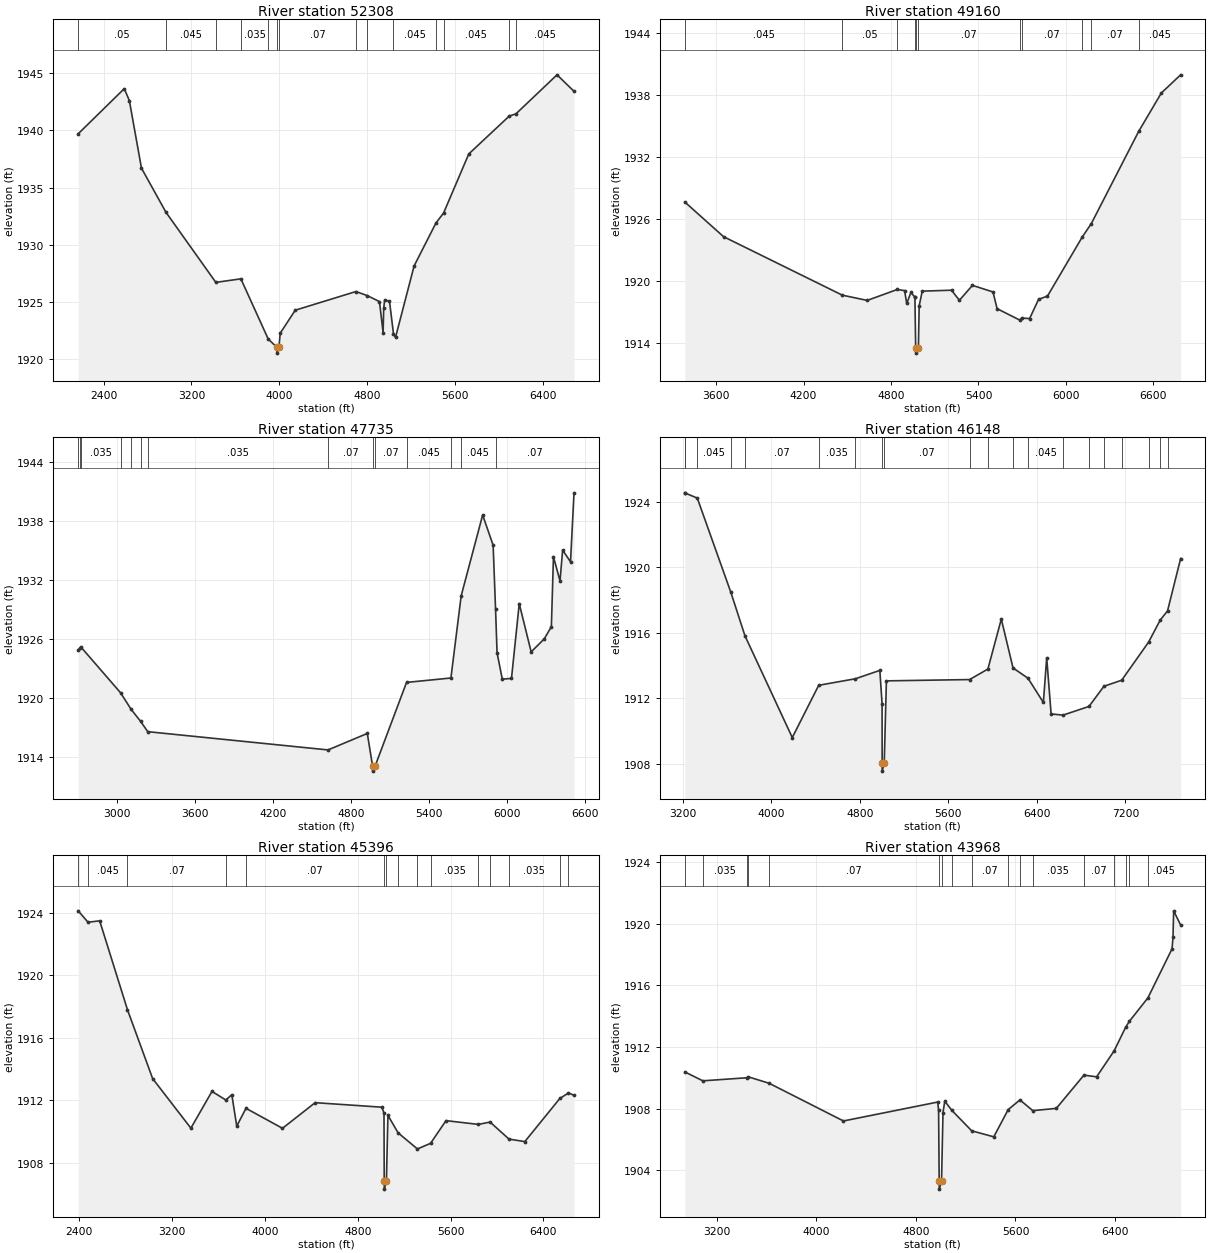
Type RM Length L Ch R = 1 ,52308   ,3148,3148,3148
BEGIN DESCRIPTION:
East China Creek 17.0
END DESCRIPTION:
XS GIS Cut Line= 3
      1420693.43      6922595.69        1423405.        6921788.
      1424859.19      6920942.56
#Sta/Elev= 30
  2169.5 1939.71  2588.5 1943.65  2634.9 1942.61    2745 1936.71  2967.6 1932.86
  3421.8 1926.73  3649.7 1927.04    3898 1921.79  3977.6 1921.05  3978.1 1920.55
  3995.7 1921.05  4007.6 1922.29  4144.5  1924.3  4696.7 1925.93  4800.9 1925.57
  4910.7 1925.05  4943.8 1922.33  4949.1 1924.45  4957.1 1925.15  5001.7  1925.1
  5038.1 1922.25  5056.6 1921.92    5226 1928.17  5424.2 1931.91  5494.1 1932.79
  5723.4 1937.95  6091.8 1941.26  6152.2 1941.45  6526.2 1944.86  6680.9 1943.42
#Mann= 14 ,-1 , 0
  2169.5     .05       0  2967.6    .045       0  3421.8     .05       0
  3649.7    .035       0    3898     .07       0  3977.6     .07       0
  3995.7     .07       0  4696.7    .035       0  4800.9     .07       0
  5038.1    .045       0  5424.2     .07       0  5494.1    .045       0
  6091.8     .07       0  6152.2    .045       0
Bank Sta=3977.6,3995.7
XS Rating Curve= 0 ,0
Exp/Cntr=0.3,0.1

Type RM Length L Ch R = 1 ,49160   ,1425,1425,1425
BEGIN DESCRIPTION:
East China Creek 15.0
END DESCRIPTION:
XS GIS Cut Line= 3
      1422737.68      6924431.61        1423705.        6923138.
        1424508.        6921542.
#Sta/Elev= 30
    3385 1927.64  3650.8 1924.28  4465.6 1918.61  4636.6  1918.1  4842.8 1919.16
  4892.9 1919.05  4907.5 1917.81  4936.7 1918.87  4962.6 1918.43  4963.8  1918.4
    4969 1913.49  4969.5 1912.99  4987.7 1913.49    4993 1917.58  5014.2    1919
  5215.1 1919.09  5268.9 1918.11  5358.5 1919.56  5499.7 1918.92  5527.6  1917.3
  5682.4  1916.2  5696.2 1916.39  5750.8 1916.34  5812.1  1918.2  5873.4 1918.52
  6112.5 1924.26  6173.8 1925.54  6498.9 1934.48  6654.7 1938.21  6786.9 1939.97
#Mann= 11 ,-1 , 0
    3385    .045       0  4465.6     .05       0  4842.8    .035       0
  4962.6     .07       0    4969     .07       0  4987.7     .07       0
  5682.4    .045       0  5696.2     .07       0  6112.5    .045       0
  6173.8     .07       0  6498.9    .045       0
Bank Sta=4969,4987.7
XS Rating Curve= 0 ,0
Exp/Cntr=0.3,0.1

Type RM Length L Ch R = 1 ,47735   ,1587,1587,1587
BEGIN DESCRIPTION:
Mapping XS 2e8d4327
END DESCRIPTION:
XS GIS Cut Line= 4
      1423817.31      6924658.67       1424681.9      6923682.97
      1424597.47      6922665.15      1424781.71      6921191.19
#Sta/Elev= 30
  2702.9  1924.9  2719.6 1925.06  2726.9 1925.12  3028.1 1920.51  3109.9 1918.81
  3182.4 1917.59  3237.6 1916.54  4622.9 1914.68  4924.7 1916.36  4965.4 1913.02
  4965.9 1912.52  4984.2 1913.02  5226.2 1921.56  5567.2 1922.01  5646.2 1930.39
  5811.1 1938.62  5891.7 1935.54  5910.4    1929  5921.9 1924.57  5962.2 1921.89
  6032.8 1921.97  6092.3 1929.59  6183.9 1924.67  6284.7    1926  6339.2 1927.24
  6355.3 1934.37  6405.7  1931.9  6425.8 1935.04  6486.3 1933.85  6513.3 1940.88
#Mann= 14 ,-1 , 0
  2702.9    .035       0  2719.6     .07       0  2726.9    .035       0
  3028.1     .07       0  3109.9    .035       0  3182.4     .07       0
  3237.6    .035       0  4622.9     .07       0  4965.4     .07       0
  4984.2     .07       0  5226.2    .045       0  5567.2     .07       0
  5646.2    .045       0  5910.4     .07       0
Bank Sta=4965.4,4984.2
XS Rating Curve= 0 ,0
Exp/Cntr=0.3,0.1

Type RM Length L Ch R = 1 ,46148   ,752,752,752
BEGIN DESCRIPTION:
Mapping XS 026d4a12
END DESCRIPTION:
XS GIS Cut Line= 5
      1423822.11      6924706.89      1425003.72      6924237.62
      1425107.45       6923780.6      1425216.39      6923042.01
      1425141.28      6921048.23
#Sta/Elev= 30
  3217.7 1924.54  3222.6 1924.52  3330.4 1924.22  3634.2 1918.46  3761.5 1915.81
  4189.2  1909.6  4427.9 1912.79  4760.4 1913.19  4980.6  1913.7  5000.8 1911.67
  5001.5 1908.05    5002 1907.55  5020.3 1908.05  5039.9 1913.06  5791.8 1913.14
  5957.2 1913.78  6078.6 1916.83  6184.5 1913.85    6320 1913.22  6458.9 1911.74
  6488.9 1914.47  6528.9 1911.04    6637 1910.97  6871.1  1911.5  7006.4 1912.73
  7166.7  1913.1  7410.3 1915.43  7514.8 1916.77    7581 1917.33  7699.5 1920.53
#Mann= 20 ,-1 , 0
  3217.7    .035       0  3222.6     .07       0  3330.4    .045       0
  3634.2    .035       0  3761.5     .07       0  4427.9    .035       0
  4760.4     .07       0  5001.5     .07       0  5020.3     .07       0
  5791.8    .035       0  5957.2    .045       0  6184.5     .07       0
    6320    .045       0    6637    .035       0  6871.1    .045       0
  7006.4     .07       0  7166.7    .035       0  7410.3    .045       0
  7514.8    .035       0    7581    .045       0
Bank Sta=5001.5,5020.3
XS Rating Curve= 0 ,0
Exp/Cntr=0.3,0.1

Type RM Length L Ch R = 1 ,45396   ,1428,1428,1428
BEGIN DESCRIPTION:
Mapping XS 42243b25
END DESCRIPTION:
XS GIS Cut Line= 5
      1423846.41      6924738.14       1425429.7      6924140.93
      1425600.63      6923617.87      1425527.71      6923216.83
      1425220.42      6921623.06
#Sta/Elev= 30
  2390.4 1924.12    2475 1923.39  2575.5 1923.48  2814.7  1917.8  3031.9 1913.39
  3361.5 1910.22  3543.4 1912.57  3662.7 1912.02  3714.2 1912.36  3756.9 1910.35
  3836.4 1911.49    4151 1910.21  4432.6 1911.85  5008.8 1911.56  5025.9 1911.17
  5027.9 1906.82  5028.4 1906.32  5046.7 1906.82  5059.7 1911.04  5147.4 1909.92
  5314.1 1908.89  5427.4 1909.25  5560.2  1910.7    5840 1910.46  5940.2 1910.61
  6103.1 1909.52  6239.6 1909.36  6541.5 1912.12  6615.8 1912.47  6663.6 1912.32
#Mann= 15 ,-1 , 0
  2390.4     .07       0    2475    .045       0  2814.7     .07       0
  3662.7    .035       0  3836.4     .07       0  5027.9     .07       0
  5046.7     .07       0  5147.4    .035       0  5314.1     .07       0
  5427.4    .035       0    5840     .07       0  5940.2    .045       0
  6103.1    .035       0  6541.5    .045       0  6615.8     .07       0
Bank Sta=5027.9,5046.7
XS Rating Curve= 0 ,0
Exp/Cntr=0.3,0.1

Type RM Length L Ch R = 1 ,43968   ,1114,1114,1114
BEGIN DESCRIPTION:
Mapping XS 7f2e1819
END DESCRIPTION:
XS GIS Cut Line= 4
      1425362.62      6924255.68      1426300.13      6923383.28
      1425715.09      6922806.21      1425193.72      6921001.71
#Sta/Elev= 30
  2945.3 1910.38  3089.8  1909.8  3445.3    1910  3450.8 1910.07  3622.7 1909.64
  4218.9 1907.19  4975.8 1908.42  4982.8 1907.89  4987.6 1903.26  4988.1 1902.76
  5006.4 1903.26  5018.2 1907.74  5032.4 1908.48  5089.2 1907.88  5248.7 1906.55
    5426 1906.16  5541.7 1907.93  5636.1 1908.56  5739.2 1907.86    5928 1908.01
  6149.7 1910.17  6251.5 1910.06  6392.2 1911.75  6483.9 1913.27  6515.5 1913.68
  6663.2 1915.19    6857 1918.38  6864.8 1919.12    6870 1920.85    6926 1919.93
#Mann= 17 ,-1 , 0
  2945.3     .07       0  3089.8    .035       0  3445.3     .07       0
  3450.8    .035       0  3622.7     .07       0  4987.6     .07       0
  5006.4     .07       0  5089.2    .035       0  5248.7     .07       0
  5541.7    .035       0  5636.1     .07       0  5739.2    .035       0
  6149.7     .07       0  6392.2    .035       0  6483.9     .07       0
  6515.5    .035       0  6663.2    .045       0
Bank Sta=4987.6,5006.4
XS Rating Curve= 0 ,0
Exp/Cntr=0.3,0.1

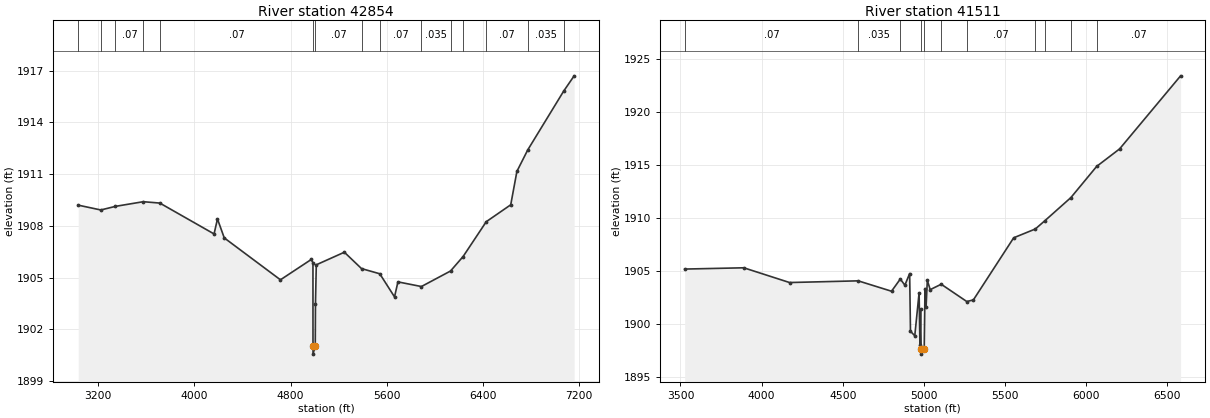
Type RM Length L Ch R = 1 ,42854   ,1343,1343,1343
BEGIN DESCRIPTION:
Mapping XS dec8beb2
END DESCRIPTION:
XS GIS Cut Line= 5
      1425418.52      6924350.53      1426595.31       6923155.4
      1426418.34      6922930.37      1425793.34      6922247.69
      1425384.33      6921078.58
#Sta/Elev= 30
  3032.6  1909.2  3220.6 1908.92  3342.9 1909.13  3574.2  1909.4  3711.9 1909.32
  4163.3 1907.53  4191.6  1908.4  4248.2  1907.3  4715.7 1904.87  4972.3 1906.05
  4986.4 1905.86  4986.7 1901.06  4987.2 1900.56  5005.5 1901.06  5007.3 1903.49
  5014.1 1905.74  5247.8 1906.47  5390.6 1905.52  5542.5 1905.22  5665.3 1903.88
  5693.6 1904.75  5888.9 1904.48  6131.3 1905.38    6236 1906.22  6428.7 1908.24
  6632.4 1909.22  6683.9 1911.16  6773.8  1912.4  7073.7 1915.82  7160.3  1916.7
#Mann= 15 ,-1 , 0
  3032.6     .07       0  3220.6    .035       0  3342.9     .07       0
  3574.2    .035       0  3711.9     .07       0  4986.7     .07       0
  5005.5     .07       0  5390.6    .035       0  5542.5     .07       0
  5888.9    .035       0  6131.3     .07       0    6236    .035       0
  6428.7     .07       0  6773.8    .035       0  7073.7     .07       0
Bank Sta=4986.7,5005.5
XS Rating Curve= 0 ,0
Exp/Cntr=0.3,0.1

Type RM Length L Ch R = 1 ,41511   ,30,30,30
BEGIN DESCRIPTION:
Mapping XS 5ccfc538
END DESCRIPTION:
XS GIS Cut Line= 6
      1426613.37      6923689.54      1426704.51      6922943.04
      1426578.64      6922252.94      1426548.26      6922218.21
      1426483.16      6922209.53      1425988.37      6920803.29
#Sta/Elev= 30
  3526.2 1905.22  3890.4 1905.34  4172.5 1903.95  4595.3 1904.11  4800.8 1903.13
  4854.9 1904.28  4883.1  1903.7  4912.5  1904.8  4917.6 1899.36  4944.1 1898.93
  4970.8 1902.99  4975.9 1898.07  4979.7 1901.43  4983.5  1897.7    4984  1897.2
  5002.3  1897.7  5007.1 1903.38  5013.8 1901.66  5021.4 1904.16  5039.2 1903.28
    5107 1903.79  5264.5 1902.16  5305.2 1902.31  5553.7 1908.17  5687.1    1909
  5745.9 1909.78  5906.1 1911.96    6065  1914.9  6206.3 1916.55  6582.3 1923.44
#Mann= 11 ,-1 , 0
  3526.2     .07       0  4595.3    .035       0  4854.9     .07       0
  4983.5     .07       0  5002.3     .07       0    5107    .035       0
  5264.5     .07       0  5687.1    .035       0  5745.9     .07       0
  5906.1    .035       0    6065     .07       0
Bank Sta=4983.5,5002.3
XS Rating Curve= 0 ,0
Exp/Cntr=0.3,0.1