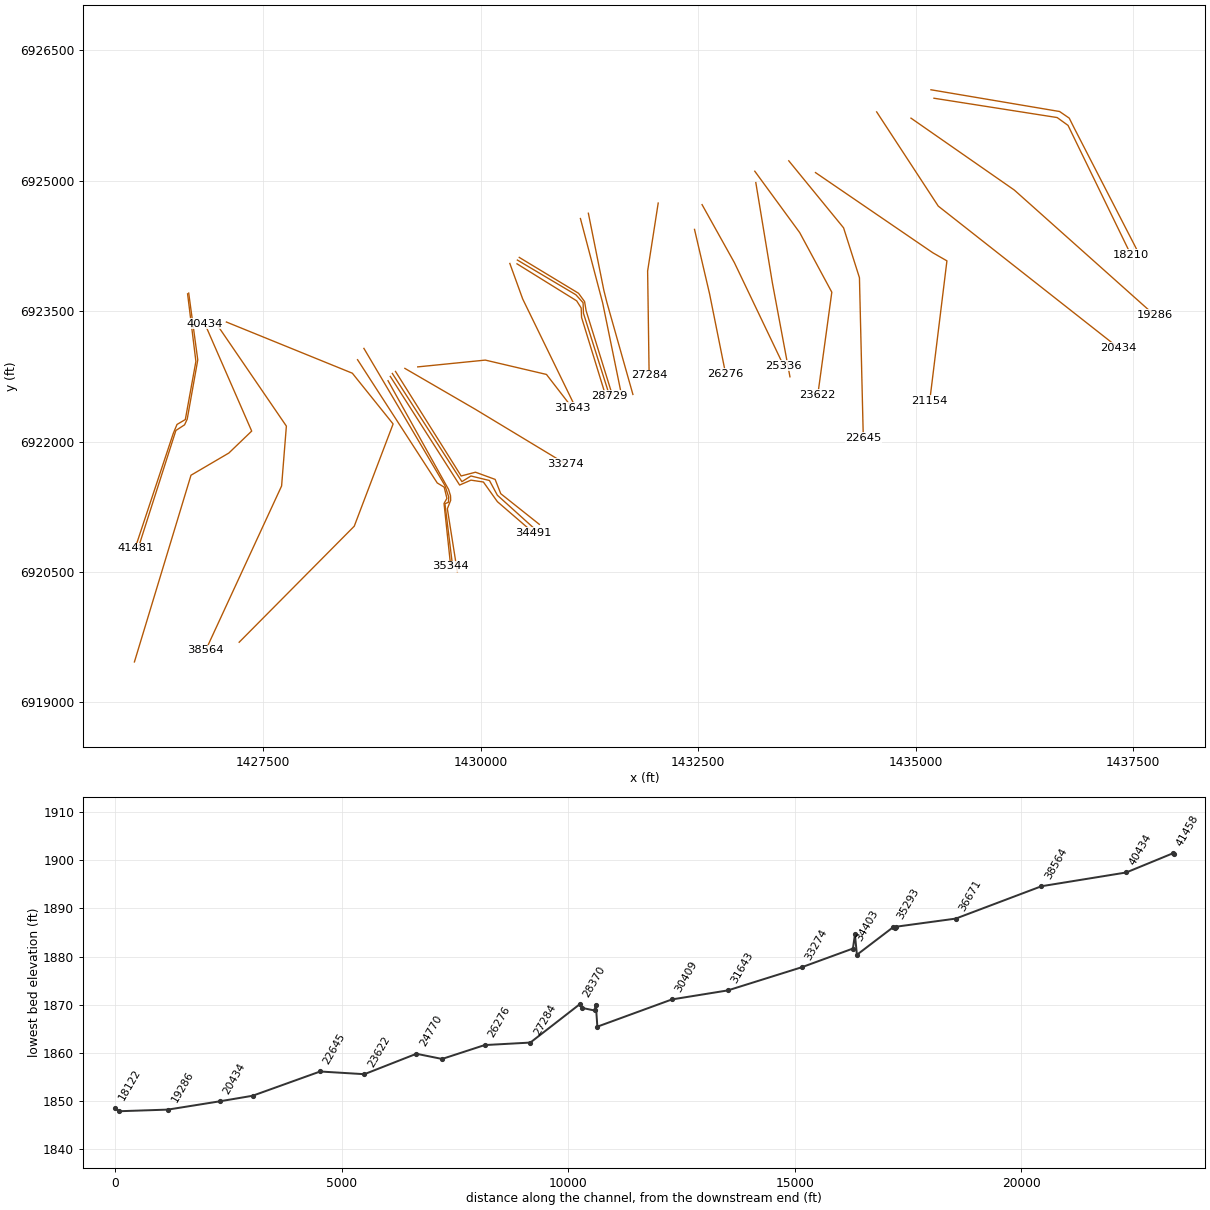
HEC-RAS study East China Creek.prj: East China Creek Base Level Engineering

--- East China Creek.g01 (geometry) --- (continued)

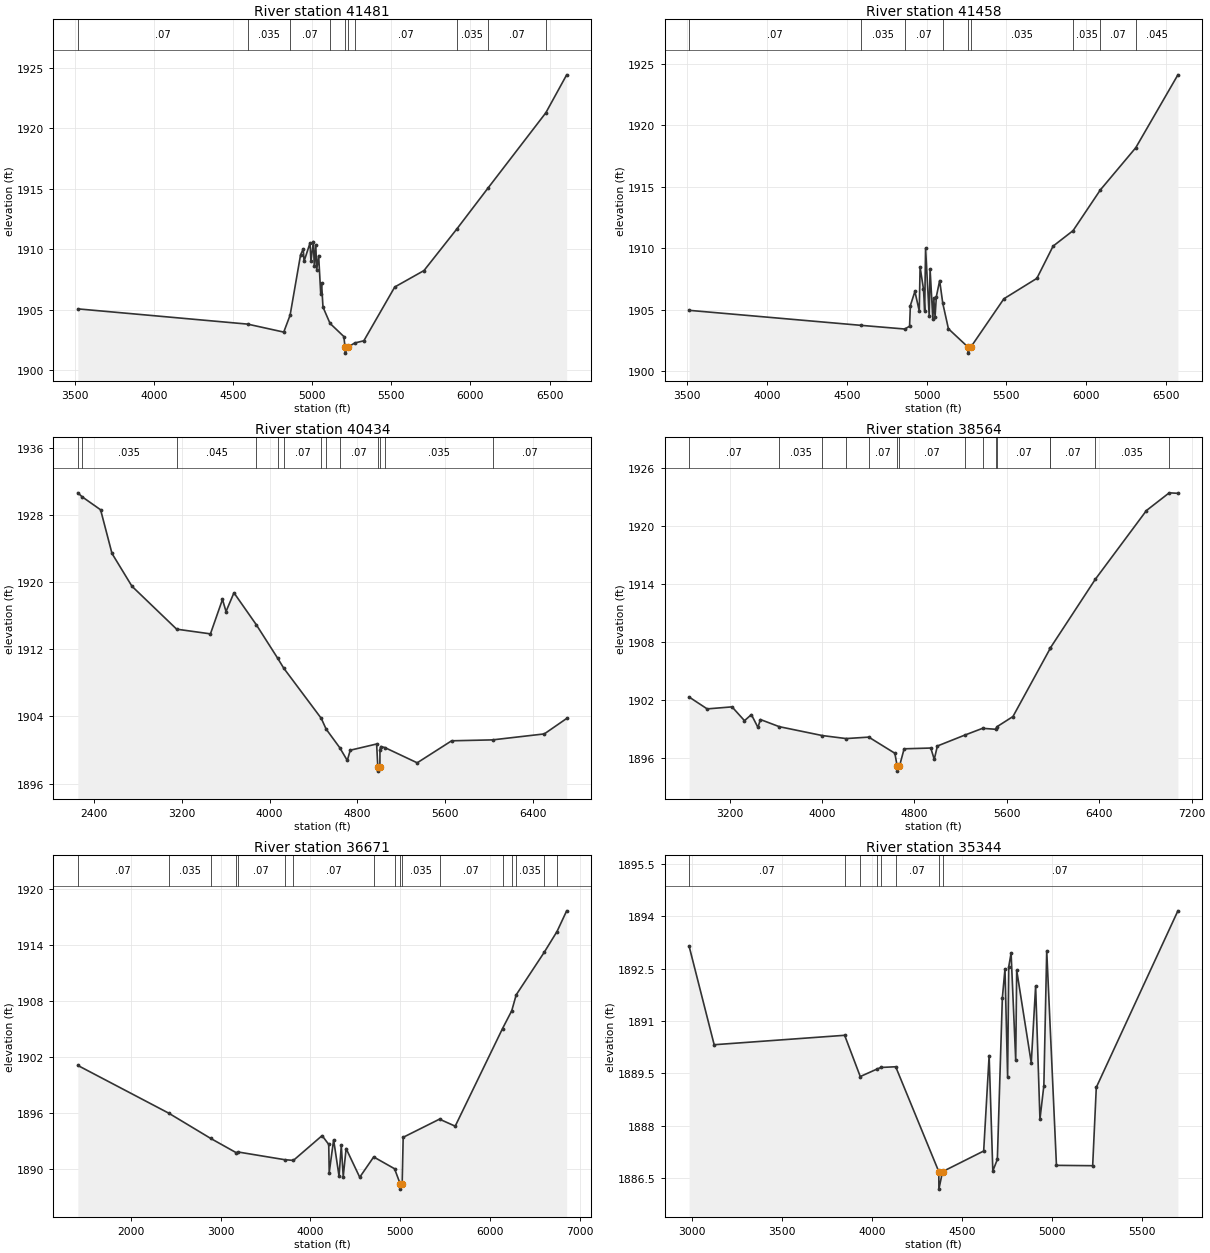
Type RM Length L Ch R = 1 ,41481   ,23,23,23
BEGIN DESCRIPTION:
Mapping XS b62c1255
END DESCRIPTION:
XS GIS Cut Line= 6
      1426630.73      6923698.22      1426726.21      6922921.34
      1426604.68      6922252.94       1426509.2      6922196.51
      1426465.79      6922092.35      1426027.44      6920772.95
#Sta/Elev= 30
  3519.9 1905.07  4592.2 1903.81  4820.4 1903.15  4860.6 1904.55  4926.4 1909.52
  4943.7 1910.04  4948.7    1909  4986.4 1910.52  4992.3 1909.01  5007.6 1910.64
  5013.5 1908.59  5022.8 1910.32  5028.7 1908.31  5040.8 1909.48  5054.2 1906.28
  5059.2 1907.23  5068.2 1905.22  5112.8 1903.87  5200.2 1902.78  5207.4 1901.91
  5207.9 1901.41  5226.2 1901.91  5268.8 1902.25  5326.3 1902.43  5521.6 1906.88
  5706.3 1908.24  5913.2 1911.67    6111 1915.07  6475.9 1921.29  6607.5 1924.43
#Mann= 10 ,-1 , 0
  3519.9     .07       0  4592.2    .035       0  4860.6     .07       0
  5112.8    .035       0  5207.4     .07       0  5226.2    .035       0
  5268.8     .07       0  5913.2    .035       0    6111     .07       0
  6475.9    .045       0
Bank Sta=5207.4,5226.2
XS Rating Curve= 0 ,0
Exp/Cntr=0.3,0.1

Type RM Length L Ch R = 1 ,41458   ,1024,1024,1024
BEGIN DESCRIPTION:
Mapping XS f086a4e6
END DESCRIPTION:
XS GIS Cut Line= 6
      1426643.75      6923706.91      1426747.91       6922938.7
      1426626.39      6922257.28        1426596.      6922192.17
      1426496.18      6922127.07      1426070.83      6920798.94
#Sta/Elev= 30
  3511.1 1904.94  4588.2 1903.72  4863.9 1903.42  4893.7 1903.65  4898.7 1905.33
  4927.1 1906.48  4954.5 1904.88  4959.6 1908.46  4980.9 1906.67  4988.4 1904.89
    4994 1909.99  5016.8 1904.49  5022.3 1908.28  5039.7 1904.22  5045.2 1905.96
  5053.5 1904.43  5061.7 1906.06  5082.3 1907.36  5101.8 1905.52  5137.3 1903.44
  5259.4 1901.96  5259.9 1901.46  5278.2 1901.96  5485.2 1905.88  5691.9 1907.54
  5793.6 1910.16  5918.9 1911.42  6089.9 1914.73  6311.9 1918.16  6576.3 1924.09
#Mann= 9 ,-1 , 0
  3511.1     .07       0  4588.2    .035       0  4863.9     .07       0
  5101.8    .035       0  5259.4     .07       0  5278.2    .035       0
  5918.9    .035       0  6089.9     .07       0  6311.9    .045       0
Bank Sta=5259.4,5278.2
XS Rating Curve= 0 ,0
Exp/Cntr=0.3,0.1

Type RM Length L Ch R = 1 ,40434   ,1870,1870,1870
BEGIN DESCRIPTION:
Mapping XS 75a6c874
END DESCRIPTION:
XS GIS Cut Line= 5
      1426019.44      6919465.95      1426669.95      6921612.63
      1427105.22      6921867.95      1427367.84      6922120.26
      1426829.64      6923352.91
#Sta/Elev= 30
  2252.3 1930.62    2290 1930.16  2459.7  1928.6  2563.6  1923.4  2745.5  1919.5
    3153 1914.39  3461.2 1913.83    3571 1917.93  3603.3 1916.49  3675.5 1918.72
  3879.3 1914.92  4074.2 1910.93  4129.3 1909.75  4471.8 1903.77  4515.7  1902.5
  4640.2 1900.28  4708.8 1898.76  4736.1 1899.98  4976.6 1900.72  4987.2 1897.99
  4987.7 1897.49  5006.1 1897.99    5007 1900.05  5013.9 1900.42  5050.7  1900.3
  5346.4 1898.48  5660.2  1901.1  6033.3 1901.21  6505.2 1901.92  6709.2 1903.76
#Mann= 13 ,-1 , 0
  2252.3     .07       0    2290    .035       0    3153    .045       0
  3879.3     .07       0  4074.2    .045       0  4129.3     .07       0
  4471.8    .035       0  4515.7    .045       0  4640.2     .07       0
  4987.2     .07       0  5006.1     .07       0  5050.7    .035       0
  6033.3     .07       0
Bank Sta=4987.2,5006.1
XS Rating Curve= 0 ,0
Exp/Cntr=0.3,0.1

Type RM Length L Ch R = 1 ,38564   ,1893,1893,1893
BEGIN DESCRIPTION:
Mapping XS 562a7848
END DESCRIPTION:
XS GIS Cut Line= 4
      1426942.48      6923383.29      1427766.59      6922177.42
      1427711.62      6921488.93      1426839.21       6919600.9
#Sta/Elev= 30
  2849.6  1902.3  3006.1 1901.07  3221.4 1901.28  3329.1 1899.85  3388.8 1900.48
  3445.6 1899.15  3466.6 1899.97  3630.5 1899.23  4003.3 1898.31  4208.9    1898
    4405 1898.15  4630.6 1896.48  4651.1 1895.13  4651.6 1894.63  4670.3 1895.13
  4710.9 1896.94  4941.6 1897.02  4971.7 1895.85  4998.8 1897.23  5238.5 1898.37
  5390.1 1899.06  5504.1 1898.96  5515.3 1899.23  5652.9 1900.28  5975.9 1907.34
  5976.7 1907.38  6365.6 1914.48  6808.5  1921.6  7005.7 1923.43  7080.7 1923.38
#Mann= 15 ,-1 , 0
  2849.6     .07       0  3630.5    .035       0  4003.3     .07       0
  4208.9    .035       0    4405     .07       0  4651.1     .07       0
  4670.3     .07       0  5238.5    .035       0  5390.1     .07       0
  5504.1    .035       0  5515.3     .07       0  5975.9    .035       0
  5976.7     .07       0  6365.6    .035       0  7005.7     .07       0
Bank Sta=4651.1,4670.3
XS Rating Curve= 0 ,0
Exp/Cntr=0.3,0.1

Type RM Length L Ch R = 1 ,36671   ,1327,1327,1327
BEGIN DESCRIPTION:
Mapping XS 6edfd7d8
END DESCRIPTION:
XS GIS Cut Line= 5
      1427077.08      6923374.15      1428524.96      6922785.62
      1428993.71      6922202.29      1428547.12      6921026.69
      1427223.77       6919692.5
#Sta/Elev= 30
  1408.4 1901.11  2419.5 1896.02    2889 1893.31  3176.4 1891.77  3193.8 1891.86
  3711.7 1891.04  3810.5 1890.96  4130.7 1893.61  4204.5 1892.67  4209.9 1889.66
  4259.1 1893.17  4319.7 1889.26  4344.5 1892.56  4366.1 1889.23  4398.2 1892.23
    4550 1889.16  4705.7 1891.33  4938.1 1890.07  5003.5 1888.39    5004 1887.89
  5022.8 1888.39  5034.3 1893.43  5439.1 1895.37  5614.2 1894.62  6141.8 1905.06
  6244.3 1906.96  6293.9 1908.66  6605.7  1913.2  6748.9 1915.43  6856.4 1917.64
#Mann= 17 ,-1 , 0
  1408.4     .07       0  2419.5    .035       0    2889     .07       0
  3176.4    .035       0  3193.8     .07       0  3711.7    .035       0
  3810.5     .07       0  4705.7     .16       0  4938.1    .035       0
  5003.5    .035       0  5022.8    .035       0  5439.1     .07       0
  6141.8    .035       0  6244.3     .07       0  6293.9    .035       0
  6605.7     .07       0  6748.9    .035       0
Bank Sta=5003.5,5022.8
XS Rating Curve= 0 ,0
Exp/Cntr=0.3,0.1

Type RM Length L Ch R = 1 ,35344   ,17,17,17
BEGIN DESCRIPTION:
Mapping XS 6d6daf8d
END DESCRIPTION:
XS GIS Cut Line= 6
        1428585.       6922940.8      1429501.11      6921524.09
      1429580.98      6921475.48      1429612.23      6921347.01
      1429579.24      6921287.98      1429655.63      6920567.52
#Sta/Elev= 30
  2984.5 1893.14  3123.7 1890.32    3848 1890.59  3934.7 1889.41  4025.7 1889.62
  4049.2 1889.67  4131.4 1889.69  4370.7 1886.69  4371.2 1886.19  4391.5 1886.69
  4619.8 1887.28  4650.1 1890.01  4670.6 1886.71  4695.7 1887.04  4723.5 1891.66
  4738.1 1892.49  4752.7  1889.4  4758.9 1892.55    4772 1892.94  4797.7 1889.87
  4803.1 1892.45    4884  1889.8  4908.2    1892  4932.2 1888.19  4953.9 1889.15
  4969.8 1893.01  5023.8 1886.87  5224.9 1886.86    5245  1889.1    5698 1894.15
#Mann= 8 ,-1 , 0
  2984.5     .07       0    3848    .035       0  3934.7     .16       0
  4025.7     .07       0  4049.2     .16       0  4131.4     .07       0
  4370.7     .07       0  4391.5     .07       0
Bank Sta=4370.7,4391.5
XS Rating Curve= 0 ,0
Exp/Cntr=0.3,0.1

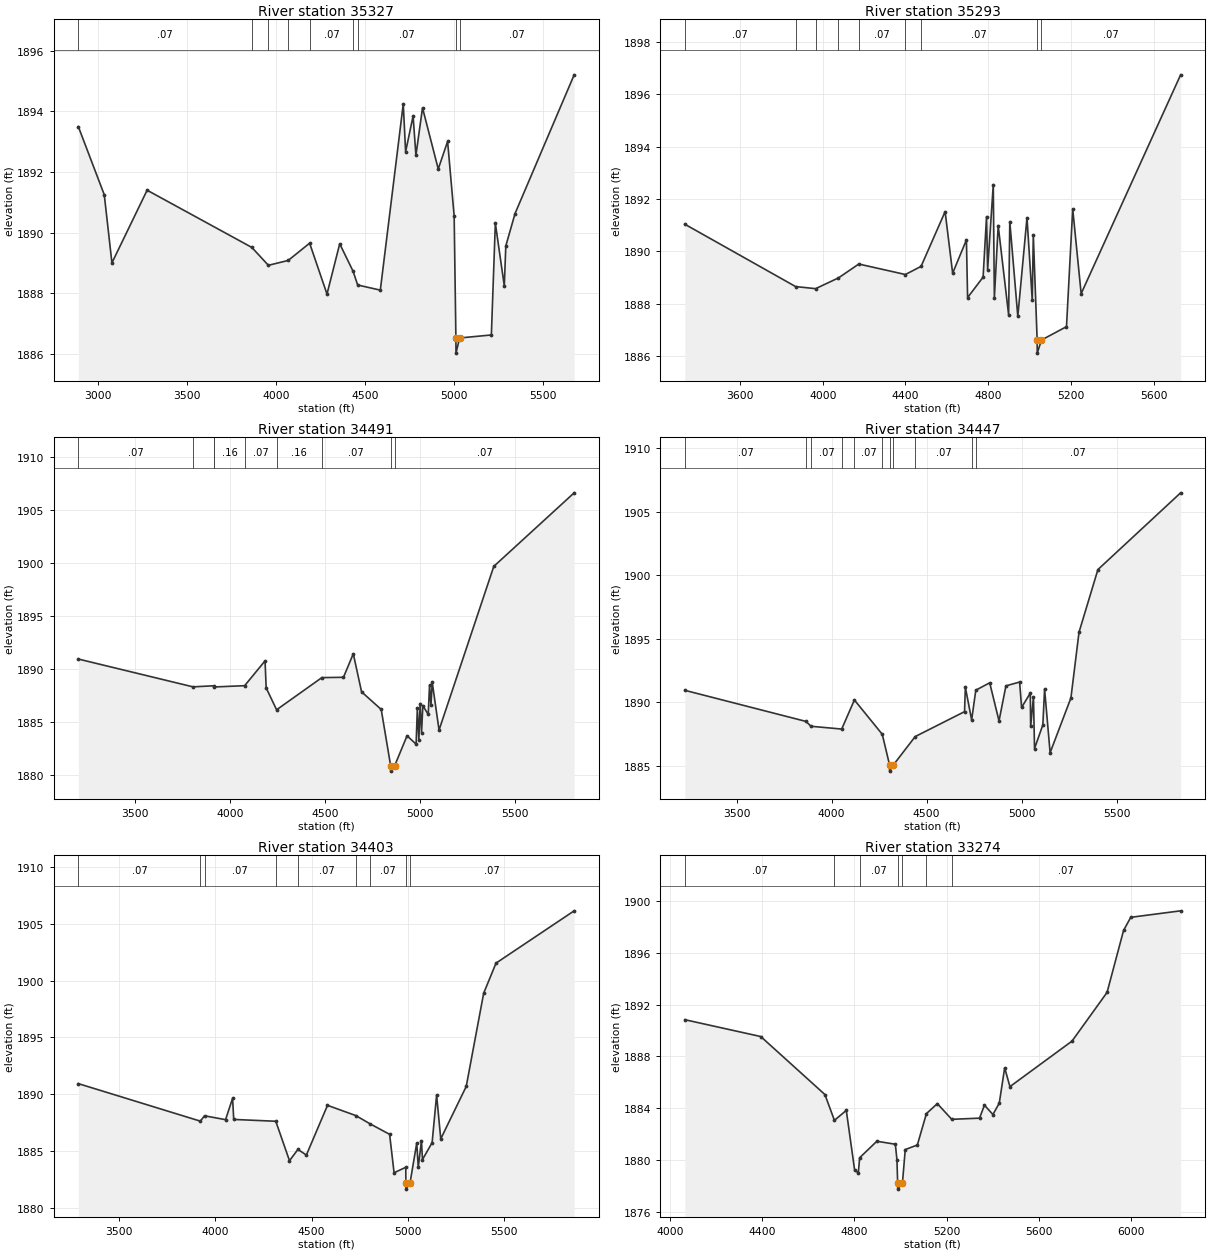
Type RM Length L Ch R = 1 ,35327   ,34,34,34
BEGIN DESCRIPTION:
Mapping XS 85a852d8
END DESCRIPTION:
XS GIS Cut Line= 6
      1428657.94      6923070.96      1429589.66      6921494.58
      1429633.06      6921362.63      1429629.59      6921301.87
      1429589.66      6921284.51      1429676.46      6920577.96
#Sta/Elev= 30
  2887.1  1893.5    3033 1891.25  3076.1    1889  3274.1  1891.4  3863.3 1889.51
  3956.2 1888.92  4067.5 1889.08  4188.3 1889.65    4286 1887.97  4357.6 1889.63
  4433.1 1888.72  4458.5 1888.27    4586  1888.1  4715.1 1894.25  4728.3 1892.67
  4770.4 1893.85  4786.3 1892.55  4823.4 1894.12  4911.9  1892.1  4964.5 1893.01
  5001.4 1890.55  5011.2 1886.52  5011.7 1886.02    5032 1886.52  5210.7 1886.62
  5233.1 1890.31  5283.5 1888.24    5292 1889.56    5344 1890.63  5676.5 1895.21
#Mann= 9 ,-1 , 0
  2887.1     .07       0  3863.3    .035       0  3956.2     .07       0
  4067.5     .16       0  4188.3     .07       0  4433.1     .16       0
  4458.5     .07       0  5011.2     .07       0    5032     .07       0
Bank Sta=5011.2,5032
XS Rating Curve= 0 ,0
Exp/Cntr=0.3,0.1

Type RM Length L Ch R = 1 ,35293   ,802,802,802
BEGIN DESCRIPTION:
Mapping XS cc32707e
END DESCRIPTION:
XS GIS Cut Line= 6
      1428935.38      6922699.32      1429631.32      6921449.44
      1429653.89      6921376.52      1429655.63      6921324.44
      1429617.43      6921227.21      1429732.02      6920503.24
#Sta/Elev= 30
  3333.1 1891.04  3868.9 1888.66  3965.6 1888.58    4076 1888.99  4174.5 1889.52
  4399.7 1889.12  4475.6 1889.43  4591.9 1891.52  4628.3 1889.17  4694.9 1890.44
  4700.6 1888.24  4775.6 1889.02  4792.2 1891.33  4797.4 1889.31  4824.8 1892.55
    4830 1888.22  4848.5 1890.99    4899 1887.58  4904.6 1891.14  4943.4 1887.52
  4987.8 1891.29  5013.3 1888.13  5018.3 1890.63  5036.9 1886.62  5037.4 1886.12
  5057.7 1886.62  5178.8 1887.13  5208.9 1891.62  5249.7 1888.39  5730.7 1896.74
#Mann= 9 ,-1 , 0
  3333.1     .07       0  3868.9    .035       0  3965.6     .07       0
    4076     .16       0  4174.5     .07       0  4399.7     .16       0
  4475.6     .07       0  5036.9     .07       0  5057.7     .07       0
Bank Sta=5036.9,5057.7
XS Rating Curve= 0 ,0
Exp/Cntr=0.3,0.1

Type RM Length L Ch R = 1 ,34491   ,44,44,44
BEGIN DESCRIPTION:
Mapping XS 15f515d9
END DESCRIPTION:
XS GIS Cut Line= 6
      1428961.39      6922748.84      1429758.64      6921499.78
      1429888.85      6921556.21      1430032.08      6921534.51
      1430192.67      6921308.81      1430604.94      6920952.95
#Sta/Elev= 30
  3204.5 1890.92  3806.8  1888.3  3915.4  1888.4  3919.6 1888.29  4078.4 1888.41
  4185.6 1890.75  4191.5  1888.2  4246.3 1886.14  4484.1 1889.17  4597.7  1889.2
  4649.3 1891.42  4692.7 1887.83    4796 1886.17  4845.6 1880.86  4846.1 1880.36
  4866.5 1880.86  4931.7 1883.69  4979.4  1882.9  4985.8 1886.27  4993.8 1883.29
  5000.5 1886.73    5008 1883.99  5014.7 1886.53  5043.1  1885.7  5049.9 1888.47
  5057.3 1886.61  5064.1 1888.72  5099.9 1884.23  5387.5 1899.65  5809.8 1906.58
#Mann= 9 ,-1 , 0
  3204.5     .07       0  3806.8    .035       0  3915.4     .07       0
  3919.6     .16       0  4078.4     .07       0  4246.3     .16       0
  4484.1     .07       0  4845.6     .07       0  4866.5     .07       0
Bank Sta=4845.6,4866.5
XS Rating Curve= 0 ,0
Exp/Cntr=0.3,0.1

Type RM Length L Ch R = 1 ,34447   ,44,44,44
BEGIN DESCRIPTION:
Mapping XS 80085238
END DESCRIPTION:
XS GIS Cut Line= 6
      1428984.81      6922782.73      1429784.68      6921538.85
      1429888.85      6921603.95      1430101.52      6921551.87
      1430192.67       6921382.6      1430635.36       6920983.3
#Sta/Elev= 30
  3227.5 1890.95  3865.6  1888.5  3891.4 1888.12  4053.2  1887.9  4119.9 1890.19
  4266.6 1887.49  4304.8 1885.09  4305.3 1884.59  4325.7 1885.09    4440 1887.31
  4699.6 1889.27  4703.9 1891.19  4736.9 1888.62  4758.9 1890.96    4832 1891.54
    4881 1888.54  4917.4  1891.3  4989.4  1891.6  4999.8  1889.6  5045.5 1890.73
  5047.5 1888.11  5062.3 1890.44  5067.9 1886.37  5111.7 1888.23  5120.8 1891.05
  5149.9 1886.04  5259.4 1890.35    5302 1895.52  5401.4 1900.45  5836.7 1906.49
#Mann= 11 ,-1 , 0
  3227.5     .07       0  3865.6    .035       0  3891.4     .07       0
  4053.2     .16       0  4119.9     .07       0  4266.6     .16       0
  4304.8     .07       0  4325.7     .16       0    4440     .07       0
  4736.9     .16       0  4758.9     .07       0
Bank Sta=4304.8,4325.7
XS Rating Curve= 0 ,0
Exp/Cntr=0.3,0.1

Type RM Length L Ch R = 1 ,34403   ,1129,1129,1129
BEGIN DESCRIPTION:
Mapping XS 4bad6f84
END DESCRIPTION:
XS GIS Cut Line= 6
      1429021.31       6922806.1        1429776.      6921603.95
      1429940.93      6921647.35      1430166.62      6921564.89
      1430231.73      6921399.96      1430674.47      6921048.37
#Sta/Elev= 30
  3289.4 1890.94  3922.5 1887.64  3944.2 1888.11  4053.4 1887.77  4089.9 1889.65
  4095.8 1887.79    4314 1887.63  4385.2 1884.16  4428.8 1885.15  4472.8 1884.66
  4582.4 1889.03  4729.5 1888.13  4800.5 1887.43  4904.7 1886.48  4927.9  1883.1
  4988.6 1883.58  4989.3 1882.16  4989.8 1881.66  5010.2 1882.16  5045.5 1885.71
  5053.5 1883.59  5069.9 1885.92  5075.3 1884.26  5125.3 1885.75  5148.6 1889.93
  5170.1 1886.08  5302.3 1890.69  5392.8 1898.89  5456.9 1901.54  5862.4 1906.14
#Mann= 9 ,-1 , 0
  3289.4     .07       0  3922.5    .035       0  3944.2     .07       0
    4314     .16       0  4428.8     .07       0  4729.5     .16       0
  4800.5     .07       0  4989.3     .07       0  5010.2     .07       0
Bank Sta=4989.3,5010.2
XS Rating Curve= 0 ,0
Exp/Cntr=0.3,0.1

Type RM Length L Ch R = 1 ,33274   ,1631,1631,1631
BEGIN DESCRIPTION:
East China Creek 8.0
END DESCRIPTION:
XS GIS Cut Line= 3
      1429129.29      6922840.93      1429937.98      6922371.43
      1430978.13      6921742.91
#Sta/Elev= 30
  4064.9 1890.83  4394.4 1889.53  4672.6 1885.06  4713.8 1883.07  4765.3 1883.84
  4801.7 1879.21  4817.5 1879.04  4823.3 1880.19  4897.8 1881.46  4978.1 1881.23
    4985 1880.02    4988 1878.27  4988.5 1877.77  5008.9 1878.27    5021 1880.82
  5073.4 1881.17  5112.8 1883.59  5160.1 1884.36  5222.7 1883.15  5343.1 1883.24
  5364.5 1884.24  5401.3 1883.52  5428.8  1884.4  5452.2 1887.12    5475 1885.67
  5744.3 1889.18  5896.2 1892.93  5967.9 1897.71    5999 1898.72  6215.3 1899.22
#Mann= 7 ,-1 , 0
  4064.9     .07       0  4713.8    .035       0  4823.3     .07       0
    4988     .07       0  5008.9     .07       0  5112.8     .16       0
  5222.7     .07       0
Bank Sta=4988,5008.9
XS Rating Curve= 0 ,0
Exp/Cntr=0.3,0.1

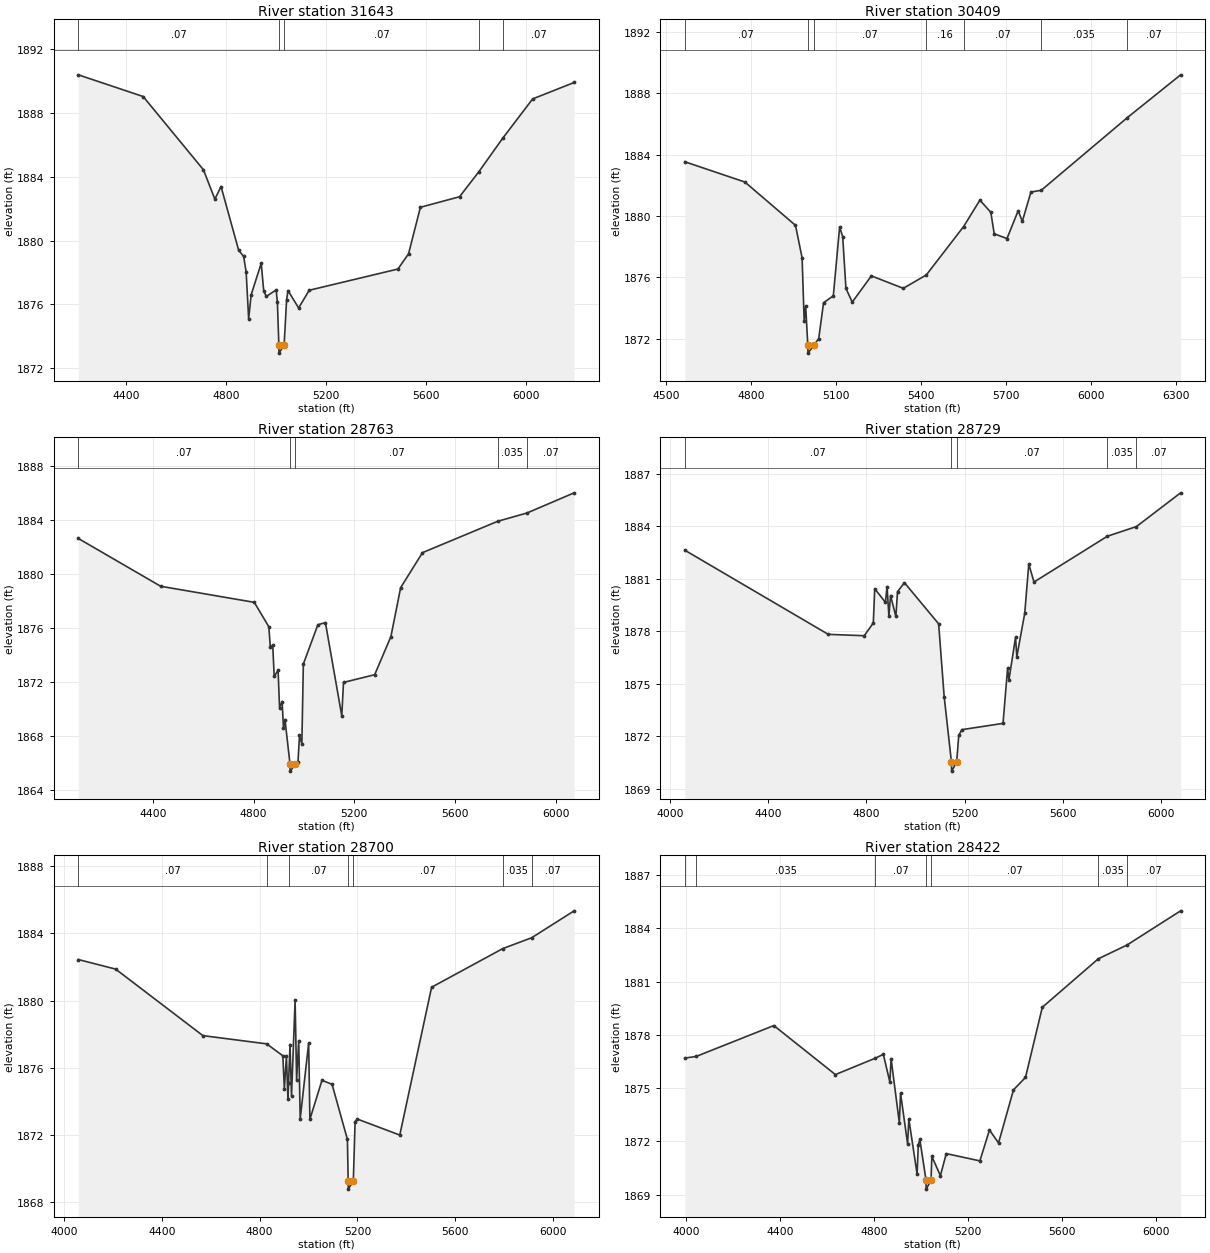
Type RM Length L Ch R = 1 ,31643   ,1234,1234,1234
BEGIN DESCRIPTION:
Mapping XS adc1f002
END DESCRIPTION:
XS GIS Cut Line= 4
      1429276.91       6922858.3      1430053.78      6922936.42
       1430756.9      6922771.49      1431051.01      6922390.87
#Sta/Elev= 30
    4210 1890.39  4469.4 1889.03  4710.6 1884.44  4756.3  1882.6    4781 1883.39
  4851.3 1879.41  4871.4 1879.01  4881.5 1878.04  4891.5  1875.1  4901.6 1876.61
  4941.8 1878.58  4951.7 1876.87  4961.9  1876.5  5001.5 1876.91  5006.6 1876.13
  5012.4 1873.45  5012.9 1872.95  5033.4 1873.45  5043.4 1876.29    5049 1876.87
  5091.5 1875.78  5133.9 1876.89  5488.8 1878.22  5531.2 1879.17  5578.8 1882.09
  5735.4 1882.75  5812.8 1884.32  5907.8 1886.41  6027.9 1888.88    6194 1889.91
#Mann= 5 ,-1 , 0
    4210     .07       0  5012.4     .07       0  5033.4     .07       0
  5812.8    .035       0  5907.8     .07       0
Bank Sta=5012.4,5033.4
XS Rating Curve= 0 ,0
Exp/Cntr=0.3,0.1

Type RM Length L Ch R = 1 ,30409   ,1646,1646,1646
BEGIN DESCRIPTION:
Mapping XS 6fa0ff89
END DESCRIPTION:
XS GIS Cut Line= 3
       1430335.9      6924047.52      1430483.46      6923639.54
      1431060.34      6922455.43
#Sta/Elev= 30
  4565.2 1883.53  4777.4 1882.21  4956.1 1879.39  4979.4 1877.28  4986.8 1873.15
  4992.1 1874.13  4999.6 1871.57  5000.1 1871.07  5020.7 1871.57  5038.2 1872.02
  5055.2 1874.35  5089.7  1874.8    5112 1879.28  5122.8 1878.66  5134.2 1875.29
  5156.5 1874.39  5224.1  1876.1  5336.8 1875.29  5418.1 1876.16  5549.8 1879.31
  5607.3 1881.03  5645.9 1880.24  5657.9 1878.84    5703 1878.53  5742.5 1880.34
  5757.2 1879.65  5787.6 1881.56  5823.8 1881.67  6127.8  1886.4  6316.2 1889.19
#Mann= 7 ,-1 , 0
  4565.2     .07       0  4999.6     .07       0  5020.7     .07       0
  5418.1     .16       0  5549.8     .07       0  5823.8    .035       0
  6127.8     .07       0
Bank Sta=4999.6,5020.7
XS Rating Curve= 0 ,0
Exp/Cntr=0.3,0.1

Type RM Length L Ch R = 1 ,28763   ,34,34,34
BEGIN DESCRIPTION:
Mapping XS 5977a8d1
END DESCRIPTION:
XS GIS Cut Line= 5
      1430418.36      6924043.19      1431104.12      6923617.84
      1431156.21      6923535.37      1431160.55      6923426.87
      1431442.38      6922511.99
#Sta/Elev= 30
  4103.2 1882.63  4430.4 1879.09  4802.5  1877.9  4860.3 1876.09  4866.2 1874.56
  4875.7 1874.74  4881.6 1872.41    4897 1872.87  4902.8 1870.11    4913 1870.55
  4918.5 1868.59  4924.4 1869.22  4944.5  1865.9    4945  1865.4  4965.6  1865.9
  4976.2 1866.11  4982.1 1868.05  4991.5 1867.41  4997.4 1873.33  5055.1 1876.24
  5085.1  1876.4  5150.1  1869.5    5157 1871.97  5280.8 1872.54  5345.3 1875.36
  5384.1 1878.99  5470.9 1881.58  5769.5  1883.9  5886.6 1884.52  6073.6 1886.01
#Mann= 5 ,-1 , 0
  4103.2     .07       0  4944.5     .07       0  4965.6     .07       0
  5769.5    .035       0  5886.6     .07       0
Bank Sta=4944.5,4965.6
XS Rating Curve= 0 ,0
Exp/Cntr=0.3,0.1

Type RM Length L Ch R = 1 ,28729   ,29,29,29
BEGIN DESCRIPTION:
Mapping XS 8e588485
END DESCRIPTION:
XS GIS Cut Line= 5
      1430422.71      6924086.58      1431095.44      6923687.28
      1431177.91      6923596.14      1431182.25      6923474.61
      1431481.74      6922528.41
#Sta/Elev= 30
  4060.5 1882.64  4644.6 1877.83  4791.2 1877.75  4828.2 1878.48    4834 1880.44
  4877.5 1879.66  4884.2 1880.56  4891.7 1878.87  4898.4 1880.05  4920.1 1878.85
  4926.8 1880.27  4955.2 1880.78  5094.3 1878.43  5116.8 1874.27  5146.6 1870.51
  5147.1 1870.01  5167.7 1870.51  5176.1 1872.05  5188.7 1872.38  5356.5 1872.74
  5375.2  1875.9  5380.4 1875.21  5407.5 1877.66  5412.7 1876.55    5445 1879.04
  5461.4 1881.85  5482.6 1880.82  5781.6 1883.44  5899.7 1883.99  6079.8 1885.92
#Mann= 5 ,-1 , 0
  4060.5     .07       0  5146.6     .07       0  5167.7     .07       0
  5781.6    .035       0  5899.7     .07       0
Bank Sta=5146.6,5167.7
XS Rating Curve= 0 ,0
Exp/Cntr=0.3,0.1

Type RM Length L Ch R = 1 ,28700   ,278,278,278
BEGIN DESCRIPTION:
Mapping XS 3cb46631
END DESCRIPTION:
XS GIS Cut Line= 5
      1430444.38      6924116.98      1431125.83      6923704.64
      1431195.27      6923609.16      1431212.63      6923504.99
      1431511.88      6922542.18
#Sta/Elev= 30
  4058.4 1882.44  4211.1 1881.87  4567.9 1877.91  4828.9 1877.42    4895 1876.71
  4901.2 1874.75  4909.7 1876.69  4915.9 1874.12  4918.4 1875.08  4924.4 1877.38
  4930.5 1874.31  4945.2 1880.01  4951.4 1875.28  4959.9 1877.61  4966.1 1872.96
  5000.6 1877.46  5005.7 1872.93  5055.2 1875.25  5096.4 1875.01  5159.2 1871.73
  5162.3 1869.27  5162.8 1868.77  5183.4 1869.27  5190.6 1872.78  5200.1 1872.94
  5373.4 1871.99  5503.6 1880.79  5794.5 1883.09  5913.3 1883.74  6086.8 1885.34
#Mann= 7 ,-1 , 0
  4058.4     .07       0  4828.9    .035       0  4918.4     .07       0
  5162.3     .07       0  5183.4     .07       0  5794.5    .035       0
  5913.3     .07       0
Bank Sta=5162.3,5183.4
XS Rating Curve= 0 ,0
Exp/Cntr=0.3,0.1

Type RM Length L Ch R = 1 ,28422   ,52,52,52
BEGIN DESCRIPTION:
Mapping XS a8cbbb92
END DESCRIPTION:
XS GIS Cut Line= 3
      1431147.52      6924564.05       1431403.6       6923591.8
      1431624.76      6922512.03
#Sta/Elev= 30
  3995.6 1876.69  4043.7 1876.78  4374.1 1878.52  4635.7 1875.76  4805.1 1876.68
  4839.5  1876.9  4867.2 1875.34  4872.4 1876.66  4907.5 1873.05  4912.7 1874.71
  4942.7 1871.85  4947.8 1873.27    4983 1870.16  4988.1  1871.8  4994.6 1872.11
  5021.1 1869.81  5021.6 1869.31  5042.2 1869.81  5045.7 1871.15  5082.1 1870.07
    5107 1871.31  5249.9  1870.9  5290.7 1872.64  5329.2 1871.91  5392.8  1874.9
  5443.8  1875.6  5515.3 1879.55  5753.4 1882.28  5874.7 1883.05  6103.2 1884.98
#Mann= 7 ,-1 , 0
  3995.6     .07       0  4043.7    .035       0  4805.1     .07       0
  5021.1     .07       0  5042.2     .07       0  5753.4    .035       0
  5874.7     .07       0
Bank Sta=5021.1,5042.2
XS Rating Curve= 0 ,0
Exp/Cntr=0.3,0.1

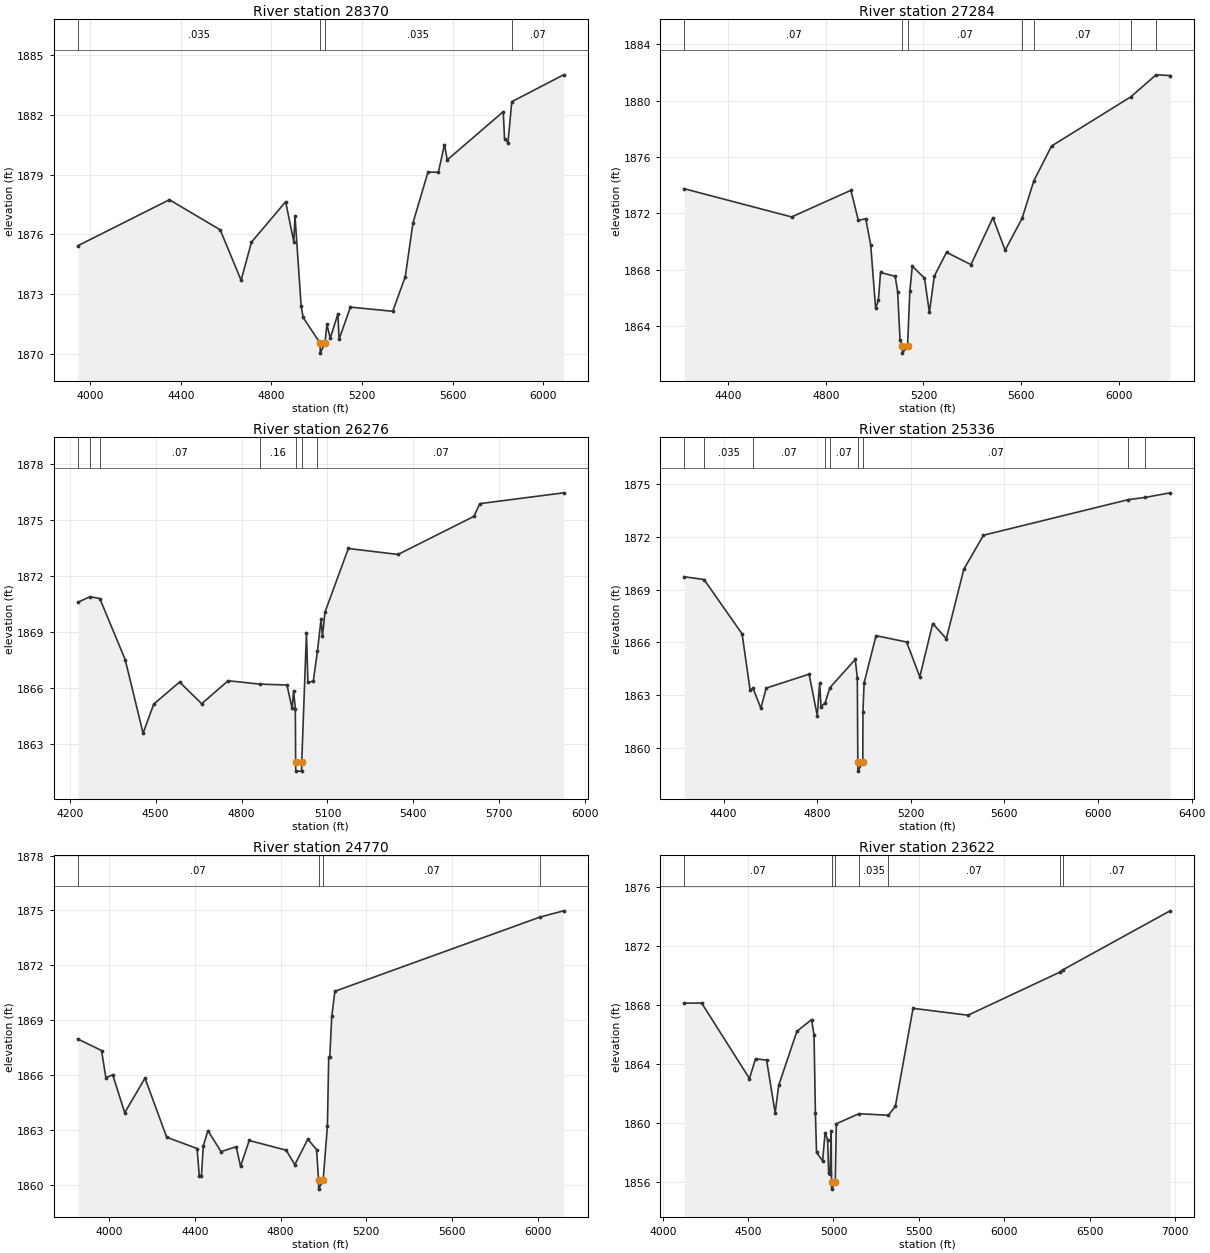
Type RM Length L Ch R = 1 ,28370   ,1086,1086,1086
BEGIN DESCRIPTION:
Mapping XS d9a5bef8
END DESCRIPTION:
XS GIS Cut Line= 4
      1431238.68      6924624.74      1431416.62      6923739.37
      1431451.35      6923600.48      1431750.83      6922541.45
#Sta/Elev= 30
  3944.1 1875.43  4348.8 1877.74  4573.2 1876.23  4665.7  1873.7  4711.5 1875.61
  4862.6 1877.64  4898.6 1875.63  4903.8 1876.94    4931 1872.41  4939.9 1871.83
  5015.1 1870.54  5015.6 1870.04  5036.3 1870.54  5044.9 1871.48  5059.7 1870.79
  5093.6 1872.01  5098.8 1870.74  5148.8 1872.35  5335.9 1872.14  5391.3 1873.88
  5425.3 1876.58  5491.7 1879.13  5537.6 1879.12  5564.5 1880.51  5576.7 1879.74
  5824.3 1882.16    5830 1880.81  5845.1 1880.61    5862 1882.66  6090.9 1884.01
#Mann= 4 ,-1 , 0
  3944.1    .035       0  5015.1    .035       0  5036.3    .035       0
    5862     .07       0
Bank Sta=5015.1,5036.3
XS Rating Curve= 0 ,0
Exp/Cntr=0.3,0.1

Type RM Length L Ch R = 1 ,27284   ,1008,1008,1008
BEGIN DESCRIPTION:
Mapping XS c7f2641e
END DESCRIPTION:
XS GIS Cut Line= 3
      1432041.62      6924741.93       1431920.1      6923960.72
      1431937.46      6922762.85
#Sta/Elev= 30
    4221 1873.75  4660.2 1871.75    4903 1873.64  4933.4 1871.51  4963.8 1871.62
    4984 1869.78  5004.2 1865.26  5015.5 1865.84  5024.3 1867.81  5084.3 1867.54
  5094.3 1866.46  5104.3 1863.01  5113.7 1862.59  5114.2 1862.09  5134.9 1862.59
  5144.3 1866.48  5154.3 1868.26  5204.3 1867.41  5224.4 1864.98  5244.4 1867.55
  5294.4 1869.24  5394.4 1868.37  5484.4  1871.7  5534.4 1869.39  5603.9 1871.65
  5651.9 1874.31  5724.4 1876.78    6049 1880.27  6152.3 1881.83  6209.6 1881.78
#Mann= 7 ,-1 , 0
    4221     .07       0  5113.7     .07       0  5134.9     .07       0
  5603.9     .16       0  5651.9     .07       0    6049    .035       0
  6152.3     .07       0
Bank Sta=5113.7,5134.9
XS Rating Curve= 0 ,0
Exp/Cntr=0.3,0.1

Type RM Length L Ch R = 1 ,26276   ,940,940,940
BEGIN DESCRIPTION:
Mapping XS ee6acf6f
END DESCRIPTION:
XS GIS Cut Line= 3
      1432459.15      6924439.06      1432632.77      6923695.96
      1432816.43      6922781.13
#Sta/Elev= 30
  4228.3 1870.61    4271 1870.91    4305 1870.81  4393.7 1867.54  4456.1  1863.6
  4493.5 1865.16  4583.7 1866.34  4660.7 1865.18  4753.1 1866.41  4862.7 1866.23
  4958.5 1866.18  4976.6 1864.93  4981.7 1865.87  4987.8  1864.9  4988.9 1862.07
  4989.4 1861.57  5009.7 1861.57  5010.2 1862.07  5026.6 1868.96  5031.7 1866.32
  5050.5 1866.39  5065.1 1868.01  5077.5 1869.69  5082.6 1868.79  5091.3 1870.08
  5172.9 1873.49  5346.3 1873.17  5611.5 1875.21  5631.9 1875.89  5924.5 1876.47
#Mann= 7 ,-1 , 0
  4228.3     .07       0    4271    .035       0    4305     .07       0
  4862.7     .16       0  4988.9     .07       0  5010.2     .16       0
  5065.1     .07       0
Bank Sta=4988.9,5010.2
XS Rating Curve= 0 ,0
Exp/Cntr=0.3,0.1

Type RM Length L Ch R = 1 ,25336   ,566,566,566
BEGIN DESCRIPTION:
Mapping XS 242a2a3a
END DESCRIPTION:
XS GIS Cut Line= 3
      1432545.98      6924723.72      1432917.49      6924057.08
      1433483.45      6922873.07
#Sta/Elev= 30
  4232.2 1869.73  4316.5 1869.57  4479.2 1866.48  4513.5 1863.27  4525.5  1863.4
  4559.3 1862.26  4582.2  1863.4  4765.4 1864.19  4800.3 1861.84  4810.5 1863.68
  4816.3 1862.34    4834 1862.56  4853.9 1863.42  4962.6 1865.03  4971.4 1863.99
  4973.6 1859.18  4974.1 1858.68    4995 1859.18  4995.4 1862.04  5000.5  1863.7
  5051.4 1866.38    5182 1866.02  5238.4 1864.04  5293.6 1867.07  5351.8 1866.21
  5426.6 1870.16  5510.5 1872.09  6128.4 1874.11  6201.5 1874.24  6307.7  1874.5
#Mann= 9 ,-1 , 0
  4232.2     .07       0  4316.5    .035       0  4525.5     .07       0
    4834    .035       0  4853.9     .07       0  4973.6     .07       0
    4995     .07       0  6128.4    .035       0  6201.5     .07       0
Bank Sta=4973.6,4995
XS Rating Curve= 0 ,0
Exp/Cntr=0.3,0.1

Type RM Length L Ch R = 1 ,24770   ,1148,1148,1148
BEGIN DESCRIPTION:
Mapping XS 3bfd847d
END DESCRIPTION:
XS GIS Cut Line= 3
      1433164.02      6924977.19      1433354.99      6923820.96
      1433556.39      6922744.53
#Sta/Elev= 30
  3853.4 1867.97  3964.1 1867.34  3984.3 1865.85  4016.3 1866.01  4072.3 1863.94
  4166.8 1865.83  4268.1  1862.6    4410 1861.98  4420.2 1860.49  4430.3 1860.49
  4438.9 1862.12  4460.7 1862.96  4521.5 1861.81  4592.5 1862.08  4612.7 1861.01
  4653.3 1862.42  4825.6 1861.89  4866.1  1861.1  4926.9 1862.49  4967.5 1861.92
    4977 1860.26  4977.5 1859.76  4998.4 1860.26  5018.2 1863.22  5024.3 1866.99
  5029.3 1866.99  5038.5 1869.21  5053.1 1870.58  6010.6 1874.64  6120.4 1874.98
#Mann= 4 ,-1 , 0
  3853.4     .07       0    4977     .07       0  4998.4     .07       0
  6010.6    .035       0
Bank Sta=4977,4998.4
XS Rating Curve= 0 ,0
Exp/Cntr=0.3,0.1

Type RM Length L Ch R = 1 ,23622   ,977,977,977
BEGIN DESCRIPTION:
Mapping XS 2e9058ad
END DESCRIPTION:
XS GIS Cut Line= 4
      1433152.28      6925107.88      1433668.33       6924402.5
      1434037.72      6923717.23      1433876.25      6922534.89
#Sta/Elev= 30
    4126 1868.14  4227.5 1868.15  4507.7 1863.02  4543.2 1864.36  4608.1 1864.27
  4658.3 1860.69  4679.1 1862.56  4785.7 1866.23  4871.4 1867.02  4886.1 1865.97
  4894.1 1860.65  4900.7    1858  4936.3 1857.43  4950.9 1859.34  4965.6 1858.86
  4971.8 1856.58  4980.2 1856.55  4986.4 1859.44  4988.9 1856.01  4989.4 1855.51
  5010.4 1856.01  5016.5 1859.95  5149.1 1860.63  5321.1 1860.53  5362.4 1861.13
  5466.2 1867.79  5787.8 1867.32  6325.1 1870.24  6343.1  1870.4  6971.8 1874.41
#Mann= 7 ,-1 , 0
    4126     .07       0  4988.9     .07       0  5010.4     .07       0
  5149.1    .035       0  5321.1     .07       0  6325.1    .035       0
  6343.1     .07       0
Bank Sta=4988.9,5010.4
XS Rating Curve= 0 ,0
Exp/Cntr=0.3,0.1

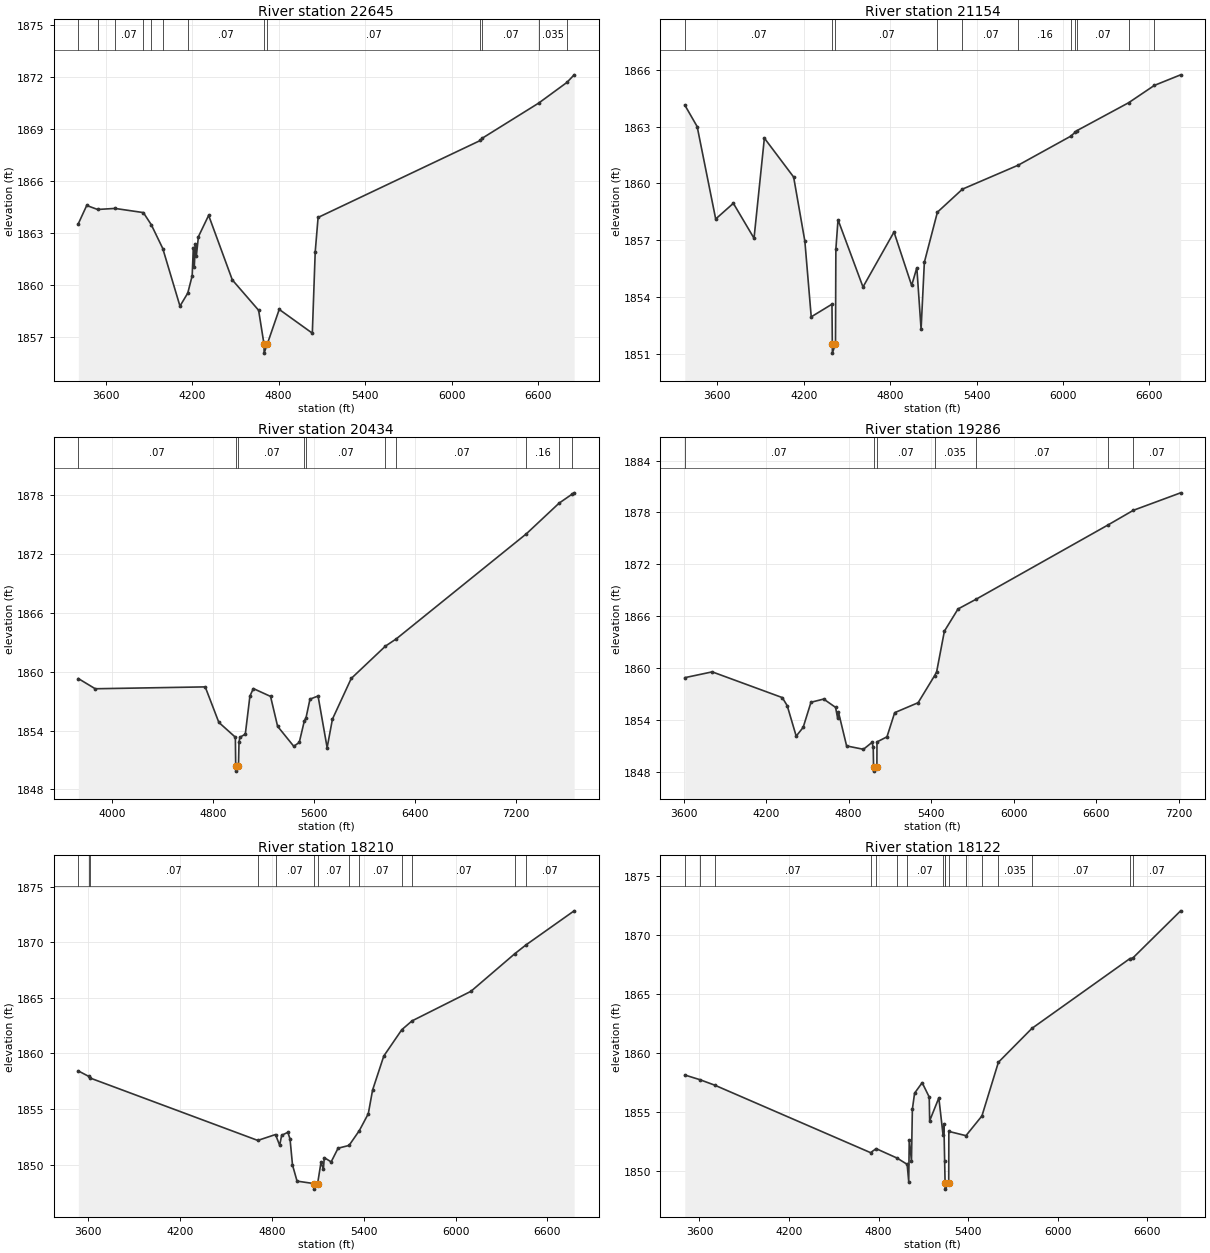
Type RM Length L Ch R = 1 ,22645   ,1491,1491,1491
BEGIN DESCRIPTION:
Mapping XS d65b8ea8
END DESCRIPTION:
XS GIS Cut Line= 4
      1433542.94      6925227.63      1434173.13      6924456.82
      1434355.43       6923883.9      1434399.76      6922042.59
#Sta/Elev= 30
  3410.5 1863.53  3468.6 1864.58    3544 1864.35  3664.7 1864.41  3861.5 1864.17
  3916.5 1863.47  3996.1  1862.1  4115.4 1858.78  4169.4 1859.53  4200.1 1860.53
    4208 1862.15  4214.5 1861.02  4222.4 1862.37  4228.8 1861.65  4243.2 1862.78
  4314.2 1864.01  4478.4 1860.29  4660.8 1858.54  4698.5 1856.57    4699 1856.07
    4720 1856.57  4803.7 1858.59  5033.3 1857.22  5053.3  1861.9  5073.3 1863.89
  6199.4 1868.33  6210.6 1868.45    6603 1870.48  6798.7 1871.67  6849.2 1872.11
#Mann= 13 ,-1 , 0
  3410.5     .07       0    3544    .035       0  3664.7     .07       0
  3861.5    .035       0  3916.5     .07       0  3996.1    .035       0
  4169.4     .07       0  4698.5     .07       0    4720     .07       0
  6199.4    .035       0  6210.6     .07       0    6603    .035       0
  6798.7     .07       0
Bank Sta=4698.5,4720
XS Rating Curve= 0 ,0
Exp/Cntr=0.3,0.1

Type RM Length L Ch R = 1 ,21154   ,720,720,720
BEGIN DESCRIPTION:
Mapping XS 23656ff1
END DESCRIPTION:
XS GIS Cut Line= 4
      1433850.23      6925092.22      1435199.18      6924170.36
      1435361.24      6924077.46      1435163.66       6922467.6
#Sta/Elev= 30
  3374.5 1864.15  3460.4 1863.01    3589 1858.12  3711.6 1858.95  3855.2  1857.1
    3927  1862.4  4130.2 1860.34    4208 1856.95  4252.3 1852.94  4396.4 1853.61
  4398.8 1851.52  4399.3 1851.02  4420.8 1851.52  4423.4 1856.52  4438.3 1858.08
  4611.7 1854.52  4827.1 1857.43  4949.6  1854.6  4985.5 1855.54  5015.1 1852.29
  5037.8 1855.83  5128.4 1858.48  5302.4  1859.7    5690 1860.97  6053.7  1862.5
  6083.6  1862.7  6095.7 1862.79  6455.4 1864.27  6634.6 1865.19  6817.1 1865.75
#Mann= 11 ,-1 , 0
  3374.5     .07       0  4398.8     .07       0  4420.8     .07       0
  5128.4    .035       0  5302.4     .07       0    5690     .16       0
  6053.7     .07       0  6083.6     .16       0  6095.7     .07       0
  6455.4     .16       0  6634.6     .07       0
Bank Sta=4398.8,4420.8
XS Rating Curve= 0 ,0
Exp/Cntr=0.3,0.1

Type RM Length L Ch R = 1 ,20434   ,1148,1148,1148
BEGIN DESCRIPTION:
Mapping XS d849d3cb
END DESCRIPTION:
XS GIS Cut Line= 3
      1434553.37      6925790.11      1435261.68      6924706.82
      1437334.63      6923076.58
#Sta/Elev= 30
  3732.7 1859.31  3866.6 1858.27  4738.8 1858.46  4846.8 1854.84  4977.8 1853.33
  4980.5 1850.37    4981 1849.87  5002.6 1850.37  5006.7 1852.82  5013.6 1853.32
  5056.7 1853.64  5093.2 1857.52  5120.4 1858.29  5256.8 1857.49  5312.8 1854.44
  5441.1  1852.4  5484.5  1852.8  5524.5 1854.98  5538.1 1855.31  5569.5 1857.21
  5633.6 1857.53  5705.5 1852.26  5747.5 1855.17  5896.6 1859.32  6168.1 1862.62
  6254.1 1863.36  7285.1 1874.07    7545  1877.2  7650.7 1878.14  7664.2 1878.25
#Mann= 10 ,-1 , 0
  3732.7     .07       0  4980.5     .07       0  5002.6     .07       0
  5524.5    .035       0  5538.1     .07       0  6168.1    .035       0
  6254.1     .07       0  7285.1     .16       0    7545     .07       0
  7650.7     .16       0
Bank Sta=4980.5,5002.6
XS Rating Curve= 0 ,0
Exp/Cntr=0.3,0.1

Type RM Length L Ch R = 1 ,19286   ,1076,1076,1076
BEGIN DESCRIPTION:
Mapping XS a86bde0d
END DESCRIPTION:
XS GIS Cut Line= 3
       1434948.3      6925718.11      1436135.81      6924891.71
      1437746.89      6923454.24
#Sta/Elev= 30
    3609 1858.93  3808.3  1859.6    4318 1856.63  4353.7  1855.7  4419.2 1852.18
  4469.8 1853.19  4526.6 1856.09  4619.1 1856.46  4705.5  1855.5  4720.3 1854.27
  4726.4 1854.96  4785.8 1851.05    4908 1850.66  4970.8 1851.46  4979.5 1850.87
  4981.7 1848.64  4982.2 1848.14    5006 1848.64  5006.6 1851.51  5079.3  1852.1
  5135.4 1854.89  5305.9 1856.04  5425.2 1859.15  5440.5  1859.6  5496.9  1864.3
    5596 1866.86  5725.7 1867.97  6686.8 1876.56  6870.8 1878.25  7214.9 1880.27
#Mann= 7 ,-1 , 0
    3609     .07       0  4981.7     .07       0    5006     .07       0
  5425.2    .035       0  5725.7     .07       0  6686.8     .16       0
  6870.8     .07       0
Bank Sta=4981.7,5006
XS Rating Curve= 0 ,0
Exp/Cntr=0.3,0.1

Type RM Length L Ch R = 1 ,18210   ,88,88,88
BEGIN DESCRIPTION:
Mapping XS c91c93e3
END DESCRIPTION:
XS GIS Cut Line= 4
      1435212.22      6925947.26      1436628.86      6925725.04
      1436753.86      6925634.77       1437476.1      6924148.63
#Sta/Elev= 30
  3534.1 1858.43  3600.9 1857.95  3611.7 1857.79  4706.8 1852.18  4822.8 1852.71
    4850 1851.74  4862.9 1852.64  4903.4 1852.91  4917.7 1852.31  4933.8 1849.97
  4963.6 1848.52  5073.7  1848.3  5074.2  1847.8    5098  1848.3  5119.9  1850.2
  5135.8 1849.61  5141.4 1850.63  5186.5 1850.25  5231.6 1851.48  5303.4 1851.73
  5370.9 1853.07  5429.1 1854.58  5457.2 1856.71  5530.4 1859.77  5648.2 1862.14
  5714.9 1862.93  6099.9 1865.59  6387.3 1868.98  6459.3 1869.76  6774.6 1872.83
#Mann= 13 ,-1 , 0
  3534.1     .07       0  3600.9    .035       0  3611.7     .07       0
  4706.8    .035       0  4822.8     .07       0  5073.7     .07       0
    5098     .07       0  5303.4    .035       0  5370.9     .07       0
  5648.2    .035       0  5714.9     .07       0  6387.3    .035       0
  6459.3     .07       0
Bank Sta=5073.7,5098
XS Rating Curve= 0 ,0
Exp/Cntr=0.3,0.1

Type RM Length L Ch R = 1 ,18122   ,49,49,49
BEGIN DESCRIPTION:
Mapping XS feadbb48
END DESCRIPTION:
XS GIS Cut Line= 5
      1435177.48      6926044.49      1436656.64      6925794.49
      1436767.75       6925718.1      1436823.31      6925606.99
      1437538.61      6924218.06
#Sta/Elev= 30
  3501.9 1858.12  3601.4 1857.73  3702.3 1857.26  4746.4 1851.54  4783.5 1851.88
  4924.1 1851.08  4991.5 1850.55    5002 1849.08  5005.4 1852.63  5020.3 1850.85
  5026.4 1855.22  5041.2 1856.58    5092 1857.47  5139.4 1856.25  5142.2 1854.24
  5203.7 1856.18  5231.7 1853.07  5237.6 1853.96  5242.6 1850.83  5245.6 1848.95
  5246.1 1848.45  5269.9 1848.95  5270.7 1853.34  5385.4 1852.98  5492.3 1854.65
  5602.7  1859.2  5827.3 1862.07  6483.4 1867.98  6503.8 1868.04  6823.4 1872.03
#Mann= 17 ,-1 , 0
  3501.9     .07       0  3601.4    .035       0  3702.3     .07       0
  4746.4    .035       0  4783.5     .07       0  4924.1    .035       0
  4991.5     .07       0  5231.7     .16       0  5242.6     .07       0
  5245.6     .07       0  5269.9     .07       0  5385.4    .035       0
  5492.3     .07       0  5602.7    .035       0  5827.3     .07       0
  6483.4    .035       0  6503.8     .07       0
Bank Sta=5245.6,5269.9
XS Rating Curve= 0 ,0
Exp/Cntr=0.3,0.1