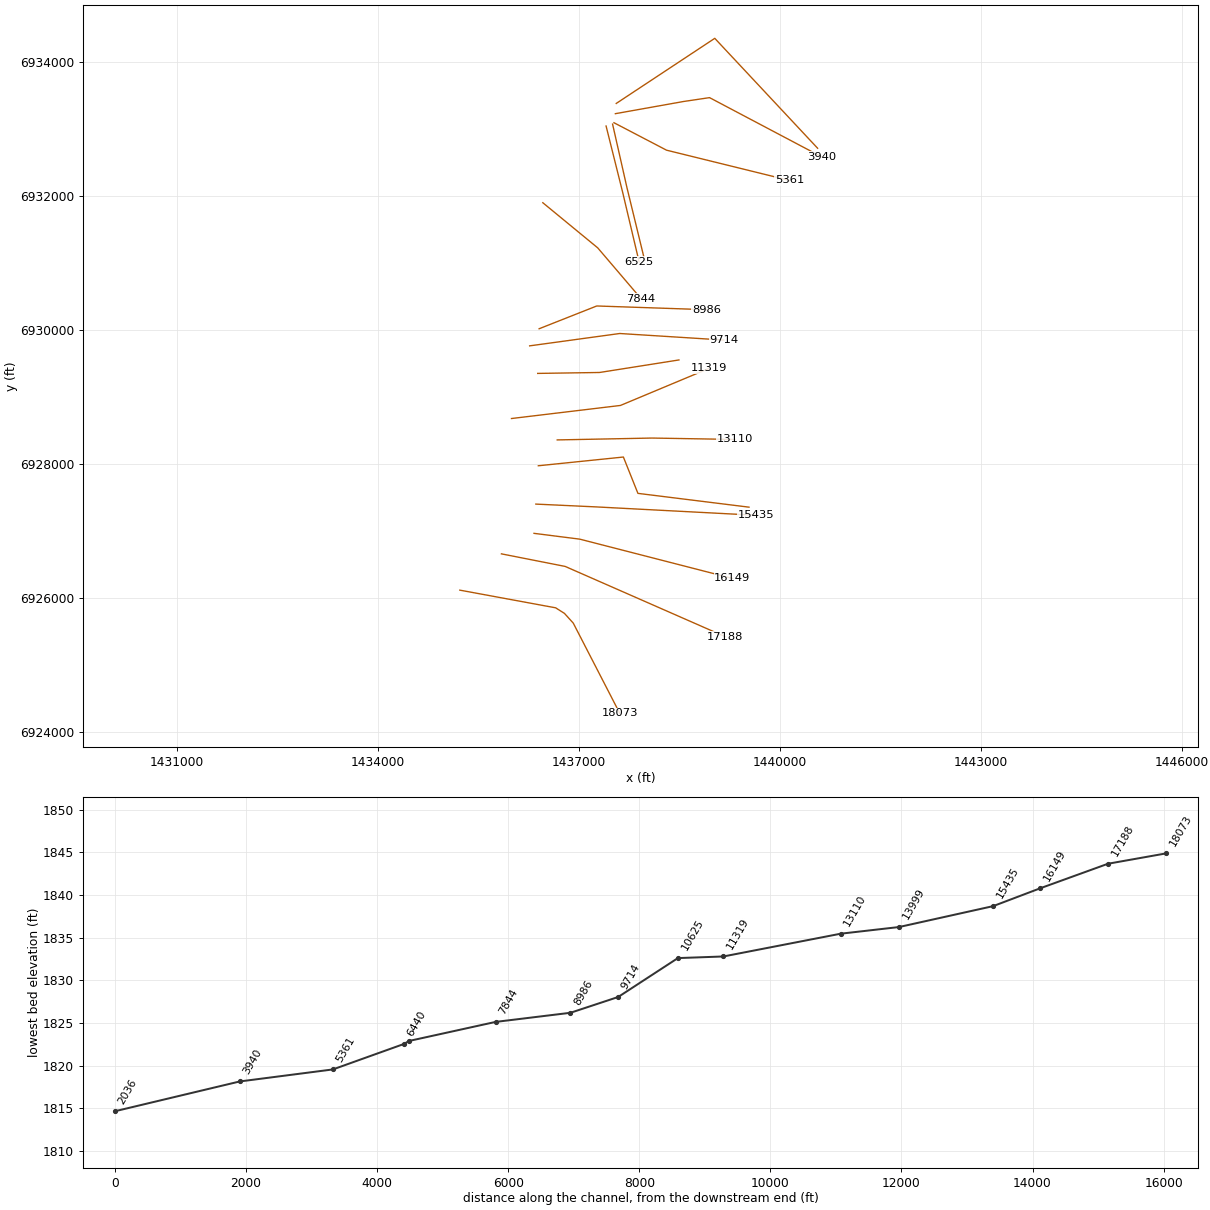
HEC-RAS study East China Creek.prj: East China Creek Base Level Engineering

--- East China Creek.g01 (geometry) --- (continued)

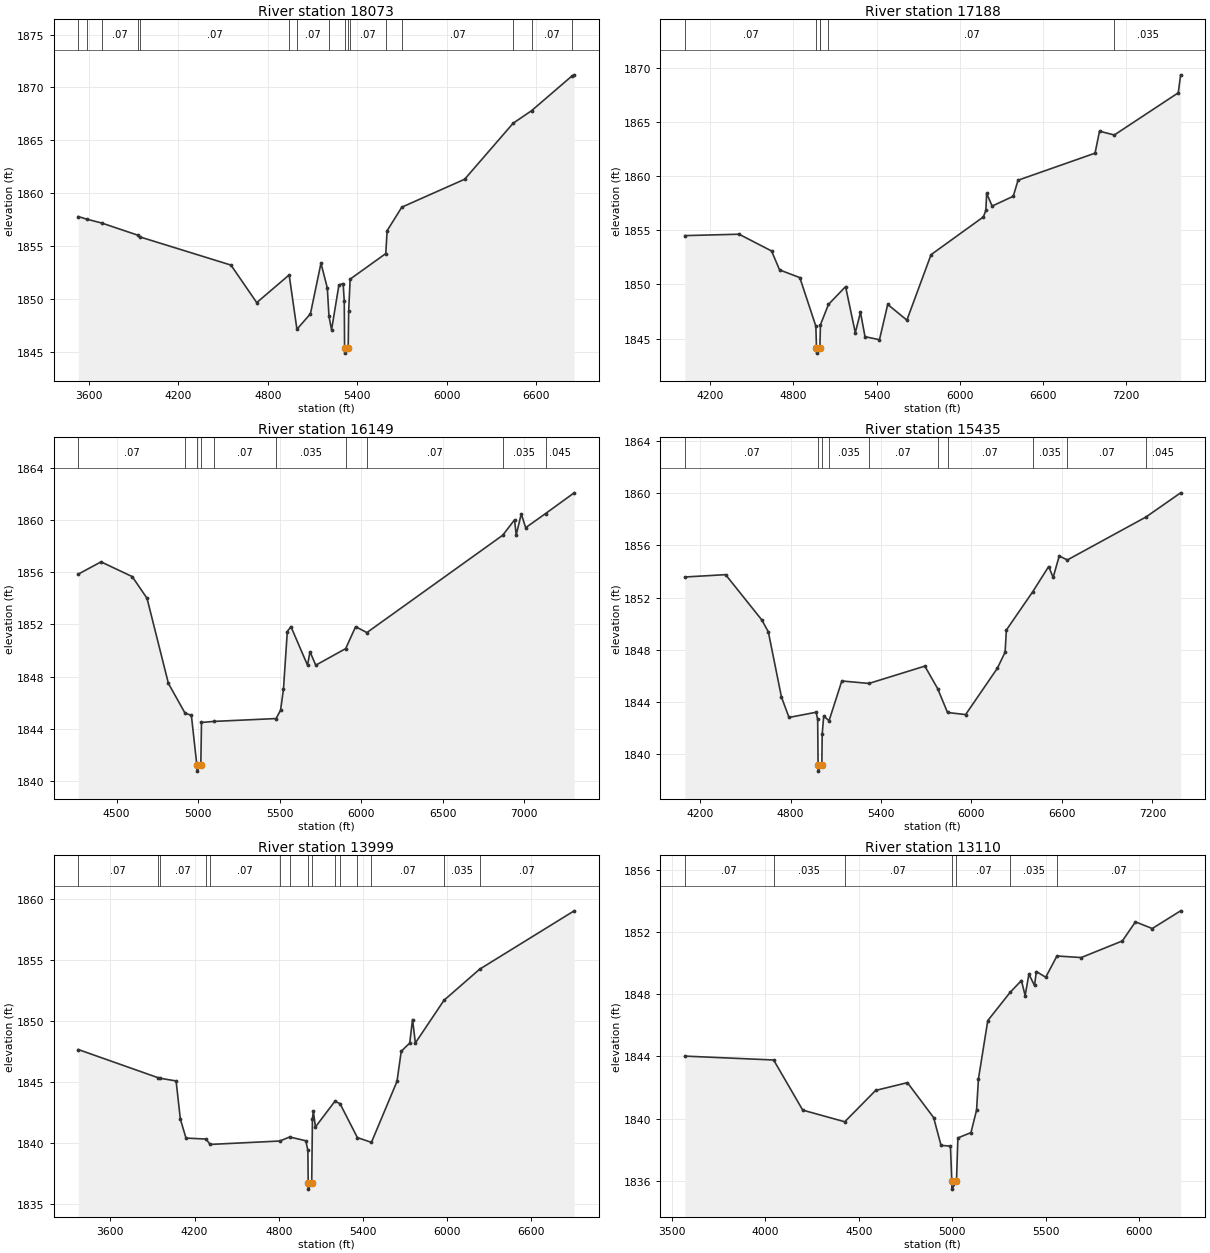
Type RM Length L Ch R = 1 ,18073   ,885,885,885
BEGIN DESCRIPTION:
Mapping XS 4900fbe0
END DESCRIPTION:
XS GIS Cut Line= 5
      1435219.19      6926113.92       1436649.7      6925850.04
      1436781.64      6925766.71      1436913.59      6925620.88
      1437608.01      6924273.69
#Sta/Elev= 30
  3530.8 1857.78    3586 1857.54  3687.2 1857.17  3929.2 1856.02  3942.4 1855.86
  4553.6 1853.19  4726.5 1849.64  4943.8 1852.26  4995.8 1847.12  5086.3 1848.58
    5157 1853.37  5199.6 1851.02  5210.7 1848.33    5228 1847.07  5277.3 1851.31
  5305.7 1851.44  5313.1 1849.75  5315.2 1845.36  5315.7 1844.86  5339.5 1845.36
  5342.6 1848.84  5352.5 1851.86  5591.3 1854.28  5600.2 1856.44  5698.8 1858.67
  6119.7 1861.31  6444.8 1866.61  6568.6  1867.8  6836.4 1871.05  6853.8 1871.19
#Mann= 16 ,-1 , 0
  3530.8     .07       0    3586    .035       0  3687.2     .07       0
  3929.2    .035       0  3942.4     .07       0  4943.8    .035       0
  4995.8     .07       0  5210.7     .16       0  5315.2     .07       0
  5339.5     .16       0  5352.5     .07       0  5591.3    .035       0
  5698.8     .07       0  6444.8    .035       0  6568.6     .07       0
  6836.4    .035       0
Bank Sta=5315.2,5339.5
XS Rating Curve= 0 ,0
Exp/Cntr=0.3,0.1

Type RM Length L Ch R = 1 ,17188   ,1039,1039,1039
BEGIN DESCRIPTION:
Mapping XS ed6fc7a8
END DESCRIPTION:
XS GIS Cut Line= 3
      1435840.65       6926655.6      1436792.06       6926468.1
      1439180.47       6925419.7
#Sta/Elev= 30
  4016.2 1854.51  4407.9 1854.64  4642.4 1853.09  4700.2 1851.34  4846.2 1850.63
    4962 1846.14  4966.5 1844.15    4967 1843.65  4990.9 1844.15  4995.1 1846.27
  5052.9 1848.15  5176.5  1849.8  5246.6 1845.54    5284 1847.42  5316.7 1845.17
    5421 1844.89  5480.6 1848.15  5618.8  1846.7  5793.3 1852.75    6171 1856.24
  6188.9 1856.85  6194.4 1858.42  6234.1 1857.24  6386.7 1858.15    6421 1859.63
  6976.7 1862.13  7008.9 1864.16  7115.8 1863.81  7577.4 1867.71  7594.3 1869.37
#Mann= 6 ,-1 , 0
  4016.2     .07       0  4966.5    .035       0  4990.9     .07       0
  4995.1    .035       0  5052.9     .07       0  7115.8    .035       0
Bank Sta=4966.5,4990.9
XS Rating Curve= 0 ,0
Exp/Cntr=0.3,0.1

Type RM Length L Ch R = 1 ,16149   ,714,714,714
BEGIN DESCRIPTION:
Mapping XS 84a85d64
END DESCRIPTION:
XS GIS Cut Line= 3
      1436327.03      6926962.03      1437010.66      6926875.22
      1439289.31      6926289.28
#Sta/Elev= 30
  4265.4 1855.86  4404.5  1856.8    4596 1855.67  4686.7 1854.01  4818.1 1847.48
  4919.4 1845.22    4959 1845.03  4992.2 1841.26  4992.7 1840.76  5016.9 1841.26
    5021 1844.49  5096.3 1844.57    5479 1844.79  5506.2 1845.44  5523.7 1847.02
  5547.5 1851.46  5569.6 1851.84  5671.5 1848.88  5686.6 1849.91  5722.1 1848.88
  5905.6 1850.15  5966.5 1851.83  6035.8 1851.38  6869.1 1858.84  6941.5 1860.02
  6951.8 1858.87  6982.8 1860.47  7009.9 1859.42  7131.7  1860.5  7307.3 1862.09
#Mann= 10 ,-1 , 0
  4265.4     .07       0  4919.4     .16       0  4992.2     .07       0
  5016.9     .16       0  5096.3     .07       0    5479    .035       0
  5905.6     .16       0  6035.8     .07       0  6869.1    .035       0
  7131.7    .045       0
Bank Sta=4992.2,5016.9
XS Rating Curve= 0 ,0
Exp/Cntr=0.3,0.1

Type RM Length L Ch R = 1 ,15435   ,1436,1436,1436
BEGIN DESCRIPTION:
Mapping XS 9b3dee22
END DESCRIPTION:
XS GIS Cut Line= 3
      1436354.56      6927398.66      1437250.39      6927356.99
      1439639.33      6927231.99
#Sta/Elev= 30
  4098.5 1853.58  4369.2 1853.76  4609.5 1850.28  4652.6 1849.37  4739.6 1844.37
  4789.7  1842.8  4969.9  1843.2  4979.9 1842.65  4982.7 1839.18  4983.2 1838.68
  5007.5 1839.18  5009.9 1841.52  5019.9 1842.91  5055.4 1842.55  5140.1  1845.6
  5319.8 1845.41  5690.9 1846.74  5775.9 1845.01  5841.3 1843.18  5961.2 1843.02
  6171.5 1846.57  6223.2 1847.81  6231.6 1849.51  6406.5 1852.45    6512 1854.38
    6542 1853.55  6582.1 1855.19  6636.4 1854.89    7157 1858.18  7387.5 1860.04
#Mann= 10 ,-1 , 0
  4098.5     .07       0  4982.7     .07       0  5007.5     .07       0
  5055.4    .035       0  5319.8     .07       0  5775.9    .035       0
  5841.3     .07       0  6406.5    .035       0  6636.4     .07       0
    7157    .045       0
Bank Sta=4982.7,5007.5
XS Rating Curve= 0 ,0
Exp/Cntr=0.3,0.1

Type RM Length L Ch R = 1 ,13999   ,889,889,889
BEGIN DESCRIPTION:
Mapping XS 137b5433
END DESCRIPTION:
XS GIS Cut Line= 4
      1436392.15      6927971.14      1437661.71      6928101.35
      1437878.72      6927558.81      1439537.43      6927352.83
#Sta/Elev= 30
  3372.3 1847.66  3936.4 1845.37  3954.3 1845.31  4068.8 1845.09  4098.9 1841.97
  4139.2 1840.41  4281.8 1840.33  4311.2 1839.89  4807.4 1840.17  4877.7  1840.5
  4992.7 1840.19  5007.5  1839.4  5009.8 1836.73  5010.3 1836.23  5034.7 1836.73
  5039.9    1842  5046.5  1842.6  5061.4 1841.32  5199.7 1843.42    5236 1843.24
  5360.1 1840.45  5460.2 1840.06  5642.2 1845.05  5672.5 1847.52  5732.9 1848.19
  5753.1 1850.12  5773.2  1848.2  5976.8 1851.69    6231 1854.24  6904.3 1859.02
#Mann= 15 ,-1 , 0
  3372.3     .07       0  3936.4    .035       0  3954.3     .07       0
  4281.8    .035       0  4311.2     .07       0  4807.4    .035       0
  4877.7     .07       0  5009.8     .07       0  5034.7     .07       0
  5199.7    .035       0    5236     .07       0  5360.1    .035       0
  5460.2     .07       0  5976.8    .035       0    6231     .07       0
Bank Sta=5009.8,5034.7
XS Rating Curve= 0 ,0
Exp/Cntr=0.3,0.1

Type RM Length L Ch R = 1 ,13110   ,1791,1791,1791
BEGIN DESCRIPTION:
Mapping XS f62d8c0b
END DESCRIPTION:
XS GIS Cut Line= 3
      1436674.04      6928356.99      1438090.67      6928384.77
      1439326.79      6928363.93
#Sta/Elev= 30
  3568.3 1844.02  4043.7 1843.77  4199.4 1840.54  4424.2 1839.79  4589.5 1841.81
  4759.5 1842.31  4899.8 1840.06  4939.5 1838.27  4989.9 1838.22    4997 1835.95
  4997.5 1835.45  5022.1 1835.95  5029.5 1838.75  5099.5 1839.09  5129.6 1840.54
  5139.6 1842.55  5189.6 1846.31  5310.1 1848.14  5369.6 1848.89  5389.6 1847.92
  5409.6  1849.3  5439.6 1848.57  5449.6 1849.47  5499.6  1849.1  5559.6 1850.47
  5689.6 1850.37  5909.7 1851.44  5979.7 1852.67  6069.7 1852.24  6221.5 1853.38
#Mann= 7 ,-1 , 0
  3568.3     .07       0  4043.7    .035       0  4424.2     .07       0
    4997     .07       0  5022.1     .07       0  5310.1    .035       0
  5559.6     .07       0
Bank Sta=4997,5022.1
XS Rating Curve= 0 ,0
Exp/Cntr=0.3,0.1

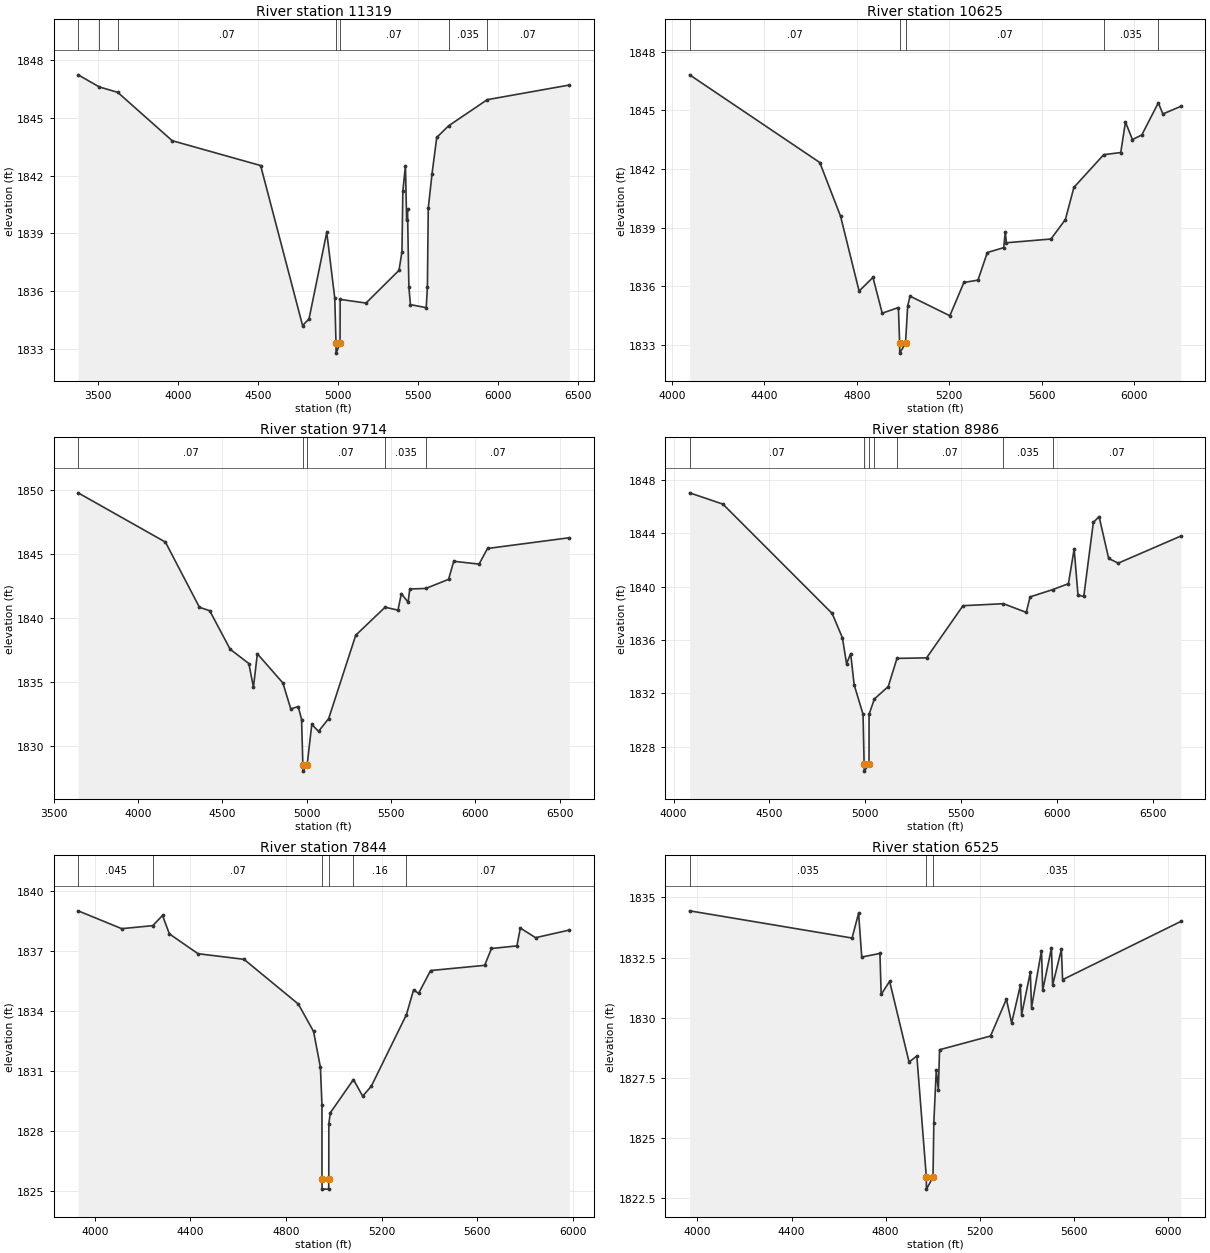
Type RM Length L Ch R = 1 ,11319   ,694,694,694
BEGIN DESCRIPTION:
Mapping XS 415c8def
END DESCRIPTION:
XS GIS Cut Line= 3
      1435990.71      6928676.43       1437618.3      6928871.75
      1438941.01      6929424.68
#Sta/Elev= 30
  3374.9 1847.23  3508.1  1846.6    3623 1846.32  3963.4 1843.81  4516.7 1842.52
  4779.2 1834.21  4819.5 1834.56  4930.3 1839.05  4980.6 1835.63  4988.2 1833.28
  4988.7 1832.78  5013.4 1833.28  5014.2 1835.57  5175.8 1835.38  5382.5 1837.08
  5400.8 1838.05  5406.3 1841.18  5422.5  1842.5  5430.1 1839.69  5435.5 1840.27
  5444.1  1836.2  5453.9  1835.3  5552.5 1835.14  5559.9 1836.19  5565.3  1840.3
  5589.1  1842.1  5618.4 1843.98  5692.3 1844.58  5934.4 1845.94  6447.8  1846.7
#Mann= 7 ,-1 , 0
  3374.9     .07       0  3508.1    .035       0    3623     .07       0
  4988.2     .07       0  5013.4     .07       0  5692.3    .035       0
  5934.4     .07       0
Bank Sta=4988.2,5013.4
XS Rating Curve= 0 ,0
Exp/Cntr=0.3,0.1

Type RM Length L Ch R = 1 ,10625   ,911,911,911
BEGIN DESCRIPTION:
Mapping XS e13c1bcb
END DESCRIPTION:
XS GIS Cut Line= 3
       1436382.3      6929350.04      1437305.95      6929363.93
      1438491.71      6929551.16
#Sta/Elev= 30
  4077.2 1846.81    4640 1842.33    4730 1839.58    4810 1835.76    4870 1836.46
    4910 1834.63    4980 1834.92  4985.3 1833.09  4985.8 1832.59  5010.7 1833.09
  5020.2 1835.01  5030.4  1835.5  5202.5  1834.5  5263.2  1836.2    5324 1836.32
  5364.5 1837.73  5435.3 1837.98  5442.1 1838.77  5447.1 1838.23  5639.5 1838.42
  5701.9 1839.41    5739 1841.06  5867.8 1842.73  5941.5 1842.84  5961.8  1844.4
  5992.1  1843.5  6032.6 1843.74    6104 1845.38  6123.7 1844.81  6201.4  1845.2
#Mann= 5 ,-1 , 0
  4077.2     .07       0  4985.3     .07       0  5010.7     .07       0
  5867.8    .035       0    6104     .07       0
Bank Sta=4985.3,5010.7
XS Rating Curve= 0 ,0
Exp/Cntr=0.3,0.1

Type RM Length L Ch R = 1 ,9714    ,728,728,728
BEGIN DESCRIPTION:
Mapping XS 24bd91f0
END DESCRIPTION:
XS GIS Cut Line= 3
      1436261.96       6929761.5      1437607.45      6929945.96
       1439159.1      6929848.31
#Sta/Elev= 30
  3644.6 1849.78  4162.4 1845.93  4364.3 1840.83  4424.9 1840.57    4546 1837.56
    4657 1836.44  4684.3 1834.59  4707.5  1837.2  4858.9 1834.92  4905.8 1832.89
  4949.7 1833.08  4969.9 1832.06  4977.3 1828.53  4977.8 1828.03  5002.9 1828.53
  5030.3 1831.68  5070.4 1831.14  5130.5 1832.14  5290.8 1838.65  5464.9 1840.84
  5541.3 1840.61  5561.3  1841.9  5601.4 1841.23  5611.4 1842.26  5707.2 1842.31
  5841.4 1843.02  5871.9 1844.43  6022.2 1844.21  6072.3 1845.43  6557.4 1846.27
#Mann= 5 ,-1 , 0
  3644.6     .07       0  4977.3     .07       0  5002.9     .07       0
  5464.9    .035       0  5707.2     .07       0
Bank Sta=4977.3,5002.9
XS Rating Curve= 0 ,0
Exp/Cntr=0.3,0.1

Type RM Length L Ch R = 1 ,8986    ,1142,1142,1142
BEGIN DESCRIPTION:
Mapping XS a81491f6
END DESCRIPTION:
XS GIS Cut Line= 3
      1436403.19      6930016.72      1437264.28      6930356.99
      1438901.56      6930301.49
#Sta/Elev= 30
  4083.6 1847.04  4257.6 1846.19  4827.5    1838  4881.2 1836.17  4902.7 1834.23
  4924.2 1834.99  4942.3 1832.66  4988.8 1830.44  4994.4 1826.68  4994.9 1826.18
    5020 1826.68  5020.2 1830.44    5048 1831.59  5120.3 1832.52  5165.9 1834.63
  5320.4 1834.67  5510.5 1838.58  5721.4 1838.73  5840.7 1838.08  5860.7 1839.24
  5979.8 1839.79  6060.8 1840.23  6090.8 1842.83  6110.8 1839.38  6140.9 1839.27
  6190.9 1844.82  6220.9 1845.26  6270.9 1842.12    6321 1841.77  6647.7  1843.8
#Mann= 7 ,-1 , 0
  4083.6     .07       0  4994.4     .07       0    5020     .07       0
    5048     .16       0  5165.9     .07       0  5721.4    .035       0
  5979.8     .07       0
Bank Sta=4994.4,5020
XS Rating Curve= 0 ,0
Exp/Cntr=0.3,0.1

Type RM Length L Ch R = 1 ,7844    ,1319,1319,1319
BEGIN DESCRIPTION:
Mapping XS 4e22210a
END DESCRIPTION:
XS GIS Cut Line= 3
      1436458.69      6931898.68      1437278.17      6931225.04
      1437923.98      6930468.13
#Sta/Elev= 30
  3930.1    1839  4112.6 1838.11  4242.6 1838.26  4283.4 1838.77  4312.1 1837.85
  4431.9 1836.86  4624.4 1836.58  4851.6 1834.35  4915.5 1832.98  4944.2 1831.19
  4950.7 1829.31  4950.8 1825.61  4951.3 1825.11  4978.7 1825.11  4979.2 1825.61
  4979.4 1828.37  4985.6 1828.92  5082.5 1830.58    5121 1829.75  5157.3 1830.25
  5304.2 1833.82    5334 1835.05  5355.1 1834.88  5405.4 1836.02  5631.6 1836.28
  5660.1 1837.12  5766.6 1837.25  5780.9 1838.14  5844.6 1837.66  5985.9 1838.04
#Mann= 6 ,-1 , 0
  3930.1    .045       0  4242.6     .07       0  4950.8     .07       0
  4979.2     .07       0  5082.5     .16       0  5304.2     .07       0
Bank Sta=4950.8,4979.2
XS Rating Curve= 0 ,0
Exp/Cntr=0.3,0.1

Type RM Length L Ch R = 1 ,6525    ,85,85,85
BEGIN DESCRIPTION:
Mapping XS 3fe2dfc6
END DESCRIPTION:
XS GIS Cut Line= 3
      1437403.18      6933044.45      1437653.17      6932044.49
      1437896.23      6931016.68
#Sta/Elev= 30
  3967.1 1834.44  4657.1 1833.31    4685 1834.34  4698.3 1832.52  4775.6 1832.67
  4780.8 1830.97  4816.8 1831.51  4899.3 1828.16  4932.4 1828.41  4972.7 1823.38
  4973.2 1822.88  5001.1 1823.38  5004.5 1825.63  5014.8 1827.82  5023.7    1827
  5028.9 1828.67  5245.4 1829.24  5312.8 1830.77  5335.1 1829.78  5372.2 1831.34
  5377.4 1830.12  5414.5 1831.89  5419.6 1830.42  5461.9 1832.79  5467.1 1831.14
  5504.2 1832.89  5509.3 1831.35  5546.5 1832.84  5551.6 1831.58    6054    1834
#Mann= 3 ,-1 , 0
  3967.1    .035       0  4972.7      .1       0  5001.1    .035       0
Bank Sta=4972.7,5001.1
XS Rating Curve= 0 ,0
Exp/Cntr=0.3,0.1

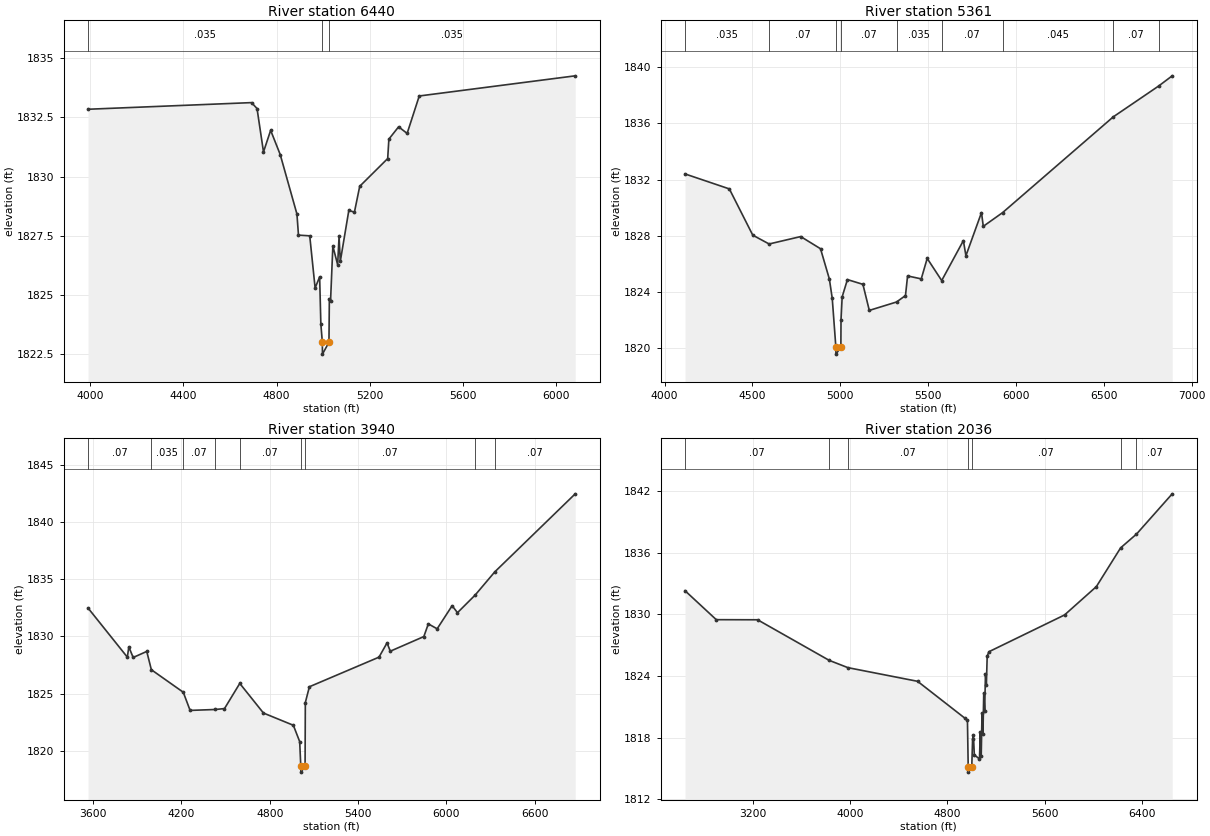
Type RM Length L Ch R = 1 ,6440    ,1079,1079,1079
BEGIN DESCRIPTION:
Mapping XS f93f6dda
END DESCRIPTION:
XS GIS Cut Line= 3
      1437500.38       6933072.3      1437715.67      6932120.88
      1437979.56      6931037.53
#Sta/Elev= 30
  3990.5 1832.84  4692.1 1833.12  4715.7 1832.87  4743.4 1831.04  4774.1 1831.95
  4815.1 1830.93  4886.9 1828.42  4893.5 1827.53  4941.8  1827.5  4964.9  1825.3
  4984.3 1825.77  4989.5 1823.78  4995.9 1823.01  4996.4 1822.51  5024.3 1823.01
    5026 1824.85  5031.2 1824.77    5041 1827.07  5061.6 1826.28  5067.7 1827.48
  5072.9 1826.42  5109.5 1828.57  5133.6  1828.5  5156.3 1829.59  5276.3 1830.76
  5281.4 1831.58  5323.2  1832.1  5359.7 1831.82  5411.7  1833.4    6081 1834.25
#Mann= 3 ,-1 , 0
  3990.5    .035       0  4995.9    .035       0  5024.3    .035       0
Bank Sta=4995.9,5024.3
XS Rating Curve= 0 ,0
Exp/Cntr=0.3,0.1

Type RM Length L Ch R = 1 ,5361    ,1421,1421,1421
BEGIN DESCRIPTION:
Mapping XS 26055ab1
END DESCRIPTION:
XS GIS Cut Line= 3
      1437521.22       6933093.1      1438305.95      6932683.38
      1440139.25        6932232.
#Sta/Elev= 30
    4116  1832.4  4368.4 1831.33  4501.7 1828.03  4594.8  1827.4  4774.6 1827.93
  4887.4 1827.06  4937.7  1824.9  4954.1 1823.52  4974.7 1820.04  4975.2 1819.54
  5003.2 1820.04  5004.1 1822.01  5010.6 1823.63  5040.5 1824.86  5128.7 1824.52
    5165 1822.66  5320.1 1823.26    5371 1823.72  5382.9 1825.12  5460.8 1824.91
  5494.6 1826.37  5577.1 1824.79  5700.6 1827.64    5715 1826.56  5803.6 1829.64
  5813.9 1828.66    5924 1829.64  6553.6 1836.47  6811.8 1838.67  6889.3  1839.4
#Mann= 9 ,-1 , 0
    4116    .035       0  4594.8     .07       0  4974.7     .07       0
  5003.2     .07       0  5320.1    .035       0  5577.1     .07       0
    5924    .045       0  6553.6     .07       0  6811.8    .045       0
Bank Sta=4974.7,5003.2
XS Rating Curve= 0 ,0
Exp/Cntr=0.3,0.1

Type RM Length L Ch R = 1 ,3940    ,1904,1904,1904
BEGIN DESCRIPTION:
Mapping XS 1ad35a78
END DESCRIPTION:
XS GIS Cut Line= 4
      1437541.99      6933228.39      1438562.82      6933410.68
      1438948.24      6933467.97      1440614.86      6932587.78
#Sta/Elev= 30
  3565.2 1832.49  3832.4 1828.19  3842.5 1829.09  3871.9 1828.16  3964.4 1828.69
  3995.6 1827.09  4212.5 1825.12    4259 1823.53  4430.1 1823.61  4492.7 1823.69
  4596.6 1825.89  4757.5  1823.3  4960.7 1822.23  5003.8  1820.8  5011.3 1818.63
  5011.8 1818.13  5040.4 1818.63  5042.2 1824.22  5069.8  1825.6  5542.9 1828.19
  5597.6 1829.44  5619.6 1828.71  5847.6 1829.99  5878.2  1831.1  5938.1 1830.67
  6039.9 1832.69  6076.3 1832.08  6196.2 1833.62  6329.7 1835.65  6876.6 1842.48
#Mann= 9 ,-1 , 0
  3565.2     .07       0  3995.6    .035       0  4212.5     .07       0
  4430.1    .035       0  4596.6     .07       0  5011.3     .07       0
  5040.4     .07       0  6196.2    .035       0  6329.7     .07       0
Bank Sta=5011.3,5040.4
XS Rating Curve= 0 ,0
Exp/Cntr=0.3,0.1

Type RM Length L Ch R = 1 ,2036    ,0,0,0
BEGIN DESCRIPTION:
Mapping XS 48527726
END DESCRIPTION:
XS GIS Cut Line= 3
      1437555.04      6933381.19      1439026.36      6934353.39
      1440562.02      6932712.09
#Sta/Elev= 30
  2639.2  1832.3  2896.6 1829.48  3236.8 1829.47  3826.2 1825.52  3980.3 1824.81
  4554.1 1823.48  4943.5 1819.89  4964.5 1819.67  4970.8 1815.14  4971.3 1814.64
  5000.1 1815.14    5007 1817.87  5013.8 1818.21  5021.1 1816.32  5063.6 1815.92
  5070.5 1818.55  5077.8 1816.22  5084.6 1820.38    5092 1818.32  5098.8 1822.35
  5106.1 1820.56    5113 1824.22  5120.3 1823.12  5127.1 1825.93  5141.3 1826.36
  5764.1 1829.94    6026  1832.7  6225.6 1836.47  6356.3 1837.81  6650.4 1841.73
#Mann= 7 ,-1 , 0
  2639.2     .07       0  3826.2    .035       0  3980.3     .07       0
  4970.8     .07       0  5000.1     .07       0  6225.6    .035       0
  6356.3     .07       0
Bank Sta=4970.8,5000.1
XS Rating Curve= 0 ,0
Exp/Cntr=0.3,0.1

Chan Stop Cuts=-1
Use User Specified Reach Order=0
Composite Channel Slope=5