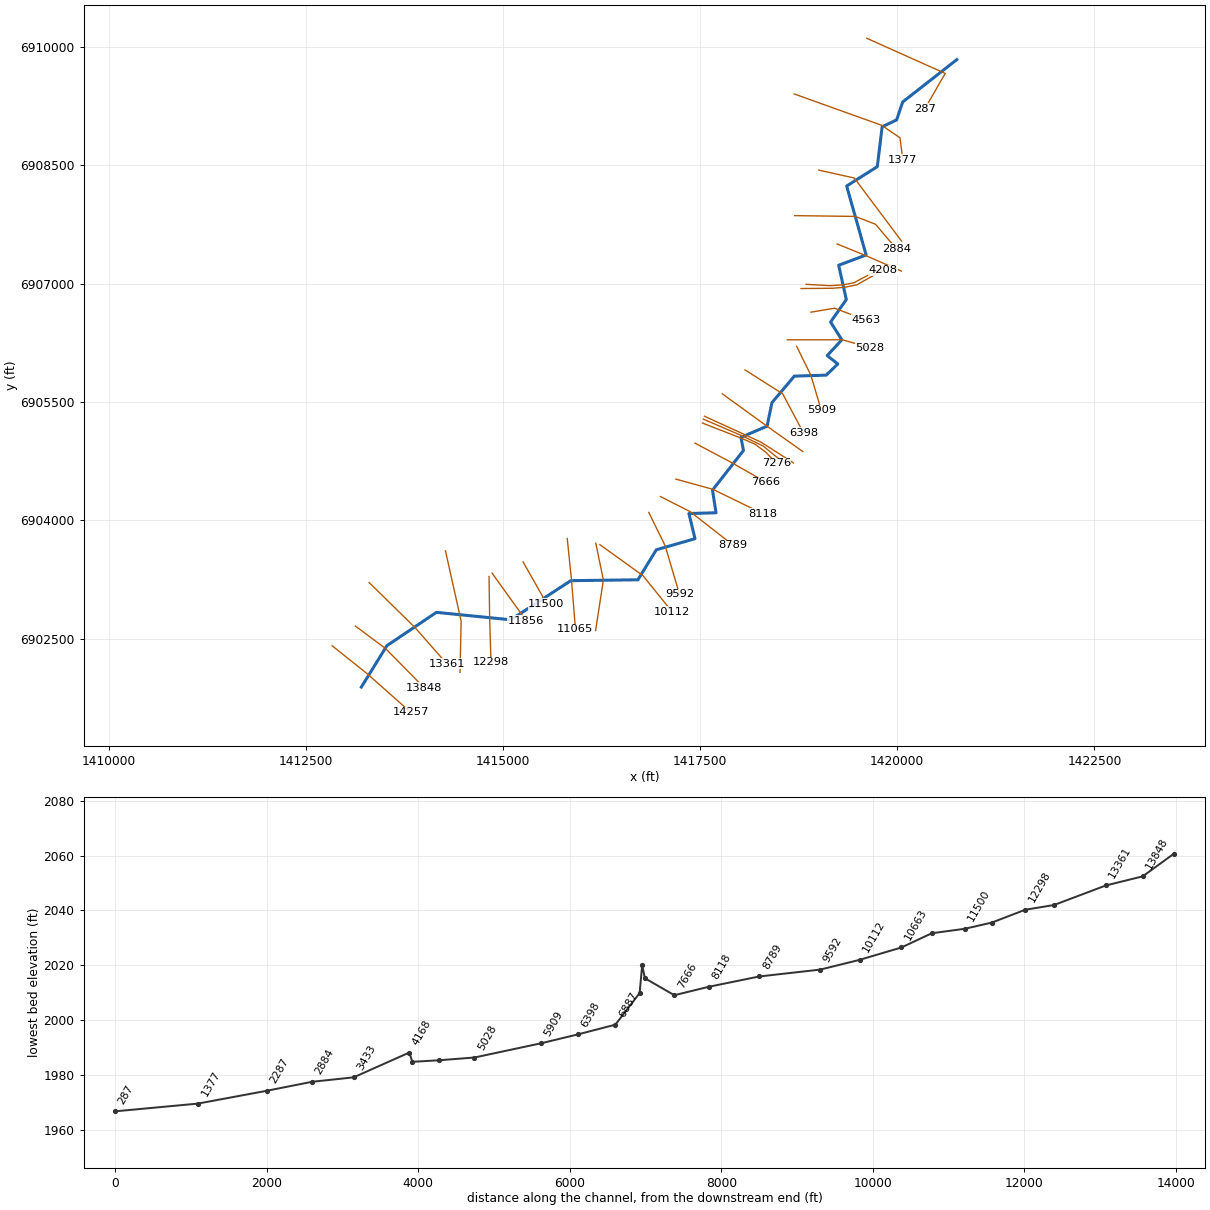
--- East China Creek Trib1.prj (project) ---

Proj Title=East China Creek Trib1 Base Level Engineering
Current Plan=p01
Default Exp/Contr=0.3,0.1
English Units
Geom File=g01
Flow File=f01
Plan File=p01
BEGIN DESCRIPTION:
East China Creek Trib1
END DESCRIPTION:

--- East China Creek Trib1.p01 (plan) ---

Plan Title=Multiple Run
Short Identifier=Multiple
Geom File=g01
Flow File=f01
Subcritical Flow
K Sum by GR= 0
Std Step Tol= 0.01
Critical Tol= 0.01
Num of Std Step Trials= 20
Max Error Tol= 0.3
Flow Tol Ratio= 0.001
Split Flow NTrial= 30
Split Flow Tol= 0.02
Split Flow Ratio= 0.02
Log Output Level= 0
Friction Slope Method= 1
Unsteady Friction Slope Method= 2
Unsteady Bridges Friction Slope Method= 1
Parabolic Critical Depth
Global Vel Dist=  1 , 1 , 1
Global Log Level= 0
CheckData=True
Encroach Param= -1, 0, 0, 0
BEGIN DESCRIPTION:
Multiple Run
END DESCRIPTION:

--- East China Creek Trib1.f01 (steady flow) ---

Flow Title=Multiple
Number of Profiles=7
Profile Names=10-year,25-year,50-year,1pct_min,100-year,1pct_plu,500-year
River Rch & RM= East China Creek,Reach-1,14257
     265     374     466     288     576    1148     889
River Rch & RM= East China Creek,Reach-1,13361
     390     561     706     442     882    1759    1393
River Rch & RM= East China Creek,Reach-1,6887
     419     604     762     477     953    1901    1509
River Rch & RM= East China Creek,Reach-1,2884
     514     748     950     599    1195    2385    1916
River Rch & RM= East China Creek,Reach-1,287
     576     843    1075     681    1358    2709    2194
Boundary for River Rch & Prof#=East China Creek,Reach-1,1
Up Type=0
Dn Type=3
Dn Slope=0.005
Boundary for River Rch & Prof#=East China Creek,Reach-1,2
Up Type=0
Dn Type=3
Dn Slope=0.005
Boundary for River Rch & Prof#=East China Creek,Reach-1,3
Up Type=0
Dn Type=3
Dn Slope=0.005
Boundary for River Rch & Prof#=East China Creek,Reach-1,4
Up Type=0
Dn Type=3
Dn Slope=0.005
Boundary for River Rch & Prof#=East China Creek,Reach-1,5
Up Type=0
Dn Type=3
Dn Slope=0.005
Boundary for River Rch & Prof#=East China Creek,Reach-1,6
Up Type=0
Dn Type=3
Dn Slope=0.005
Boundary for River Rch & Prof#=East China Creek,Reach-1,7
Up Type=0
Dn Type=3
Dn Slope=0.005

--- East China Creek Trib1.g01 (geometry) ---

Geom Title=Existing Conditions

River Reach=East China Creek,Reach-1
Reach XY= 30
      1413205.00      6901888.00      1413528.07      6902411.85
      1414156.58      6902834.33      1415099.03      6902740.14
      1415860.86      6903235.94      1416711.74      6903247.13
      1416944.94      6903627.39      1417435.44      6903767.80
      1417358.36      6904086.75      1417702.18      6904095.94
      1417656.97      6904382.32      1418049.60      6904885.57
      1418018.35      6905051.81      1418349.41      6905193.61
      1418410.46      6905490.45      1418694.88      6905827.66
      1419099.15      6905840.06      1419246.11      6905981.49
      1419111.90      6906088.00      1419297.50      6906288.00
      1419154.51      6906512.96      1419354.03      6906798.29
      1419256.96      6907232.13      1419605.32      6907362.88
      1419358.52      6908236.54      1419746.87      6908481.93
      1419808.36      6908986.75      1419991.77      6909074.28
      1420068.62      6909301.22      1420755.00      6909838.00

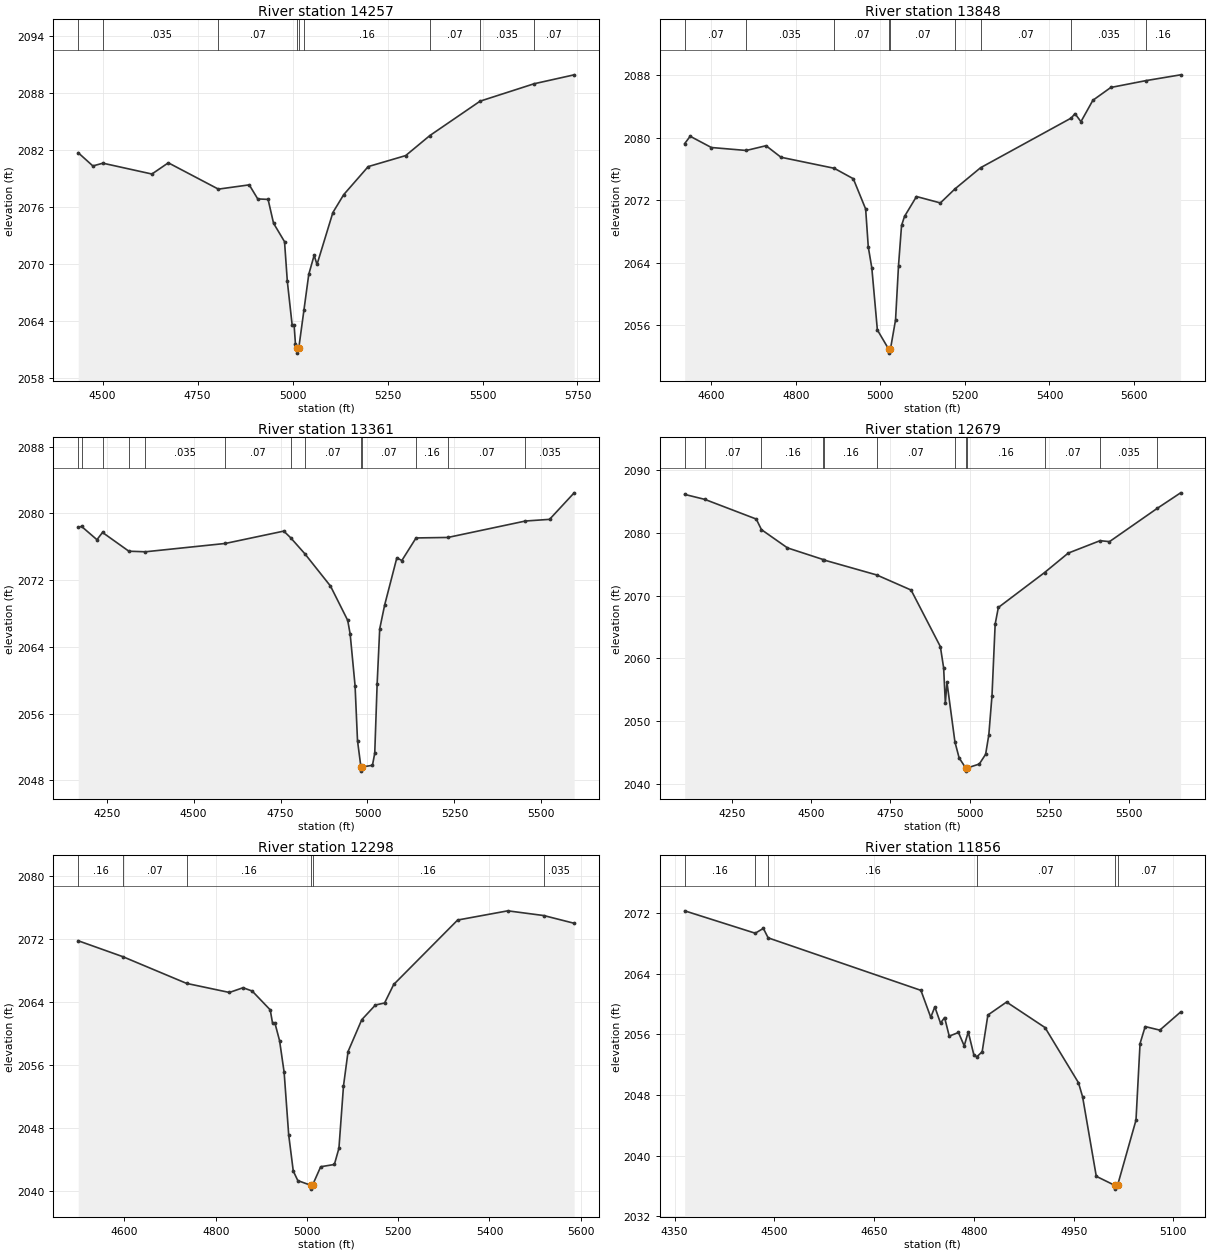
Type RM Length L Ch R = 1,14257,409,409,409
BEGIN DESCRIPTION:
Mapping XS 03dab705
END DESCRIPTION:
XS GIS Cut Line= 3
      1412834.49      6902410.82      1413278.91      6902056.67
      1413830.49      6901567.53
#Sta/Elev= 30
  4435.7 2081.70  4474.3 2080.31  4500.7 2080.60  4629.7 2079.46  4672.9 2080.64
  4804.7 2077.87  4885.9 2078.32  4908.3 2076.84  4935.5 2076.79  4949.9 2074.28
  4978.8 2072.34  4986.2 2068.15  4998.9 2063.56  5004.0 2063.56  5007.5 2061.61
  5012.2 2061.11  5012.4 2060.61  5016.2 2061.11  5029.8 2065.11  5042.6 2068.90
  5056.8 2070.91  5064.3 2069.94  5106.1 2075.41  5134.6 2077.29  5199.0 2080.24
  5297.7 2081.40  5361.4 2083.51  5493.7 2087.13  5635.8 2088.96  5741.2 2089.90
#Mann=9,-1,0
  4435.7    0.07       0  4500.7   0.035       0  4804.7    0.07       0
  5012.2    0.07       0  5016.2    0.07       0  5029.8    0.16       0
  5361.4    0.07       0  5493.7   0.035       0  5635.8    0.07       0
Bank Sta=5012.2,5016.2
Exp/Cntr=0.3,0.1

Type RM Length L Ch R = 1,13848,487,487,487
BEGIN DESCRIPTION:
Mapping XS 15387b81
END DESCRIPTION:
XS GIS Cut Line= 3
      1413129.62      6902660.83      1413511.55      6902376.11
      1414000.58      6901880.14
#Sta/Elev= 30
  4537.3 2079.26  4550.3 2080.20  4600.4 2078.76  4683.0 2078.38  4729.7 2078.99
  4765.1 2077.51  4890.9 2076.10  4936.1 2074.76  4965.3 2070.88  4971.5 2066.03
  4979.9 2063.33  4993.0 2055.39  5019.9 2052.92  5020.1 2052.42  5023.9 2052.92
  5036.0 2056.67  5043.0 2063.62  5050.2 2068.77  5057.2 2069.93  5085.5 2072.48
  5142.0 2071.66  5176.6 2073.46  5237.1 2076.17  5451.7 2082.54  5460.3 2083.10
  5474.5 2082.07  5502.7 2084.81  5545.1 2086.45  5628.4 2087.33  5710.2 2088.07
#Mann=9,-1,0
  4537.3    0.07       0  4683.0   0.035       0  4890.9    0.07       0
  5019.9    0.07       0  5023.9    0.07       0  5176.6    0.16       0
  5237.1    0.07       0  5451.7   0.035       0  5628.4    0.16       0
Bank Sta=5019.9,5023.9
Exp/Cntr=0.3,0.1

Type RM Length L Ch R = 1,13361,682,682,682
BEGIN DESCRIPTION:
Mapping XS c5c6801f
END DESCRIPTION:
XS GIS Cut Line= 3
      1413303.28      6903212.53      1413886.55      6902640.00
      1414288.75      6902182.33
#Sta/Elev= 30
  4167.9 2078.34  4177.6 2078.44  4221.8 2076.85  4237.8 2077.72  4313.6 2075.47
  4361.1 2075.40  4591.2 2076.40  4759.2 2077.88  4778.6 2077.10  4819.5 2075.18
  4893.6 2071.29  4943.1 2067.18  4950.2 2065.53  4964.3 2059.34  4971.3 2052.75
  4981.1 2049.60  4981.3 2049.10  4985.1 2049.60  5014.3 2049.80  5020.9 2051.25
  5027.8 2059.59  5035.2 2066.16  5049.4 2069.02  5084.5 2074.68  5098.8 2074.35
  5139.7 2077.06  5231.4 2077.12  5454.4 2079.09  5523.8 2079.29  5594.5 2082.47
#Mann=13,-1,0
  4167.9   0.035       0  4177.6    0.07       0  4237.8   0.035       0
  4313.6    0.07       0  4361.1   0.035       0  4591.2    0.07       0
  4778.6   0.035       0  4819.5    0.07       0  4981.1    0.07       0
  4985.1    0.07       0  5139.7    0.16       0  5231.4    0.07       0
  5454.4   0.035       0
Bank Sta=4981.1,4985.1
Exp/Cntr=0.3,0.1

Type RM Length L Ch R = 1,12679,381,381,381
BEGIN DESCRIPTION:
Mapping XS 8e8a83c0
END DESCRIPTION:
XS GIS Cut Line= 3
      1414271.16      6903614.02      1414469.89      6902723.33
      1414456.00      6902074.07
#Sta/Elev= 30
  4102.1 2086.12  4165.8 2085.32  4327.5 2082.19  4343.9 2080.50  4425.9 2077.59
  4539.1 2075.72  4542.1 2075.64  4706.7 2073.28  4815.2 2070.87  4907.4 2061.85
  4917.7 2058.47  4923.1 2052.85  4928.2 2056.16  4953.3 2046.65  4966.5 2044.11
  4987.3 2042.50  4987.6 2042.00  4991.6 2042.50  5030.0 2043.13  5050.0 2044.69
  5060.0 2047.78  5070.0 2054.02  5080.0 2065.44  5090.0 2068.09  5235.6 2073.66
  5310.1 2076.76  5410.4 2078.74  5440.1 2078.59  5590.9 2083.91  5664.1 2086.37
#Mann=12,-1,0
  4102.1    0.16       0  4165.8    0.07       0  4343.9    0.16       0
  4539.1    0.07       0  4542.1    0.16       0  4706.7    0.07       0
  4953.3    0.16       0  4987.3    0.07       0  4991.6    0.16       0
  5235.6    0.07       0  5410.4   0.035       0  5590.9    0.07       0
Bank Sta=4987.3,4991.6
Exp/Cntr=0.3,0.1

Type RM Length L Ch R = 1,12298,442,442,442
BEGIN DESCRIPTION:
Mapping XS 2e90a45e
END DESCRIPTION:
XS GIS Cut Line= 3
      1414824.05      6903289.30      1414831.00      6902792.78
      1414848.35      6902202.71
#Sta/Elev= 30
  4498.7 2071.79  4596.1 2069.78  4736.2 2066.38  4830.0 2065.23  4860.0 2065.83
  4880.0 2065.41  4919.5 2063.02  4924.5 2061.37  4930.0 2061.30  4940.0 2059.11
  4950.0 2055.10  4960.0 2047.15  4970.0 2042.57  4980.0 2041.35  5007.9 2040.77
  5008.2 2040.27  5012.2 2040.77  5030.1 2043.11  5060.1 2043.40  5070.1 2045.46
  5080.1 2053.37  5090.1 2057.73  5120.1 2061.77  5150.1 2063.64  5170.1 2063.89
  5190.1 2066.24  5330.2 2074.42  5440.2 2075.59  5519.1 2074.99  5585.6 2074.01
#Mann=6,-1,0
  4498.7    0.16       0  4596.1    0.07       0  4736.2    0.16       0
  5007.9    0.07       0  5012.2    0.16       0  5519.1   0.035       0
Bank Sta=5007.9,5012.2
Exp/Cntr=0.3,0.1

Type RM Length L Ch R = 1,11856,356,356,356
BEGIN DESCRIPTION:
Mapping XS 289bc790
END DESCRIPTION:
XS GIS Cut Line= 3
      1414862.26      6903330.95      1415226.83      6902824.03
      1415295.49      6902724.03
#Sta/Elev= 30
  4365.1 2072.26  4471.2 2069.31  4483.4 2069.95  4490.6 2068.70  4720.3 2061.78
  4735.1 2058.23  4741.2 2059.60  4749.8 2057.46  4755.9 2058.20  4762.9 2055.75
  4776.8 2056.23  4785.4 2054.47  4791.5 2056.30  4799.8 2053.32  4804.3 2053.02
  4812.4 2053.69  4821.0 2058.53  4849.1 2060.24  4906.9 2056.88  4957.2 2049.61
  4963.4 2047.76  4984.0 2037.28  5011.7 2036.09  5012.0 2035.59  5016.0 2036.09
  5043.7 2044.68  5049.8 2054.77  5057.5 2057.01  5079.5 2056.54  5110.8 2058.93
#Mann=6,-1,0
  4365.1    0.16       0  4471.2    0.07       0  4490.6    0.16       0
  4804.3    0.07       0  5011.7    0.07       0  5016.0    0.07       0
Bank Sta=5011.7,5016
Exp/Cntr=0.3,0.1

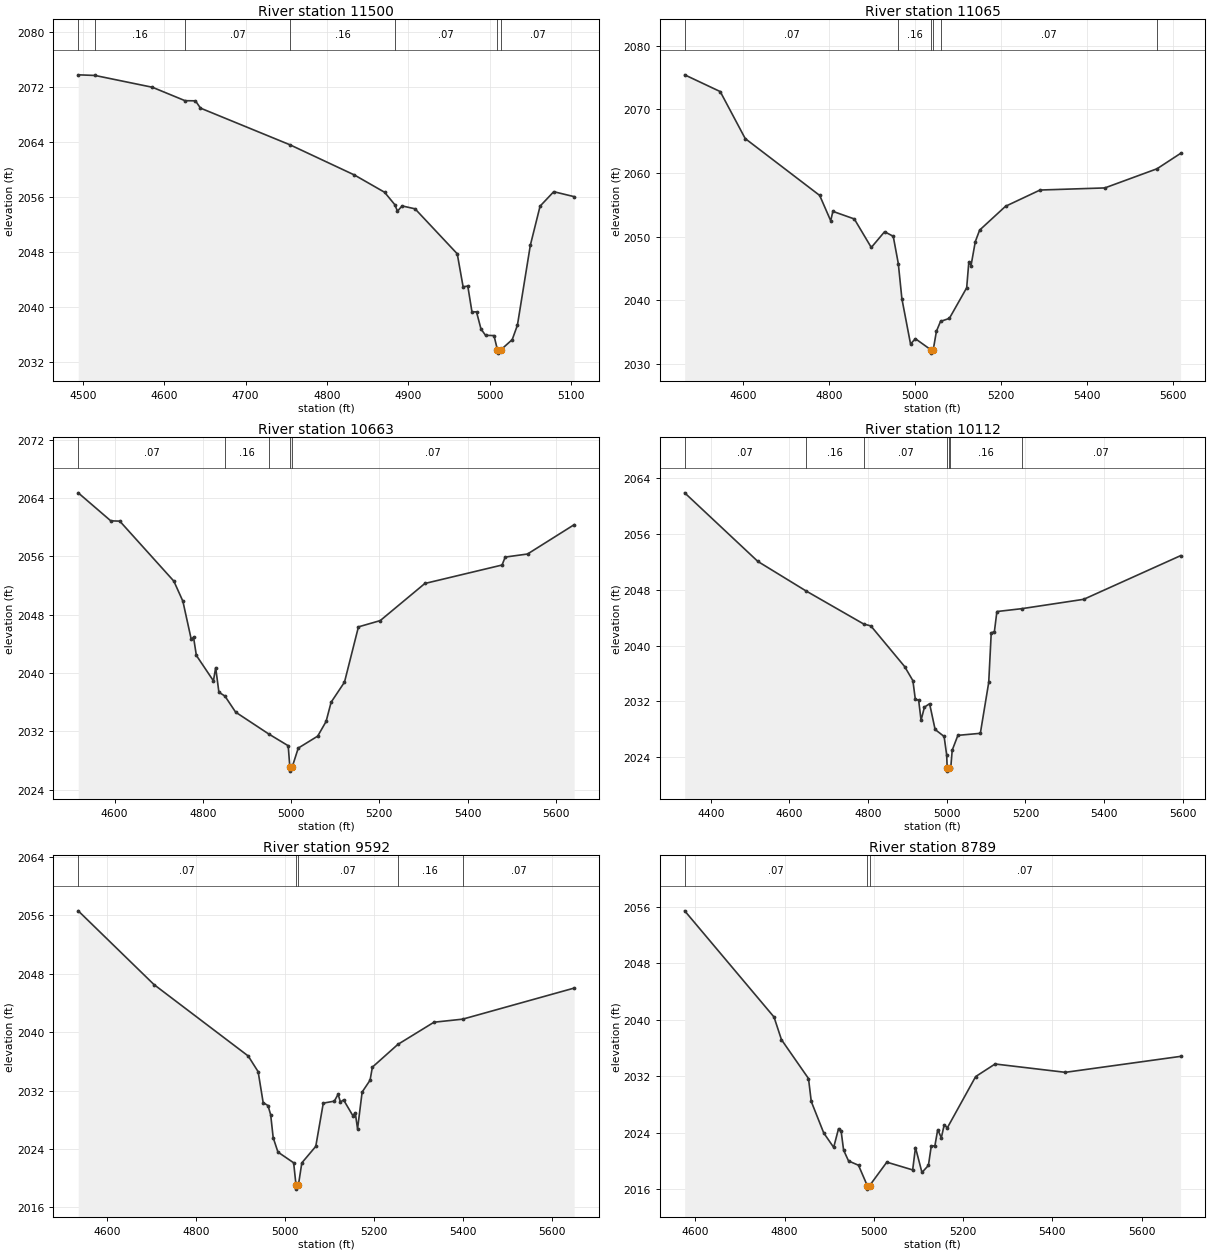
Type RM Length L Ch R = 1,11500,435,435,435
BEGIN DESCRIPTION:
Mapping XS 328d3855
END DESCRIPTION:
XS GIS Cut Line= 3
      1415255.46      6903473.37      1415495.06      6903051.46
      1415550.87      6902939.83
#Sta/Elev= 30
  4494.1 2073.80  4514.7 2073.71  4585.4 2071.99  4625.5 2070.04  4638.3 2070.02
  4644.5 2068.96  4754.7 2063.62  4833.8 2059.24  4870.9 2056.73  4883.4 2054.94
  4886.8 2053.98  4892.5 2054.74  4908.4 2054.32  4960.3 2047.78  4967.5 2042.99
  4973.3 2043.08  4978.4 2039.34  4984.0 2039.34  4989.5 2036.85  4995.1 2035.93
  5005.5 2035.89  5009.7 2033.84  5010.0 2033.34  5014.1 2033.84  5027.9 2035.30
  5034.3 2037.39  5050.2 2049.02  5062.2 2054.71  5079.0 2056.81  5104.1 2056.09
#Mann=7,-1,0
  4494.1    0.07       0  4514.7    0.16       0  4625.5    0.07       0
  4754.7    0.16       0  4883.4    0.07       0  5009.7    0.07       0
  5014.1    0.07       0
Bank Sta=5009.7,5014.1
Exp/Cntr=0.3,0.1

Type RM Length L Ch R = 1,11065,402,402,402
BEGIN DESCRIPTION:
Mapping XS 695be6a5
END DESCRIPTION:
XS GIS Cut Line= 3
      1415815.37      6903770.19      1415870.06      6903236.35
      1415919.49      6902622.37
#Sta/Elev= 30
  4464.6 2075.42  4547.2 2072.79  4605.3 2065.41  4778.4 2056.48  4804.0 2052.50
  4809.0 2053.98  4858.8 2052.79  4898.3 2048.31  4929.2 2050.78  4949.3 2050.07
  4961.1 2045.78  4969.4 2040.27  4989.5 2033.16  5000.9 2033.98  5037.3 2032.22
  5037.6 2031.72  5042.2 2032.22  5049.7 2035.16  5059.2 2036.70  5079.8 2037.18
  5120.0 2041.98  5125.0 2046.05  5130.1 2045.46  5140.0 2049.22  5150.1 2051.04
  5210.3 2054.78  5290.5 2057.33  5441.0 2057.66  5562.4 2060.67  5617.2 2063.09
#Mann=6,-1,0
  4464.6    0.07       0  4961.1    0.16       0  5037.3    0.07       0
  5042.2    0.16       0  5059.2    0.07       0  5562.4    0.16       0
Bank Sta=5037.3,5042.2
Exp/Cntr=0.3,0.1

Type RM Length L Ch R = 1,10663,551,551,551
BEGIN DESCRIPTION:
Mapping XS bb83b4e3
END DESCRIPTION:
XS GIS Cut Line= 3
      1416177.36      6903710.29      1416273.71      6903244.17
      1416174.75      6902603.54
#Sta/Elev= 30
  4517.4 2064.69  4591.2 2060.85  4611.6 2060.81  4734.2 2052.58  4754.6 2049.84
  4773.7 2044.58  4778.8 2044.90  4785.2 2042.40  4823.9 2038.91  4829.0 2040.72
  4836.3 2037.35  4850.0 2036.82  4874.2 2034.62  4949.4 2031.62  4993.4 2030.01
  4997.2 2027.03  4997.5 2026.53  5002.1 2027.03  5016.2 2029.69  5060.3 2031.33
  5079.3 2033.34  5090.7 2035.98  5121.0 2038.73  5152.6 2046.31  5202.0 2047.17
  5303.2 2052.26  5478.2 2054.79  5485.3 2055.88  5535.9 2056.30  5641.6 2060.32
#Mann=5,-1,0
  4517.4    0.07       0  4850.0    0.16       0  4949.4    0.07       0
  4997.2    0.07       0  5002.1    0.07       0
Bank Sta=4997.2,5002.1
Exp/Cntr=0.3,0.1

Type RM Length L Ch R = 1,10112,520,520,520
BEGIN DESCRIPTION:
Mapping XS fc25e2b1
END DESCRIPTION:
XS GIS Cut Line= 3
      1416229.47      6903692.06      1416776.31      6903298.85
      1417145.13      6902841.72
#Sta/Elev= 30
  4333.8 2061.86  4519.9 2052.04  4642.0 2047.83  4788.8 2043.09  4807.2 2042.81
  4893.1 2036.99  4914.0 2034.98  4920.1 2032.35  4928.7 2032.16  4934.8 2029.32
  4943.4 2031.19  4956.5 2031.68  4970.5 2027.99  4993.4 2026.99  4999.9 2024.34
  5001.2 2022.53  5001.6 2022.03  5006.3 2022.53  5007.1 2022.53  5010.3 2022.53
  5014.0 2025.03  5028.4 2027.15  5085.5 2027.44  5106.8 2034.72  5113.2 2041.82
  5121.2 2041.98  5127.6 2044.87  5190.7 2045.28  5348.3 2046.62  5594.7 2052.87
#Mann=7,-1,0
  4333.8    0.07       0  4642.0    0.16       0  4788.8    0.07       0
  5001.2    0.07       0  5006.3    0.07       0  5007.1    0.16       0
  5190.7    0.07       0
Bank Sta=5001.2,5006.3
Exp/Cntr=0.3,0.1

Type RM Length L Ch R = 1,9592,803,803,803
BEGIN DESCRIPTION:
Mapping XS 41deead7
END DESCRIPTION:
XS GIS Cut Line= 3
      1416849.24      6904100.91      1417057.56      6903676.46
      1417239.30      6903061.15
#Sta/Elev= 30
  4534.6 2056.63  4704.9 2046.52  4916.6 2036.73  4938.9 2034.58  4950.2 2030.34
  4961.1 2029.93  4967.1 2028.66  4972.7 2025.54  4983.4 2023.56  5018.7 2022.09
  5024.1 2018.98  5024.5 2018.48  5029.2 2018.98  5037.1 2022.08  5068.4 2024.34
  5085.3 2030.27  5110.1 2030.54  5118.6 2031.49  5123.8 2030.42  5130.9 2030.71
  5151.8 2028.54  5157.1 2028.95  5162.3 2026.74  5172.6 2031.79  5190.4 2033.41
  5195.6 2035.20  5252.9 2038.32  5334.0 2041.36  5398.5 2041.78  5649.0 2046.04
#Mann=5,-1,0
  4534.6    0.07       0  5024.1    0.07       0  5029.2    0.07       0
  5252.9    0.16       0  5398.5    0.07       0
Bank Sta=5024.1,5029.2
Exp/Cntr=0.3,0.1

Type RM Length L Ch R = 1,8789,671,671,671
BEGIN DESCRIPTION:
Mapping XS ca1c4e4b
END DESCRIPTION:
XS GIS Cut Line= 3
      1416997.64      6904301.47      1417372.66      6904111.35
      1417916.94      6903686.87
#Sta/Elev= 30
  4576.4 2055.40  4776.5 2040.36  4793.1 2037.16  4853.7 2031.65  4859.9 2028.40
  4887.8 2023.95  4910.1 2021.90  4921.0 2024.56  4926.7 2024.24  4932.3 2021.52
  4943.4 2019.98  4965.7 2019.37  4985.3 2016.49  4985.7 2015.99  4990.6 2016.49
  5029.1 2019.81  5087.0 2018.71  5093.3 2021.88  5107.8 2018.35  5122.3 2019.35
  5128.6 2022.07  5136.8 2022.13  5143.1 2024.41  5151.2 2023.26  5157.6 2025.09
  5164.7 2024.68  5228.1 2031.93  5271.6 2033.71  5428.9 2032.53  5687.1 2034.79
#Mann=3,-1,0
  4576.4    0.07       0  4985.3    0.07       0  4990.6    0.07       0
Bank Sta=4985.3,4990.6
Exp/Cntr=0.3,0.1

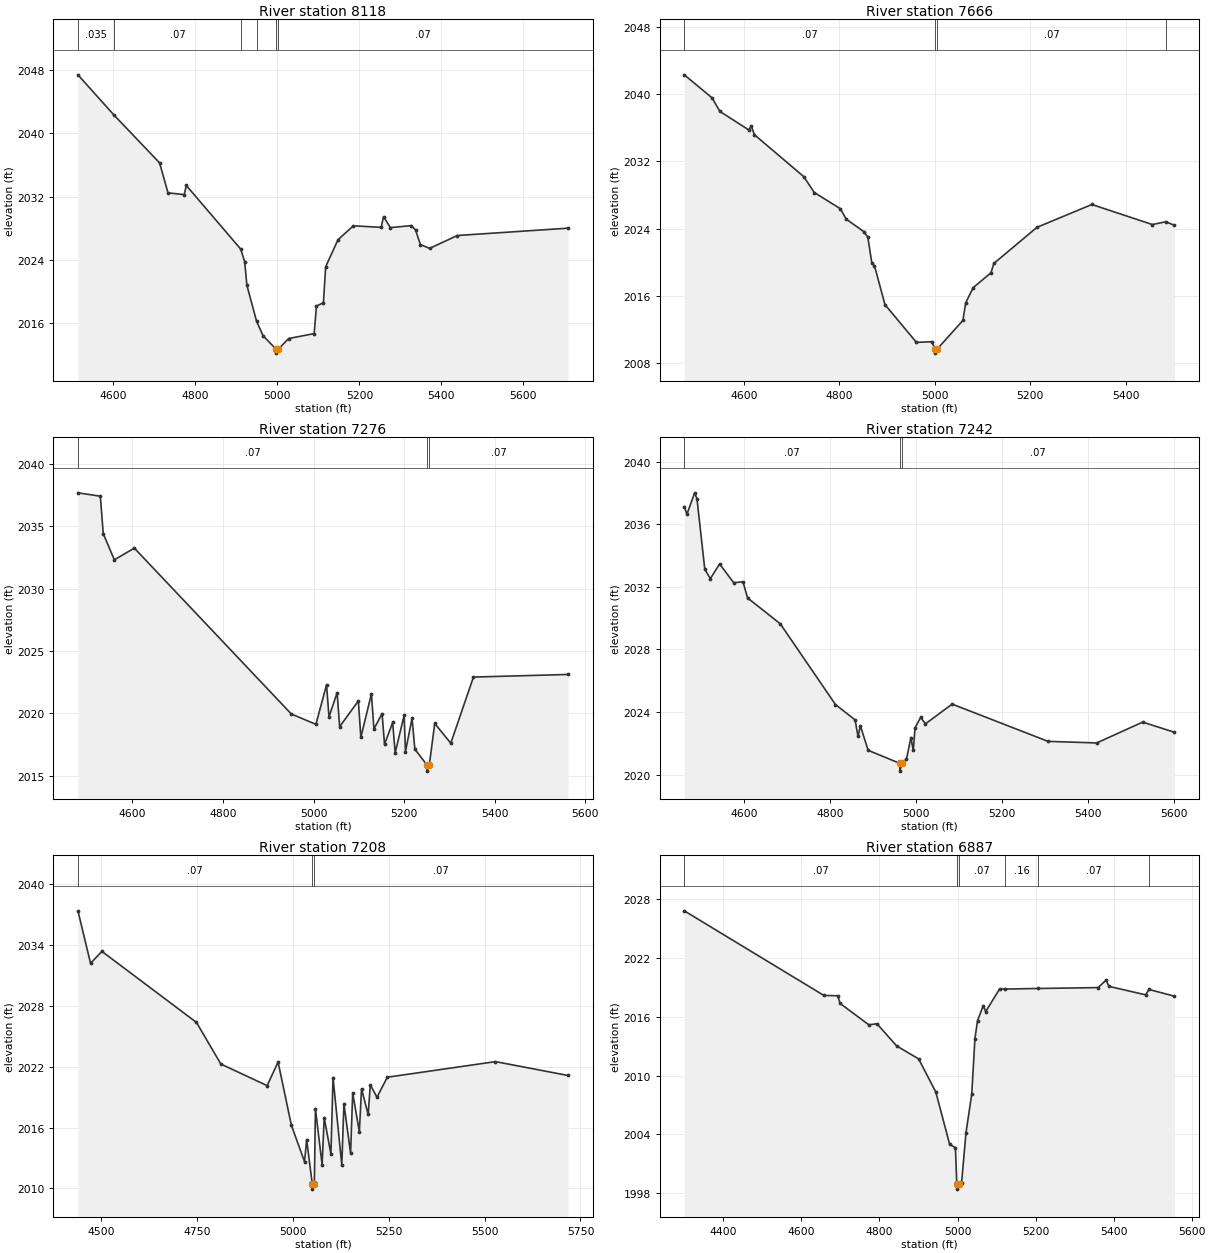
Type RM Length L Ch R = 1,8118,452,452,452
BEGIN DESCRIPTION:
Mapping XS 81a16ddf
END DESCRIPTION:
XS GIS Cut Line= 3
      1417193.00      6904522.80      1417664.33      6904392.60
      1418299.44      6904082.86
#Sta/Elev= 30
  4513.5 2047.42  4601.3 2042.34  4712.7 2036.28  4733.2 2032.49  4772.7 2032.26
  4777.9 2033.42  4910.6 2025.37  4920.2 2023.78  4925.6 2020.80  4949.2 2016.25
  4965.1 2014.41  4996.8 2012.71  4997.2 2012.21  5002.1 2012.71  5027.7 2014.06
  5089.7 2014.68  5095.3 2018.16  5112.3 2018.60  5117.8 2023.14  5147.9 2026.56
  5185.4 2028.32  5253.0 2028.12  5259.1 2029.48  5275.6 2028.09  5326.2 2028.34
  5337.0 2027.81  5348.7 2025.95  5371.3 2025.46  5438.9 2027.09  5709.1 2028.02
#Mann=6,-1,0
  4513.5   0.035       0  4601.3    0.07       0  4910.6   0.035       0
  4949.2    0.07       0  4996.8    0.07       0  5002.1    0.07       0
Bank Sta=4996.8,5002.1
Exp/Cntr=0.3,0.1

Type RM Length L Ch R = 1,7666,390,390,390
BEGIN DESCRIPTION:
Mapping XS fb02a52d
END DESCRIPTION:
XS GIS Cut Line= 3
      1417435.18      6904978.53      1417901.31      6904731.15
      1418335.21      6904482.90
#Sta/Elev= 30
  4474.9 2042.33  4533.2 2039.58  4549.5 2037.97  4609.8 2035.77  4615.4 2036.21
  4621.9 2035.19  4725.4 2030.19  4747.4 2028.30  4802.0 2026.37  4814.3 2025.13
  4851.6 2023.62  4859.6 2022.99  4868.0 2019.91  4873.6 2019.57  4895.6 2014.93
  4961.6 2010.43  4994.2 2010.51  4999.9 2009.65  5000.4 2009.15  5005.3 2009.65
  5059.0 2013.05  5064.8 2015.15  5080.6 2016.96  5118.0 2018.74  5123.8 2019.84
  5214.2 2024.15  5329.4 2026.87  5456.2 2024.48  5484.2 2024.81  5502.5 2024.39
#Mann=4,-1,0
  4474.9    0.07       0  4999.9    0.07       0  5005.3    0.07       0
  5484.2    0.16       0
Bank Sta=4999.9,5005.3
Exp/Cntr=0.3,0.1

Type RM Length L Ch R = 1,7276,34,34,34
BEGIN DESCRIPTION:
Mapping XS 8fa9746a
END DESCRIPTION:
XS GIS Cut Line= 5
      1417528.90      6905233.76      1418015.89      6905043.65
      1418195.58      6904965.52      1418336.21      6904861.35
      1418464.89      6904722.56
#Sta/Elev= 30
  4479.5 2037.67  4529.0 2037.40  4535.5 2034.39  4560.0 2032.30  4604.1 2033.24
  4951.0 2019.94  5005.3 2019.11  5028.8 2022.28  5034.2 2019.71  5052.2 2021.65
  5057.7 2018.92  5099.1 2020.99  5104.6 2018.07  5128.0 2021.56  5133.5 2018.74
  5151.5 2019.97  5156.9 2017.51  5174.9 2019.26  5180.4 2016.83  5200.3 2019.84
  5203.1 2016.92  5217.7 2019.60  5223.9 2017.12  5250.5 2015.86  5250.9 2015.36
  5255.9 2015.86  5267.8 2019.18  5303.3 2017.60  5353.4 2022.90  5562.5 2023.11
#Mann=3,-1,0
  4479.5    0.07       0  5250.5    0.07       0  5255.9    0.07       0
Bank Sta=5250.5,5255.9
Exp/Cntr=0.3,0.1

Type RM Length L Ch R = 1,7242,34,34,34
BEGIN DESCRIPTION:
Mapping XS 3438aeae
END DESCRIPTION:
XS GIS Cut Line= 4
      1417539.36      6905283.22      1418036.73      6905069.69
      1418299.75      6904942.08      1418538.42      6904746.95
#Sta/Elev= 30
  4459.8 2037.12  4465.9 2036.63  4484.0 2038.00  4489.4 2037.61  4507.5 2033.13
  4520.4 2032.52  4542.1 2033.46  4574.8 2032.26  4596.5 2032.32  4607.2 2031.29
  4683.3 2029.64  4812.0 2024.48  4857.7 2023.50  4864.5 2022.45  4870.0 2023.12
  4888.1 2021.56  4961.5 2020.73  4962.0 2020.23  4966.9 2020.73  4977.4 2021.00
  4987.8 2022.37  4993.2 2021.55  4997.4 2023.00  5010.3 2023.66  5021.7 2023.25
  5083.8 2024.51  5307.2 2022.13  5420.6 2022.03  5527.6 2023.36  5601.7 2022.71
#Mann=3,-1,0
  4459.8    0.07       0  4961.5    0.07       0  4966.9    0.07       0
Bank Sta=4961.5,4966.9
Exp/Cntr=0.3,0.1

Type RM Length L Ch R = 1,7208,321,321,321
BEGIN DESCRIPTION:
Mapping XS 486ee7fb
END DESCRIPTION:
XS GIS Cut Line= 4
      1417554.96      6905319.69      1418062.77      6905087.92
      1418271.10      6904991.56      1418684.67      6904727.53
#Sta/Elev= 30
  4439.4 2037.40  4472.4 2032.21  4501.8 2033.40  4748.6 2026.38  4812.2 2022.27
  4932.9 2020.14  4961.4 2022.47  4996.1 2016.23  5030.4 2012.63  5035.9 2014.82
  5050.6 2010.42  5051.0 2009.92  5056.0 2010.42  5058.8 2017.87  5076.2 2012.33
  5081.7 2016.98  5099.2 2013.38  5104.7 2020.94  5127.6 2012.29  5133.1 2018.35
  5150.5 2013.46  5156.0 2019.42  5173.4 2015.57  5179.0 2019.83  5196.4 2017.29
  5201.9 2020.22  5219.3 2018.99  5246.3 2020.97  5528.4 2022.51  5717.8 2021.14
#Mann=3,-1,0
  4439.4    0.07       0  5050.6    0.07       0  5056.0    0.07       0
Bank Sta=5050.6,5056
Exp/Cntr=0.3,0.1

Type RM Length L Ch R = 1,6887,489,489,489
BEGIN DESCRIPTION:
Mapping XS e956f3f8
END DESCRIPTION:
XS GIS Cut Line= 3
      1417781.49      6905603.56      1418357.04      6905186.88
      1418802.37      6904871.76
#Sta/Elev= 30
  4299.9 2026.84  4657.5 2018.20  4693.1 2018.17  4699.3 2017.38  4772.8 2015.20
  4793.6 2015.31  4843.9 2013.05  4900.3 2011.72  4944.4 2008.34  4980.0 2002.98
  4994.7 2002.65  4998.2 1998.92  4998.6 1998.42  5003.6 1998.92  5010.5 1999.07
  5021.7 2004.16  5036.5 2008.13  5044.7 2013.80  5051.3 2015.62  5066.1 2017.16
  5072.2 2016.55  5107.9 2018.86  5121.5 2018.85  5206.2 2018.91  5360.3 2019.00
  5381.2 2019.78  5387.7 2019.13  5482.1 2018.26  5490.7 2018.81  5556.0 2018.12
#Mann=6,-1,0
  4299.9    0.07       0  4998.2    0.07       0  5003.6    0.07       0
  5121.5    0.16       0  5206.2    0.07       0  5490.7    0.16       0
Bank Sta=4998.2,5003.6
Exp/Cntr=0.3,0.1

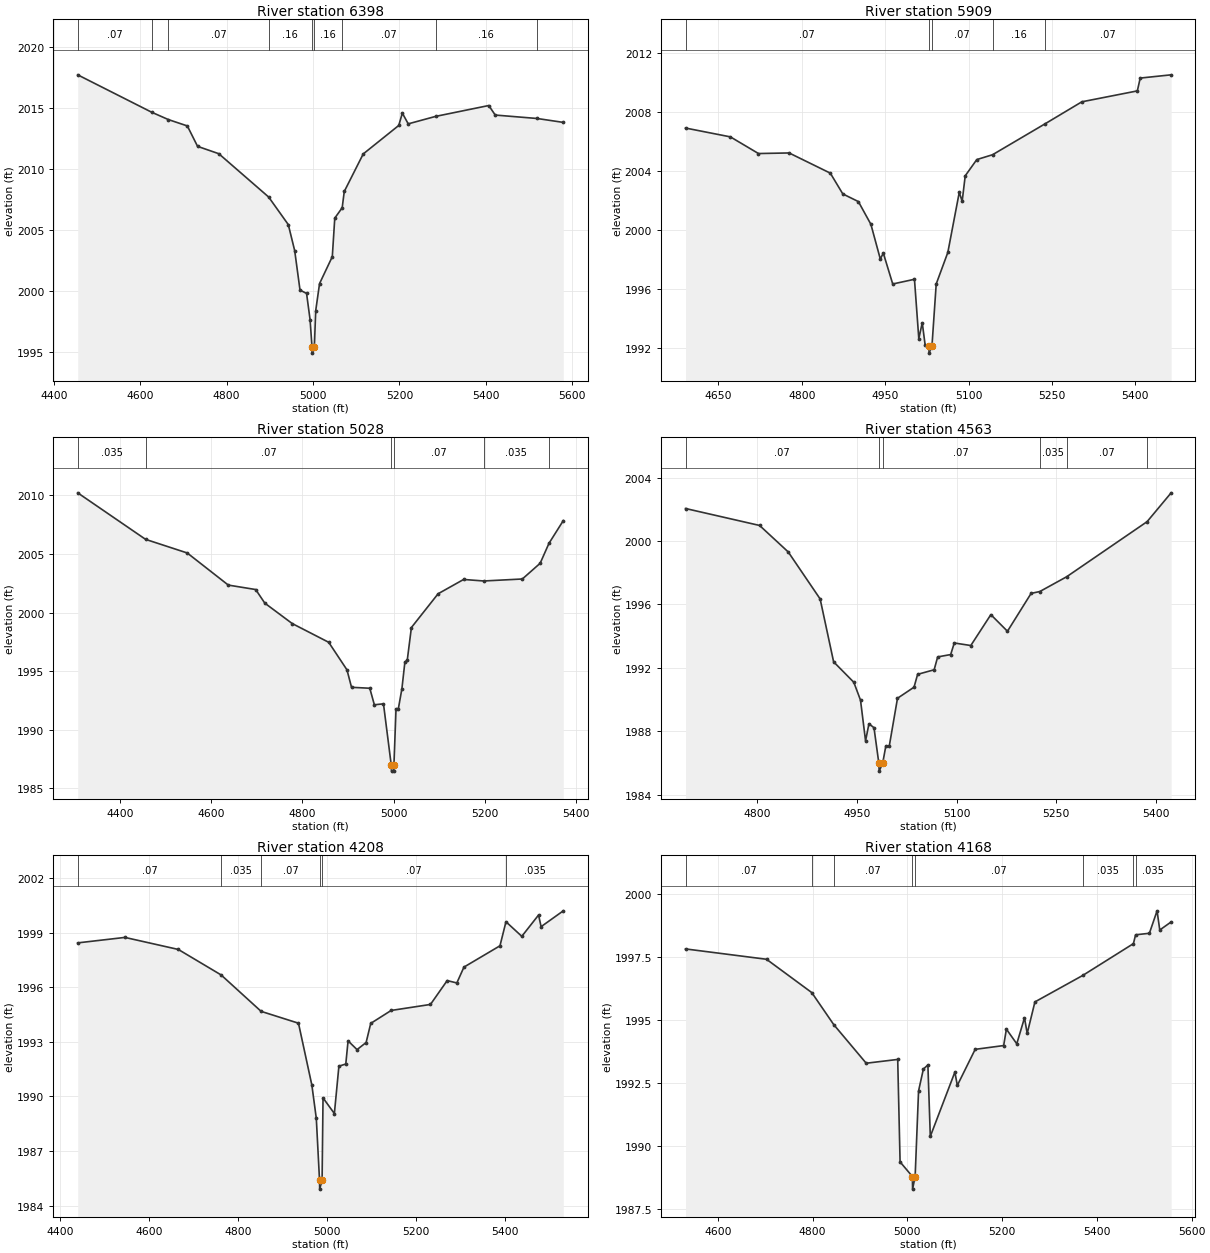
Type RM Length L Ch R = 1,6398,489,489,489
BEGIN DESCRIPTION:
Mapping XS 73fceeca
END DESCRIPTION:
XS GIS Cut Line= 3
      1418070.54      6905905.65      1418547.14      6905603.54
      1418810.10      6905108.87
#Sta/Elev= 30
  4455.0 2017.69  4626.4 2014.63  4665.0 2014.03  4708.9 2013.51  4732.6 2011.84
  4781.7 2011.24  4897.1 2007.70  4942.7 2005.44  4957.5 2003.31  4969.8 2000.09
  4985.0 1999.81  4993.1 1997.68  4997.6 1995.43  4998.0 1994.93  5003.0 1995.43
  5006.2 1998.41  5015.1 2000.62  5044.6 2002.82  5050.3 2005.97  5067.5 2006.82
  5072.3 2008.15  5116.2 2011.22  5198.5 2013.55  5206.8 2014.56  5220.4 2013.68
  5283.8 2014.29  5406.9 2015.18  5421.9 2014.40  5518.7 2014.12  5579.5 2013.80
#Mann=9,-1,0
  4455.0    0.07       0  4626.4    0.16       0  4665.0    0.07       0
  4897.1    0.16       0  4997.6    0.07       0  5003.0    0.16       0
  5067.5    0.07       0  5283.8    0.16       0  5518.7    0.07       0
Bank Sta=4997.6,5003
Exp/Cntr=0.3,0.1

Type RM Length L Ch R = 1,5909,881,881,881
BEGIN DESCRIPTION:
East China Creek Trib1 8.0
END DESCRIPTION:
XS GIS Cut Line= 3
      1418724.23      6906205.10      1418905.00      6905838.00
      1419036.68      6905392.76
#Sta/Elev= 30
  4590.8 2006.94  4671.5 2006.34  4722.0 2005.21  4777.1 2005.25  4851.2 2003.88
  4873.7 2002.47  4901.7 2001.95  4924.2 2000.41  4941.1 1998.06  4946.6 1998.45
  4963.5 1996.36  5002.6 1996.68  5010.4 1992.65  5016.6 1993.73  5021.9 1992.19
  5028.4 1992.17  5028.9 1991.67  5034.1 1992.17  5041.7 1996.36  5062.6 1998.50
  5083.2 2002.58  5088.4 2001.97  5093.9 2003.70  5114.7 2004.80  5143.1 2005.13
  5237.2 2007.22  5303.7 2008.72  5403.5 2009.46  5408.7 2010.33  5464.3 2010.55
#Mann=5,-1,0
  4590.8    0.07       0  5028.4    0.07       0  5034.1    0.07       0
  5143.1    0.16       0  5237.2    0.07       0
Bank Sta=5028.4,5034.1
Exp/Cntr=0.3,0.1

Type RM Length L Ch R = 1,5028,465,465,465
BEGIN DESCRIPTION:
East China Creek Trib1 7.0
END DESCRIPTION:
XS GIS Cut Line= 3
      1418605.00      6906288.00      1419305.00      6906288.00
      1419655.00      6906188.00
#Sta/Elev= 30
  4307.5 2010.22  4456.3 2006.25  4547.5 2005.09  4637.5 2002.35  4697.5 2001.97
  4717.5 2000.81  4777.5 1999.07  4857.5 1997.47  4897.5 1995.12  4907.5 1993.63
  4947.5 1993.55  4957.5 1992.14  4977.5 1992.22  4994.6 1986.98  4995.1 1986.48
  4999.9 1986.48  5000.4 1986.98  5005.0 1991.80  5010.1 1991.80  5017.9 1993.51
  5024.4 1995.78  5029.6 1995.94  5038.7 1998.73  5097.2 2001.61  5153.1 2002.83
  5197.2 2002.70  5281.8 2002.87  5320.8 2004.21  5340.1 2005.91  5371.5 2007.85
#Mann=6,-1,0
  4307.5   0.035       0  4456.3    0.07       0  4994.6    0.07       0
  5000.4    0.07       0  5197.2   0.035       0  5340.1    0.07       0
Bank Sta=4994.6,5000.4
Exp/Cntr=0.3,0.1

Type RM Length L Ch R = 1,4563,355,355,355
BEGIN DESCRIPTION:
East China Creek Trib1 6.0
END DESCRIPTION:
XS GIS Cut Line= 3
      1418905.05      6906638.01      1419205.00      6906688.00
      1419605.01      6906538.00
#Sta/Elev= 30
  4691.8 2002.06  4803.3 2000.99  4846.4 1999.32  4894.5 1996.35  4914.8 1992.38
  4945.2 1991.09  4955.3 1989.96  4962.9 1987.39  4968.0 1988.47  4975.6 1988.22
  4982.9 1985.98  4983.4 1985.48  4988.7 1985.98  4993.4 1987.06  4998.6 1987.06
  5011.0 1990.08  5035.9 1990.78  5041.3 1991.59  5066.2 1991.88  5071.5 1992.69
  5091.1 1992.84  5096.5 1993.57  5121.4 1993.41  5151.6 1995.36  5176.6 1994.31
  5212.2 1996.70  5225.4 1996.82  5265.7 1997.75  5386.9 2001.23  5423.1 2003.05
#Mann=6,-1,0
  4691.8    0.07       0  4982.9    0.07       0  4988.7    0.07       0
  5225.4   0.035       0  5265.7    0.07       0  5386.9   0.035       0
Bank Sta=4982.9,4988.7
Exp/Cntr=0.3,0.1

Type RM Length L Ch R = 1,4208,40,40,40
BEGIN DESCRIPTION:
Mapping XS ab6dbbe1
END DESCRIPTION:
XS GIS Cut Line= 5
      1418778.80      6906937.45      1419178.10      6906940.92
      1419330.88      6906953.07      1419487.13      6906984.32
      1419818.72      6907170.08
#Sta/Elev= 30
  4440.0 1998.43  4546.2 1998.73  4666.2 1998.07  4762.5 1996.67  4852.5 1994.67
  4936.5 1994.02  4966.6 1990.62  4976.6 1988.79  4983.8 1985.41  4984.2 1984.91
  4989.6 1985.41  4991.7 1989.92  5017.2 1989.06  5027.4 1991.66  5042.9 1991.78
  5048.0 1993.05  5068.2 1992.57  5088.6 1992.96  5099.0 1994.01  5144.9 1994.72
  5233.3 1995.05  5270.9 1996.36  5292.6 1996.23  5308.6 1997.10  5389.6 1998.27
  5403.1 1999.59  5438.7 1998.79  5476.4 1999.96  5482.1 1999.32  5532.0 2000.19
#Mann=6,-1,0
  4440.0    0.07       0  4762.5   0.035       0  4852.5    0.07       0
  4983.8    0.07       0  4989.6    0.07       0  5403.1   0.035       0
Bank Sta=4983.8,4989.6
Exp/Cntr=0.3,0.1

Type RM Length L Ch R = 1,4168,735,735,735
BEGIN DESCRIPTION:
Mapping XS 72a23337
END DESCRIPTION:
XS GIS Cut Line= 5
      1418844.36      6906990.90      1419150.32      6906973.91
      1419313.52      6906984.32      1419448.94      6907010.37
      1419816.96      6907206.53
#Sta/Elev= 30
  4531.8 1997.81  4702.7 1997.40  4798.2 1996.08  4844.6 1994.81  4913.1 1993.28
  4979.6 1993.43  4984.6 1989.37  5010.6 1988.79  5011.0 1988.29  5016.4 1988.79
  5023.6 1992.18  5033.8 1993.05  5043.3 1993.21  5048.4 1990.38  5100.3 1992.93
  5105.4 1992.40  5143.1 1993.83  5203.2 1993.98  5209.0 1994.63  5230.9 1994.05
  5247.2 1995.08  5252.9 1994.46  5269.2 1995.71  5370.2 1996.76  5477.1 1998.02
  5481.7 1998.37  5510.8 1998.43  5527.0 1999.32  5532.7 1998.56  5556.7 1998.88
#Mann=8,-1,0
  4531.8    0.07       0  4798.2   0.035       0  4844.6    0.07       0
  5010.6    0.07       0  5016.4    0.07       0  5370.2   0.035       0
  5477.1    0.07       0  5481.7   0.035       0
Bank Sta=5010.6,5016.4
Exp/Cntr=0.3,0.1

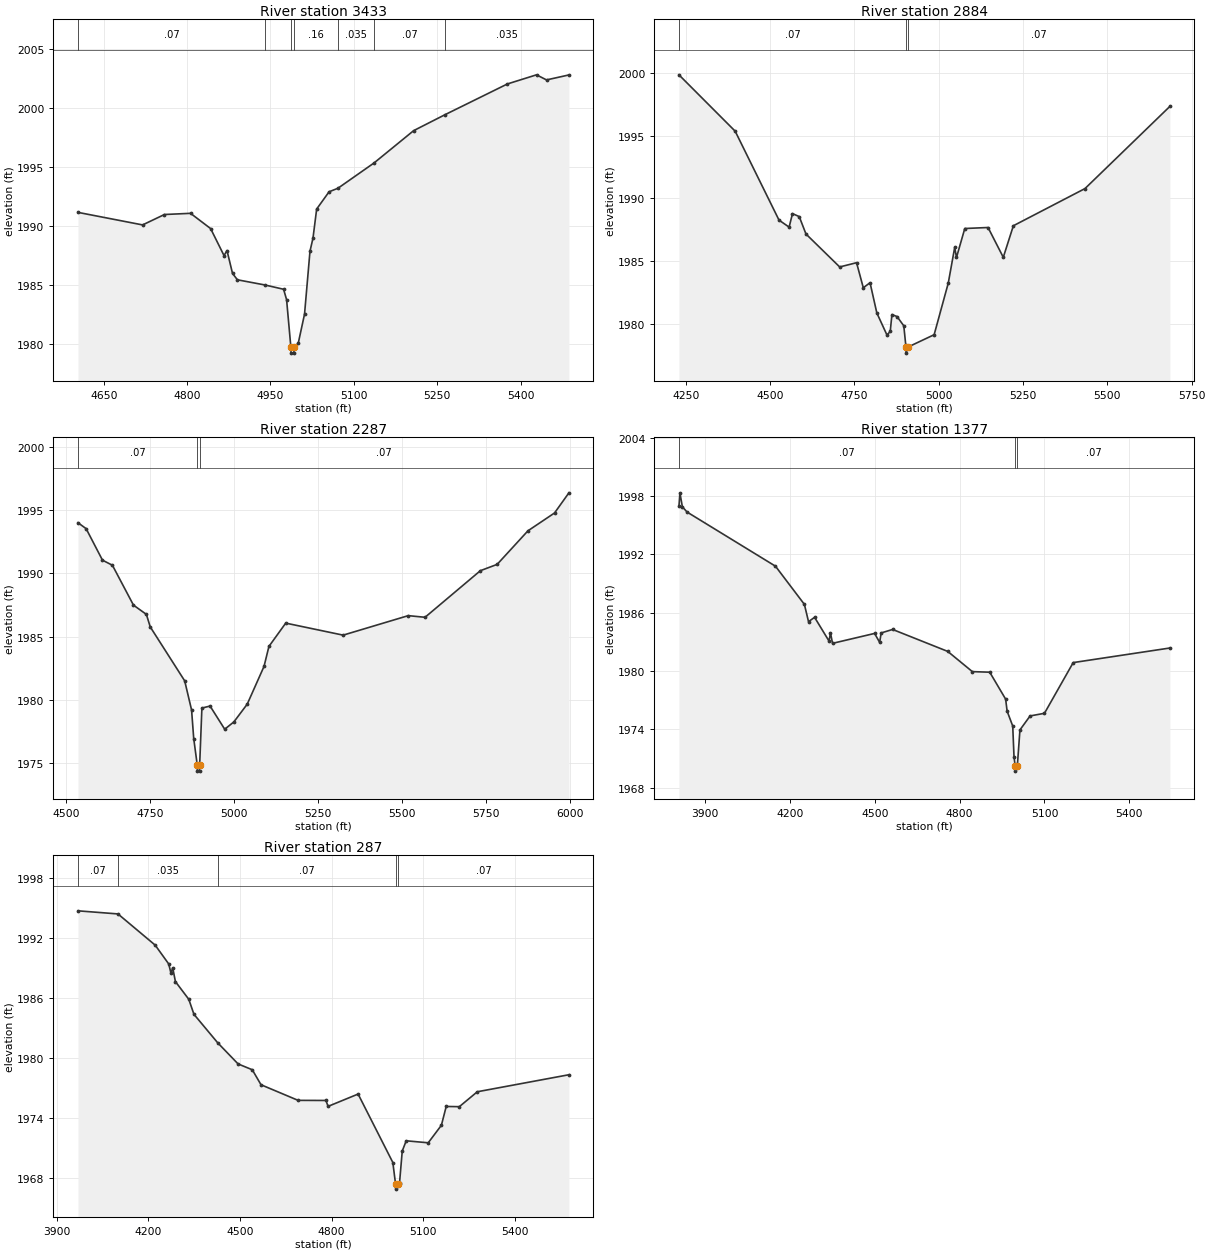
Type RM Length L Ch R = 1,3433,549,549,549
BEGIN DESCRIPTION:
East China Creek Trib1 4.0
END DESCRIPTION:
XS GIS Cut Line= 3
      1419237.26      6907502.04      1419604.64      6907353.15
      1420051.15      6907158.75
#Sta/Elev= 30
  4603.6 1991.16  4719.9 1990.10  4759.2 1990.98  4806.2 1991.08  4842.3 1989.79
  4866.4 1987.51  4871.8 1987.93  4881.7 1986.00  4890.5 1985.46  4940.3 1985.02
  4973.6 1984.66  4979.0 1983.78  4986.7 1979.76  4987.2 1979.26  4992.1 1979.26
  4992.5 1979.76  5000.0 1980.10  5011.3 1982.56  5021.1 1987.88  5026.5 1988.98
  5033.1 1991.44  5055.4 1992.90  5071.4 1993.20  5136.4 1995.34  5207.6 1998.07
  5264.5 1999.43  5376.4 2002.02  5428.7 2002.79  5446.7 2002.36  5487.0 2002.78
#Mann=7,-1,0
  4603.6    0.07       0  4940.3    0.16       0  4986.7    0.07       0
  4992.5    0.16       0  5071.4   0.035       0  5136.4    0.07       0
  5264.5   0.035       0
Bank Sta=4986.7,4992.5
Exp/Cntr=0.3,0.1

Type RM Length L Ch R = 1,2884,597,597,597
BEGIN DESCRIPTION:
East China Creek Trib1 3.0
END DESCRIPTION:
XS GIS Cut Line= 4
      1418698.20      6907861.35      1419468.83      6907851.16
      1419724.23      6907751.98      1419990.56      6907438.39
#Sta/Elev= 30
  4229.3 1999.86  4396.1 1995.36  4526.1 1988.26  4556.1 1987.70  4566.1 1988.78
  4586.1 1988.54  4606.1 1987.15  4706.1 1984.52  4756.1 1984.86  4776.1 1982.86
  4796.1 1983.26  4816.2 1980.85  4846.2 1979.09  4856.0 1979.37  4861.0 1980.72
  4876.2 1980.56  4896.2 1979.82  4902.6 1978.14  4903.1 1977.64  4909.8 1978.14
  4986.2 1979.11  5028.1 1983.23  5047.2 1986.08  5052.5 1985.28  5077.1 1987.59
  5146.1 1987.67  5191.3 1985.29  5221.2 1987.81  5433.7 1990.78  5685.4 1997.34
#Mann=3,-1,0
  4229.3    0.07       0  4902.6    0.07       0  4909.8    0.07       0
Bank Sta=4902.6,4909.8
Exp/Cntr=0.3,0.1

Type RM Length L Ch R = 1,2287,910,910,910
BEGIN DESCRIPTION:
East China Creek Trib1 2.0
END DESCRIPTION:
XS GIS Cut Line= 3
      1419004.98      6908438.00      1419455.00      6908338.00
      1420055.00      6907538.00
#Sta/Elev= 30
  4534.9 1993.99  4559.2 1993.52  4607.9 1991.03  4637.4 1990.63  4700.1 1987.48
  4738.5 1986.75  4750.0 1985.76  4852.5 1981.50  4873.0 1979.20  4879.4 1976.94
  4889.8 1974.87  4890.3 1974.37  4896.6 1974.37  4897.1 1974.87  4903.7 1979.35
  4928.0 1979.51  4971.6 1977.68  4999.0 1978.26  5038.6 1979.66  5088.6 1982.64
  5103.2 1984.22  5153.2 1986.06  5324.0 1985.11  5517.8 1986.65  5567.8 1986.52
  5732.4 1990.20  5782.4 1990.70  5874.0 1993.35  5953.2 1994.76  5995.9 1996.35
#Mann=3,-1,0
  4534.9    0.07       0  4889.8    0.07       0  4897.1    0.07       0
Bank Sta=4889.8,4897.1
Exp/Cntr=0.3,0.1

Type RM Length L Ch R = 1,1377,1090,1090,1090
BEGIN DESCRIPTION:
Mapping XS d15947f8
END DESCRIPTION:
XS GIS Cut Line= 4
      1418693.57      6909403.04      1419802.56      6909005.89
      1420034.76      6908847.47      1420069.42      6908572.40
#Sta/Elev= 30
  3807.2 1996.94  3810.7 1998.34  3819.3 1996.90  3836.1 1996.36  4148.6 1990.79
  4250.9 1986.86  4265.5 1985.08  4286.9 1985.53  4337.9 1983.09  4343.2 1983.92
  4350.4 1982.85  4499.1 1983.87  4517.1 1982.95  4522.4 1983.92  4562.9 1984.28
  4757.9 1982.02  4844.9 1979.94  4906.4 1979.88  4962.6 1977.11  4967.9 1975.87
  4987.7 1974.34  4992.2 1971.20  4996.5 1970.20  4997.0 1969.70  5003.9 1970.20
  5013.2 1973.94  5049.1 1975.38  5099.9 1975.65  5201.6 1980.87  5543.5 1982.37
#Mann=3,-1,0
  3807.2    0.07       0  4996.5    0.07       0  5003.9    0.07       0
Bank Sta=4996.5,5003.9
Exp/Cntr=0.3,0.1

Type RM Length L Ch R = 1,287,0,0,0
BEGIN DESCRIPTION:
Mapping XS 647b29e4
END DESCRIPTION:
XS GIS Cut Line= 3
      1419613.66      6910108.40      1420608.47      6909663.08
      1420349.16      6909214.47
#Sta/Elev= 30
  3969.4 1994.70  4100.4 1994.39  4222.4 1991.27  4266.7 1989.39  4274.2 1988.45
  4279.7 1989.01  4288.6 1987.63  4332.4 1985.86  4349.3 1984.36  4426.9 1981.52
  4493.9 1979.40  4540.3 1978.82  4569.0 1977.32  4690.5 1975.76  4781.6 1975.75
  4788.7 1975.16  4887.0 1976.39  5000.8 1969.55  5009.7 1967.39  5010.2 1966.89
  5018.1 1967.39  5022.7 1967.51  5031.6 1970.70  5044.6 1971.72  5116.7 1971.52
  5159.8 1973.27  5175.6 1975.15  5218.6 1975.13  5277.5 1976.62  5577.5 1978.32
#Mann=5,-1,0
  3969.4    0.07       0  4100.4   0.035       0  4426.9    0.07       0
  5009.7    0.07       0  5018.1    0.07       0
Bank Sta=5009.7,5018.1
Exp/Cntr=0.3,0.1

Chan Stop Cuts=-1