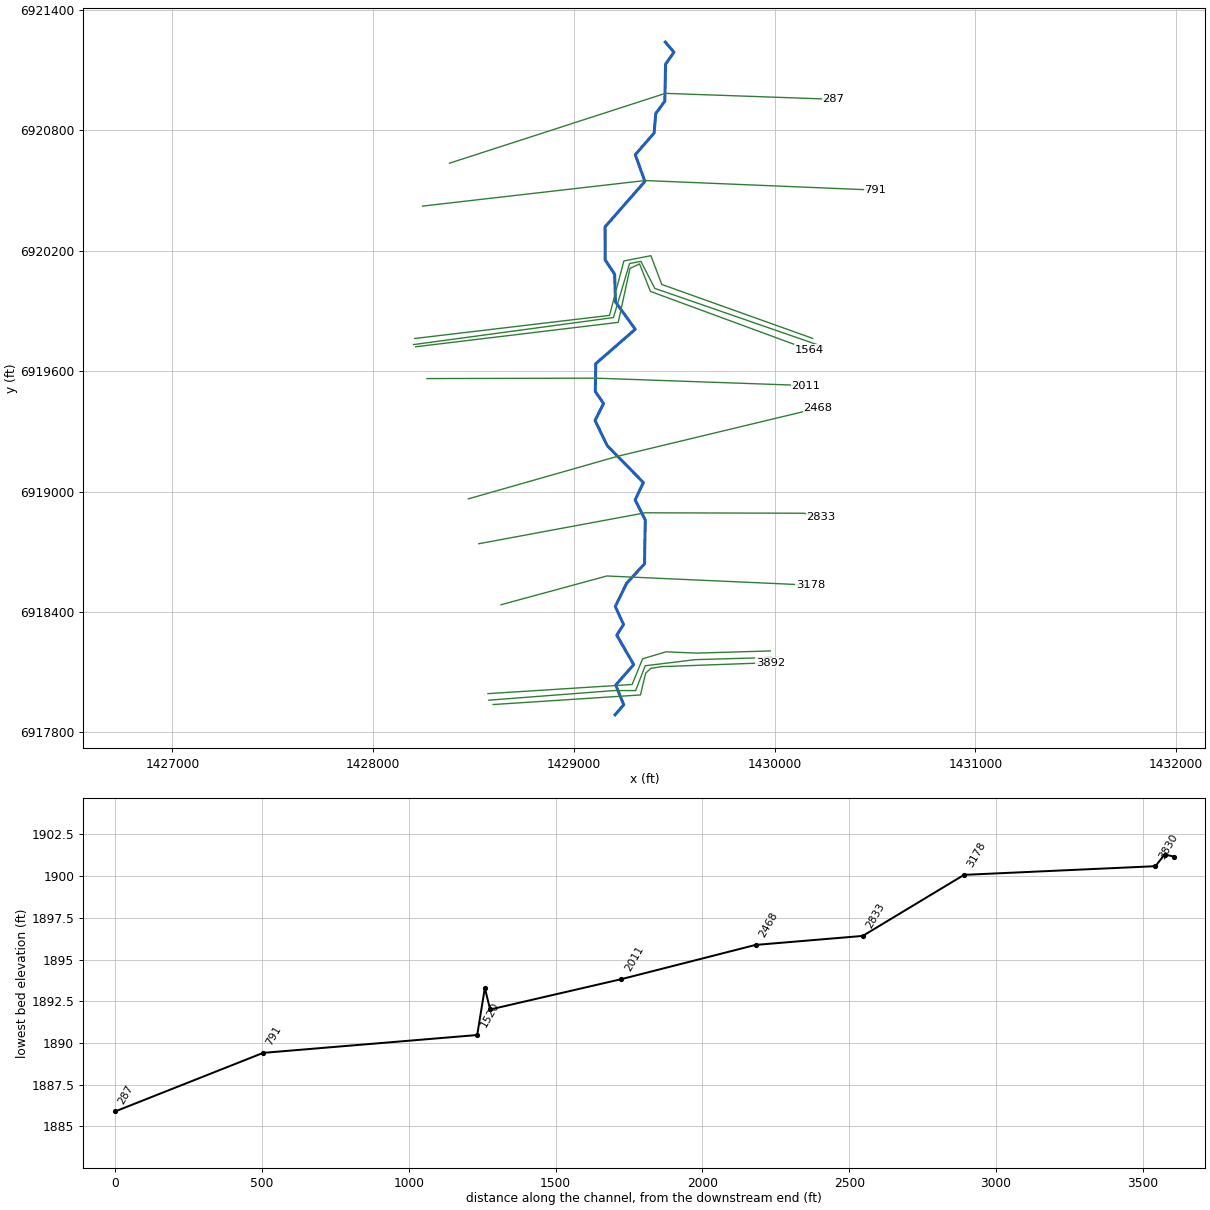
--- East China Creek Trib2.prj (project) ---

Proj Title=East China Creek Trib2 Base Level Engineering
Current Plan=p01
Default Exp/Contr=0.3,0.1
English Units
Geom File=g01
Flow File=f01
Plan File=p01
BEGIN DESCRIPTION:
East China Creek Trib2
END DESCRIPTION:

--- East China Creek Trib2.p01 (plan) ---

Plan Title=Multiple Run
Short Identifier=Multiple
Geom File=g01
Flow File=f01
Subcritical Flow
K Sum by GR= 0
Std Step Tol= 0.01
Critical Tol= 0.01
Num of Std Step Trials= 20
Max Error Tol= 0.3
Flow Tol Ratio= 0.001
Split Flow NTrial= 30
Split Flow Tol= 0.02
Split Flow Ratio= 0.02
Log Output Level= 0
Friction Slope Method= 1
Unsteady Friction Slope Method= 2
Unsteady Bridges Friction Slope Method= 1
Parabolic Critical Depth
Global Vel Dist=  1 , 1 , 1
Global Log Level= 0
CheckData=True
Encroach Param= -1, 0, 0, 0
BEGIN DESCRIPTION:
Multiple Run
END DESCRIPTION:

--- East China Creek Trib2.f01 (steady flow) ---

Flow Title=Multiple
Number of Profiles=7
Profile Names=10-year,25-year,50-year,1pct_min,100-year,1pct_plu,500-year
River Rch & RM= East China Creek,Reach-1,3892
     251     353     437     269     537    1071     822
River Rch & RM= East China Creek,Reach-1,2833
     318     451     563     350     697    1391    1083
Boundary for River Rch & Prof#=East China Creek,Reach-1,1
Up Type=0
Dn Type=3
Dn Slope=0.005
Boundary for River Rch & Prof#=East China Creek,Reach-1,2
Up Type=0
Dn Type=3
Dn Slope=0.005
Boundary for River Rch & Prof#=East China Creek,Reach-1,3
Up Type=0
Dn Type=3
Dn Slope=0.005
Boundary for River Rch & Prof#=East China Creek,Reach-1,4
Up Type=0
Dn Type=3
Dn Slope=0.005
Boundary for River Rch & Prof#=East China Creek,Reach-1,5
Up Type=0
Dn Type=3
Dn Slope=0.005
Boundary for River Rch & Prof#=East China Creek,Reach-1,6
Up Type=0
Dn Type=3
Dn Slope=0.005
Boundary for River Rch & Prof#=East China Creek,Reach-1,7
Up Type=0
Dn Type=3
Dn Slope=0.005

--- East China Creek Trib2.g01 (geometry) ---

Geom Title=Existing Conditions

River Reach=East China Creek,Reach-1
Reach XY= 30
      1429205.00      6917888.00      1429248.05      6917937.88
      1429208.17      6918036.36      1429297.70      6918137.92
      1429213.24      6918284.77      1429247.17      6918337.92
      1429205.79      6918427.30      1429263.16      6918544.05
      1429351.45      6918639.47      1429355.35      6918858.15
      1429304.79      6918958.21      1429345.85      6919044.73
      1429165.76      6919228.32      1429105.14      6919353.41
      1429147.41      6919437.99      1429106.37      6919498.44
      1429108.52      6919636.54      1429305.51      6919808.06
      1429207.08      6919943.86      1429202.73      6920082.06
      1429155.52      6920153.22      1429154.96      6920318.02
      1429353.38      6920544.04      1429305.61      6920677.37
      1429399.46      6920785.58      1429407.36      6920882.02
      1429452.74      6920943.94      1429456.31      6921127.58
      1429498.09      6921188.14      1429455.00      6921238.00

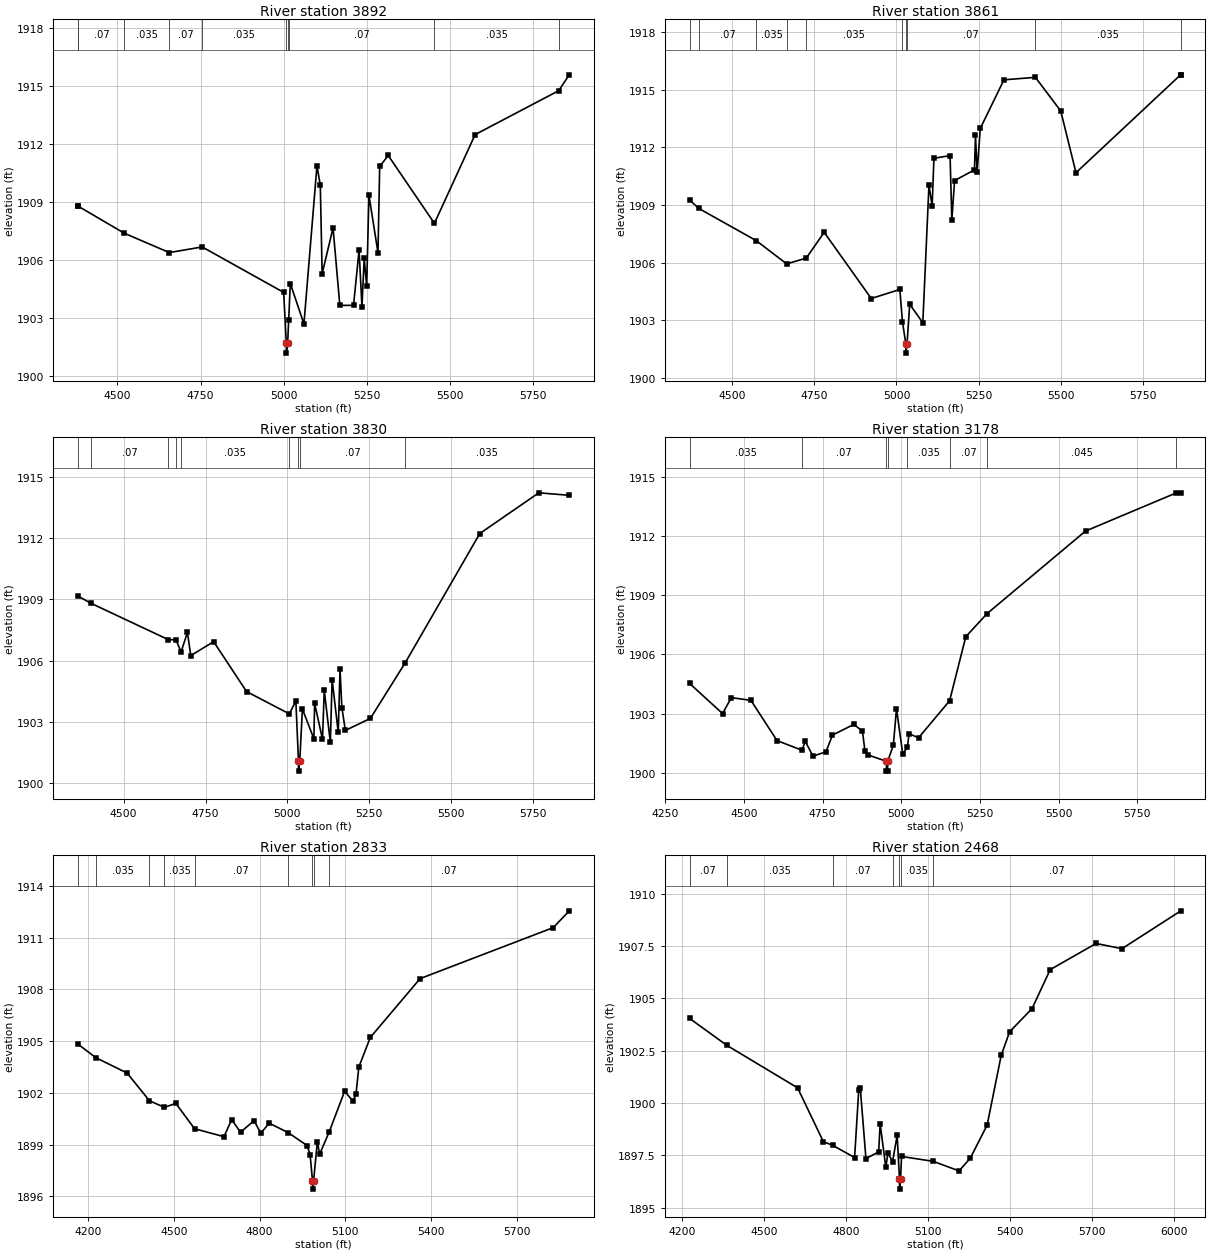
Type RM Length L Ch R = 1,3892,31,31,31
BEGIN DESCRIPTION:
Mapping XS 5460052b
END DESCRIPTION:
XS GIS Cut Line= 6
      1428597.74      6917939.12      1429331.22      6917986.86
      1429357.26      6918095.37      1429383.30      6918119.24
      1429437.56      6918127.92      1429977.91      6918147.45
#Sta/Elev= 30
  4381.5 1908.77  4382.9 1908.77  4520.7 1907.38  4656.1 1906.38  4755.1 1906.67
  5000.1 1904.32  5008.1 1901.68  5008.3 1901.18  5012.1 1901.68  5015.2 1902.88
  5020.1 1904.78  5061.1 1902.69  5100.3 1910.87  5110.3 1909.86  5115.9 1905.29
  5148.6 1907.65  5169.1 1903.65  5210.3 1903.65  5226.9 1906.51  5235.6 1903.59
  5242.4 1906.09  5249.8 1904.63  5256.6 1909.35  5283.8 1906.37  5288.9 1910.83
  5314.6 1911.40  5453.5 1907.89  5576.0 1912.48  5827.3 1914.75  5859.1 1915.57
#Mann=10,-1,0
  4381.5   0.035       0  4382.9    0.07       0  4520.7   0.035       0
  4656.1    0.07       0  4755.1   0.035       0  5008.1   0.035       0
  5012.1   0.035       0  5015.2    0.07       0  5453.5   0.035       0
  5827.3   0.045       0
Bank Sta=5008.1,5012.1
Exp/Cntr=0.3,0.1

Type RM Length L Ch R = 1,3861,31,31,31
BEGIN DESCRIPTION:
Mapping XS 2ab94918
END DESCRIPTION:
XS GIS Cut Line= 6
      1428576.01      6917960.82      1429198.84      6918008.56
      1429307.35      6918008.56      1429355.09      6918132.26
      1429604.66      6918162.64      1429984.44      6918173.49
#Sta/Elev= 30
  4369.5 1909.27  4396.9 1908.83  4572.6 1907.15  4665.4 1905.94  4725.0 1906.24
  4779.7 1907.58  4923.2 1904.14  5010.3 1904.61  5018.2 1902.94  5028.3 1901.80
  5028.6 1901.30  5032.3 1901.80  5040.3 1903.84  5080.3 1902.88  5099.0 1910.03
  5108.7 1908.95  5114.1 1911.43  5163.3 1911.57  5168.7 1908.23  5177.1 1910.27
  5237.7 1910.83  5240.8 1912.62  5245.8 1910.70  5255.3 1912.98  5327.5 1915.51
  5423.3 1915.64  5500.6 1913.89  5547.0 1910.68  5865.8 1915.77  5866.6 1915.77
#Mann=10,-1,0
  4369.5   0.035       0  4396.9    0.07       0  4572.6   0.035       0
  4665.4    0.07       0  4725.0   0.035       0  5018.2    0.07       0
  5028.3   0.035       0  5032.3    0.07       0  5423.3   0.035       0
  5865.8   0.045       0
Bank Sta=5028.3,5032.3
Exp/Cntr=0.3,0.1

Type RM Length L Ch R = 1,3830,652,652,652
BEGIN DESCRIPTION:
Mapping XS e2a634f9
END DESCRIPTION:
XS GIS Cut Line= 6
      1428571.70      6917993.37      1429289.99      6918038.94
      1429342.07      6918166.98      1429459.26      6918201.70
      1429609.00      6918195.19      1429977.90      6918206.04
#Sta/Elev= 30
  4360.8 1909.16  4401.6 1908.80  4636.6 1907.03  4660.0 1907.02  4675.3 1906.43
  4694.9 1907.38  4705.0 1906.25  4774.8 1906.93  4875.4 1904.49  5005.8 1903.40
  5025.7 1904.03  5033.7 1901.10  5034.0 1900.60  5037.7 1901.10  5045.7 1903.64
  5080.7 1902.18  5082.9 1903.92  5107.0 1902.16  5112.4 1904.55  5131.0 1902.01
  5136.4 1905.08  5155.1 1902.49  5160.5 1905.58  5166.1 1903.71  5176.8 1902.59
  5253.3 1903.18  5359.9 1905.91  5587.1 1912.22  5767.2 1914.21  5860.1 1914.09
#Mann=9,-1,0
  4360.8   0.035       0  4401.6    0.07       0  4636.6   0.035       0
  4660.0    0.07       0  4675.3   0.035       0  5005.8    0.07       0
  5033.7   0.035       0  5037.7    0.07       0  5359.9   0.035       0
Bank Sta=5033.7,5037.7
Exp/Cntr=0.3,0.1

Type RM Length L Ch R = 1,3178,345,345,345
BEGIN DESCRIPTION:
Mapping XS 5eb6a807
END DESCRIPTION:
XS GIS Cut Line= 3
      1428636.82      6918436.09      1429164.12      6918579.31
      1430177.59      6918533.74
#Sta/Elev= 30
  4327.3 1904.53  4432.1 1903.00  4460.1 1903.81  4522.3 1903.67  4605.2 1901.63
  4684.3 1901.14  4695.1 1901.59  4719.2 1900.84  4760.6 1901.06  4781.4 1901.91
  4849.2 1902.45  4876.6 1902.11  4884.6 1901.09  4894.6 1900.90  4952.7 1900.58
  4952.9 1900.08  4956.4 1900.08  4956.7 1900.58  4974.7 1901.39  4984.7 1903.24
  5004.7 1900.94  5019.4 1901.30  5024.7 1901.98  5054.8 1901.77  5153.5 1903.65
  5204.9 1906.90  5272.4 1908.07  5585.3 1912.26  5872.7 1914.19  5888.2 1914.20
#Mann=8,-1,0
  4327.3   0.035       0  4684.3    0.07       0  4952.7    0.07       0
  4956.7    0.07       0  5019.4   0.035       0  5153.5    0.07       0
  5272.4   0.045       0  5872.7   0.035       0
Bank Sta=4952.7,4956.7
Exp/Cntr=0.3,0.1

Type RM Length L Ch R = 1,2833,365,365,365
BEGIN DESCRIPTION:
Mapping XS 584147fc
END DESCRIPTION:
XS GIS Cut Line= 5
      1428526.13      6918739.90      1429355.09      6918893.98
      1430138.51      6918891.81      1430145.02      6918891.81
      1430229.32      6918872.84
#Sta/Elev= 30
  4164.3 1904.82  4227.7 1904.03  4336.1 1903.15  4414.6 1901.54  4466.7 1901.16
  4506.7 1901.39  4572.3 1899.92  4675.3 1899.46  4702.2 1900.45  4733.2 1899.72
  4780.9 1900.39  4803.9 1899.66  4833.7 1900.24  4899.5 1899.70  4966.7 1898.94
  4976.9 1898.39  4985.0 1896.92  4985.3 1896.42  4989.0 1896.92  5002.2 1899.18
  5009.9 1898.44  5043.2 1899.72  5097.4 1902.09  5127.4 1901.51  5137.4 1901.94
  5147.4 1903.50  5187.4 1905.21  5361.6 1908.62  5828.1 1911.58  5883.8 1912.55
#Mann=9,-1,0
  4164.3    0.07       0  4227.7   0.035       0  4414.6    0.07       0
  4466.7   0.035       0  4572.3    0.07       0  4899.5   0.035       0
  4985.0   0.035       0  4989.0   0.035       0  5043.2    0.07       0
Bank Sta=4985,4989
Exp/Cntr=0.3,0.1

Type RM Length L Ch R = 1,2468,457,457,457
BEGIN DESCRIPTION:
Mapping XS 954cd62a
END DESCRIPTION:
XS GIS Cut Line= 3
      1428474.06      6918963.44      1429220.54      6919176.10
      1430214.49      6919414.82
#Sta/Elev= 30
  4226.9 1904.04  4363.4 1902.75  4622.3 1900.72  4716.6 1898.15  4751.2 1897.97
  4831.0 1897.39  4846.2 1900.62  4851.8 1900.71  4872.5 1897.34  4919.1 1897.66
  4924.5 1899.00  4945.3 1896.92  4952.9 1897.60  4970.1 1897.20  4986.8 1898.45
  4995.3 1896.38  4995.6 1895.88  4999.3 1896.38  5002.8 1897.44  5118.5 1897.21
  5213.4 1896.75  5254.5 1897.36  5316.2 1898.94  5367.6 1902.27  5398.5 1903.40
  5480.7 1904.51  5547.0 1906.37  5715.0 1907.62  5809.8 1907.37  6025.3 1909.18
#Mann=7,-1,0
  4226.9    0.07       0  4363.4   0.035       0  4751.2    0.07       0
  4970.1   0.035       0  4995.3   0.035       0  4999.3   0.035       0
  5118.5    0.07       0
Bank Sta=4995.3,4999.3
Exp/Cntr=0.3,0.1

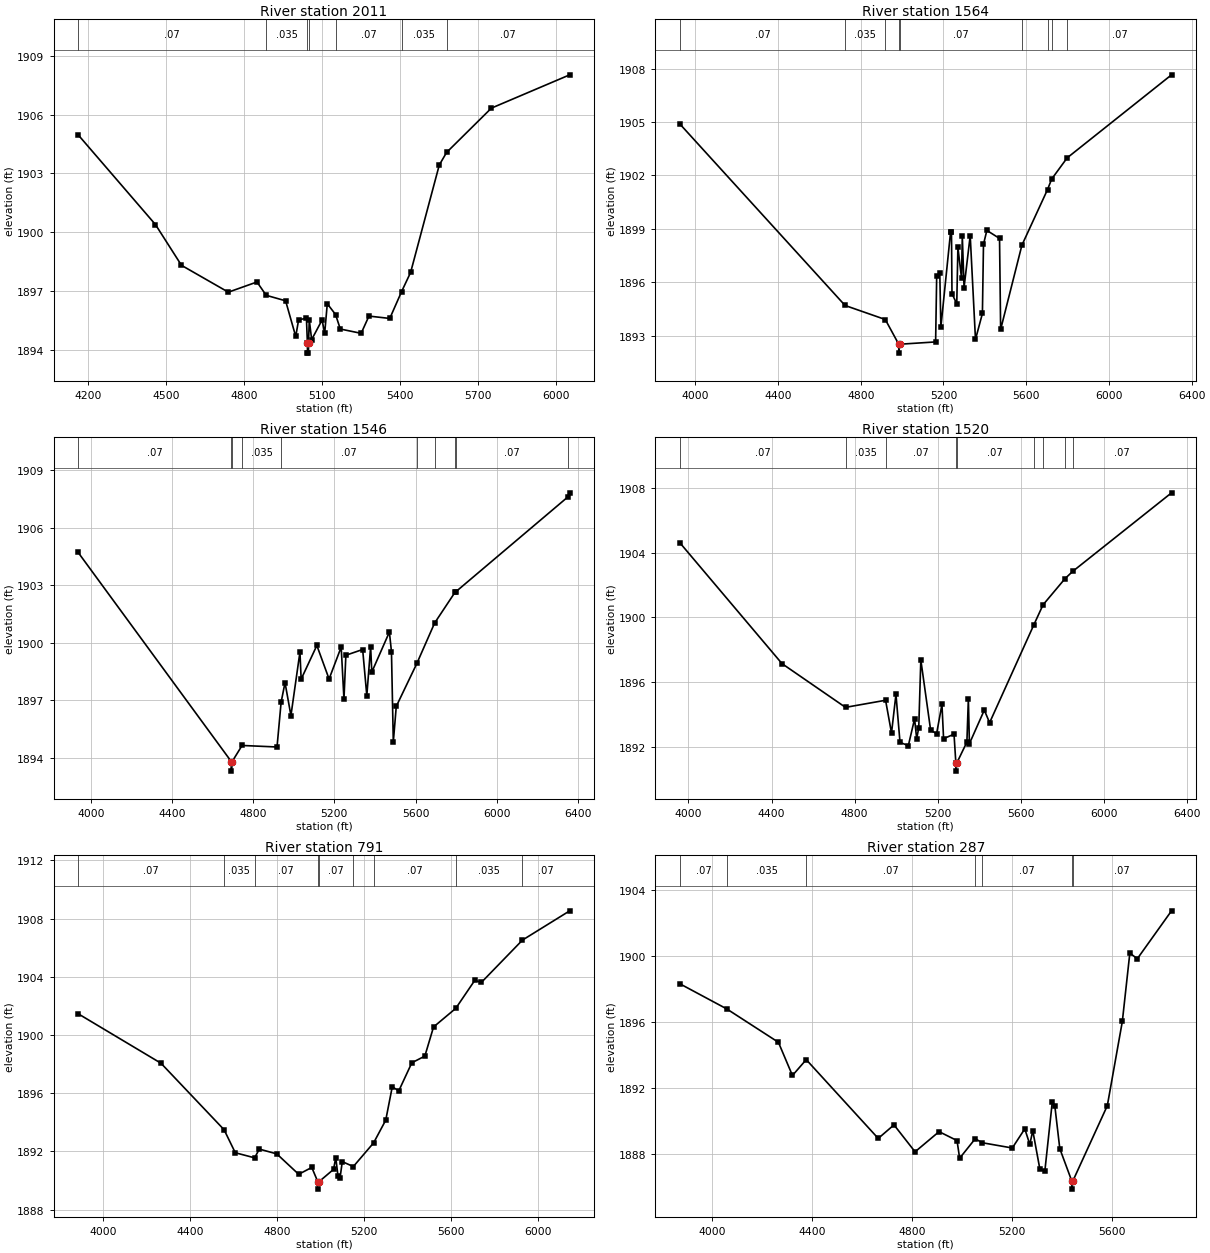
Type RM Length L Ch R = 1,2011,447,447,447
BEGIN DESCRIPTION:
Mapping XS 335b44a8
END DESCRIPTION:
XS GIS Cut Line= 3
      1428267.89      6919562.38      1429107.69      6919564.55
      1430155.83      6919527.66
#Sta/Elev= 30
  4163.3 1904.97  4460.4 1900.39  4560.4 1898.31  4740.4 1896.94  4850.4 1897.46
  4885.9 1896.78  4960.4 1896.50  4999.3 1894.68  5010.4 1895.53  5040.4 1895.61
  5044.2 1894.33  5044.5 1893.83  5048.2 1893.83  5048.5 1894.33  5051.3 1895.53
  5060.5 1894.52  5100.5 1895.52  5110.5 1894.84  5120.5 1896.35  5152.3 1895.80
  5170.5 1895.06  5250.6 1894.84  5280.6 1895.72  5360.6 1895.60  5406.0 1896.97
  5440.7 1897.95  5550.8 1903.43  5578.9 1904.07  5750.9 1906.33  6051.9 1908.03
#Mann=7,-1,0
  4163.3    0.07       0  4885.9   0.035       0  5044.2   0.035       0
  5048.5   0.035       0  5152.3    0.07       0  5406.0   0.035       0
  5578.9    0.07       0
Bank Sta=5044.2,5048.5
Exp/Cntr=0.3,0.1

Type RM Length L Ch R = 1,1564,18,18,18
BEGIN DESCRIPTION:
Mapping XS 41408d59
END DESCRIPTION:
XS GIS Cut Line= 6
      1428211.41      6919720.80      1429220.54      6919842.33
      1429279.14      6920111.43      1429326.88      6920133.13
      1429381.13      6919996.41      1430170.52      6919705.81
#Sta/Elev= 30
  3926.1 1904.89  4724.4 1894.69  4918.9 1893.90  4983.9 1892.51  4984.2 1892.01
  4988.3 1892.51  5162.2 1892.64  5167.3 1896.32  5182.4 1896.50  5187.5 1893.46
  5234.7 1898.84  5238.9 1898.84  5241.3 1895.36  5264.4 1894.78  5269.9 1897.96
  5287.4 1896.23  5291.2 1898.60  5299.6 1895.70  5329.4 1898.62  5354.9 1892.78
  5388.4 1894.24  5393.6 1898.13  5409.9 1898.91  5471.2 1898.46  5476.5 1893.34
  5579.3 1898.08  5703.3 1901.21  5723.3 1901.80  5798.1 1902.99  6302.7 1907.66
#Mann=9,-1,0
  3926.1    0.07       0  4724.4   0.035       0  4918.9    0.07       0
  4983.9    0.07       0  4988.3    0.07       0  5579.3   0.035       0
  5703.3    0.07       0  5723.3   0.035       0  5798.1    0.07       0
Bank Sta=4983.9,4988.3
Exp/Cntr=0.3,0.1

Type RM Length L Ch R = 1,1546,26,26,26
BEGIN DESCRIPTION:
Mapping XS 432d95d7
END DESCRIPTION:
XS GIS Cut Line= 6
      1428200.54      6919731.65      1429196.67      6919866.20
      1429276.97      6920135.30      1429333.39      6920146.15
      1429402.83      6920011.60      1430236.14      6919722.98
#Sta/Elev= 30
  3937.8 1904.72  4692.3 1893.80  4692.6 1893.30  4696.7 1893.80  4745.4 1894.64
  4917.6 1894.56  4937.8 1896.90  4957.0 1897.92  4986.1 1896.20  5030.5 1899.52
  5036.4 1898.10  5113.8 1899.86  5174.0 1898.11  5233.7 1899.78  5247.3 1897.05
  5256.7 1899.35  5339.4 1899.65  5359.9 1897.24  5378.7 1899.80  5384.4 1898.47
  5471.1 1900.56  5481.3 1899.54  5490.4 1894.82  5505.0 1896.68  5606.3 1898.92
  5693.8 1901.03  5793.9 1902.63  5798.9 1902.67  6350.8 1907.62  6359.4 1907.83
#Mann=10,-1,0
  3937.8    0.07       0  4692.3    0.07       0  4696.7    0.07       0
  4745.4   0.035       0  4937.8    0.07       0  5606.3   0.035       0
  5693.8    0.07       0  5793.9   0.035       0  5798.9    0.07       0
  6350.8   0.045       0
Bank Sta=4692.3,4696.7
Exp/Cntr=0.3,0.1

Type RM Length L Ch R = 1,1520,729,729,729
BEGIN DESCRIPTION:
Mapping XS 248798bb
END DESCRIPTION:
XS GIS Cut Line= 6
      1428207.13      6919762.04      1429177.14      6919877.05
      1429248.75      6920148.32      1429383.30      6920174.36
      1429437.56      6920031.13      1430188.97      6919762.61
#Sta/Elev= 30
  3958.9 1904.62  4450.2 1897.14  4756.0 1894.43  4948.9 1894.87  4977.5 1892.84
  4998.9 1895.24  5018.4 1892.26  5058.5 1892.06  5088.6 1893.72  5098.6 1892.49
  5108.6 1893.16  5118.6 1897.37  5166.0 1893.00  5194.7 1892.81  5220.3 1894.61
  5228.2 1892.49  5278.4 1892.77  5287.3 1890.98  5287.6 1890.48  5291.7 1890.98
  5340.4 1892.28  5347.5 1894.97  5352.5 1892.18  5424.2 1894.26  5449.7 1893.48
  5661.9 1899.52  5706.9 1900.78  5813.2 1902.41  5850.4 1902.86  6325.6 1907.72
#Mann=9,-1,0
  3958.9    0.07       0  4756.0   0.035       0  4948.9    0.07       0
  5287.3    0.07       0  5291.7    0.07       0  5661.9   0.035       0
  5706.9    0.07       0  5813.2   0.035       0  5850.4    0.07       0
Bank Sta=5287.3,5291.7
Exp/Cntr=0.3,0.1

Type RM Length L Ch R = 1,791,504,504,504
BEGIN DESCRIPTION:
East China Creek Trib2 2.0
END DESCRIPTION:
XS GIS Cut Line= 3
      1428245.97      6920421.43      1429354.40      6920548.62
      1430501.51      6920501.07
#Sta/Elev= 30
  3884.3 1901.46  4265.8 1898.06  4556.5 1893.49  4608.0 1891.91  4697.0 1891.56
  4718.8 1892.16  4799.3 1891.83  4899.9 1890.43  4960.3 1890.90  4988.2 1889.91
  4988.5 1889.41  4992.8 1889.91  5060.7 1890.77  5070.7 1891.58  5080.7 1890.34
  5090.7 1890.20  5100.7 1891.30  5151.6 1890.96  5245.1 1892.59  5300.9 1894.15
  5330.9 1896.44  5360.9 1896.16  5421.0 1898.09  5481.0 1898.55  5521.0 1900.55
  5623.4 1901.83  5711.2 1903.76  5741.2 1903.61  5930.5 1906.52  6148.1 1908.53
#Mann=9,-1,0
  3884.3    0.07       0  4556.5   0.035       0  4697.0    0.07       0
  4988.2    0.07       0  4992.8    0.07       0  5151.6    0.16       0
  5245.1    0.07       0  5623.4   0.035       0  5930.5    0.07       0
Bank Sta=4988.2,4992.8
Exp/Cntr=0.3,0.1

Type RM Length L Ch R = 1,287,0,0,0
BEGIN DESCRIPTION:
East China Creek Trib2 1.0
END DESCRIPTION:
XS GIS Cut Line= 3
      1428379.98      6920634.99      1429455.43      6920982.82
      1430291.81      6920953.32
#Sta/Elev= 30
  3869.7 1898.33  4057.2 1896.81  4263.8 1894.79  4319.9 1892.78  4375.1 1893.74
  4663.2 1888.97  4726.3 1889.79  4810.6 1888.16  4906.7 1889.38  4978.5 1888.84
  4989.0 1887.77  5051.3 1888.95  5078.9 1888.71  5199.7 1888.39  5249.7 1889.55
  5269.7 1888.61  5281.7 1889.44  5309.8 1887.13  5329.8 1886.97  5359.8 1891.19
  5369.8 1890.95  5389.8 1888.35  5437.5 1886.40  5437.8 1885.90  5442.2 1886.40
  5579.9 1890.95  5640.0 1896.05  5670.0 1900.19  5700.0 1899.85  5836.9 1902.75
#Mann=7,-1,0
  3869.7    0.07       0  4057.2   0.035       0  4375.1    0.07       0
  5051.3    0.16       0  5078.9    0.07       0  5437.5    0.07       0
  5442.2    0.07       0
Bank Sta=5437.5,5442.2
Exp/Cntr=0.3,0.1

Chan Stop Cuts=-1