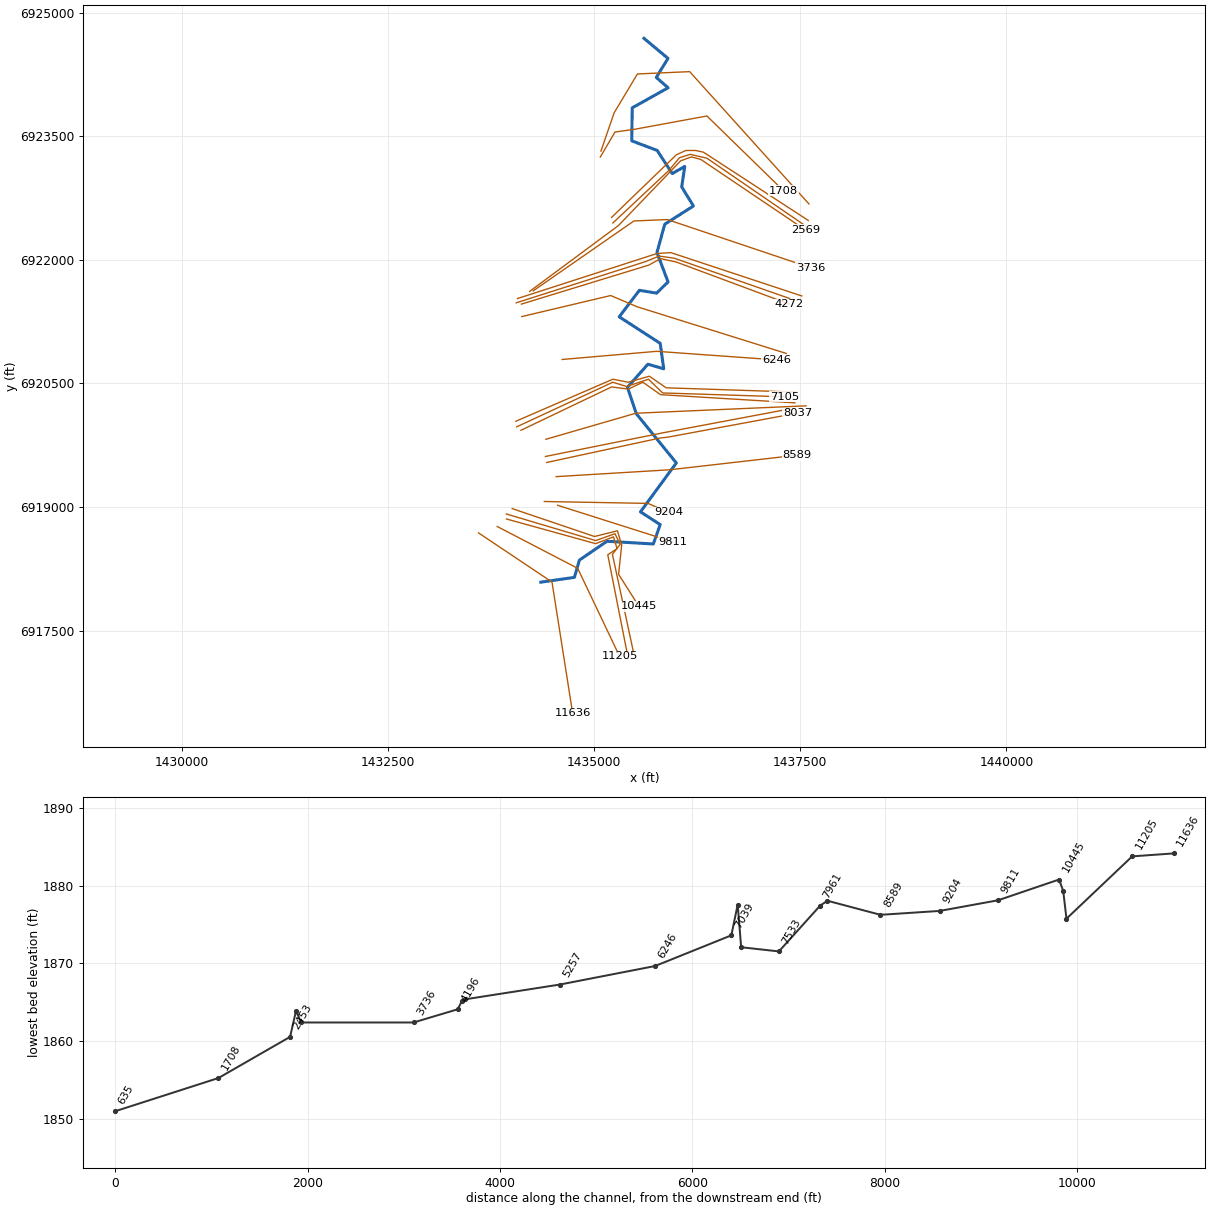
--- East China Creek Trib3.prj (project) ---

Proj Title=East China Creek Trib3 Base Level Engineering
Current Plan=p01
Default Exp/Contr=0.3,0.1
English Units
Geom File=g01
Flow File=f01
Plan File=p01
BEGIN DESCRIPTION:
East China Creek Trib3
END DESCRIPTION:

--- East China Creek Trib3.p01 (plan) ---

Plan Title=Multiple Run
Short Identifier=Multiple
Geom File=g01
Flow File=f01
Subcritical Flow
K Sum by GR= 0
Std Step Tol= 0.01
Critical Tol= 0.01
Num of Std Step Trials= 20
Max Error Tol= 0.3
Flow Tol Ratio= 0.001
Split Flow NTrial= 30
Split Flow Tol= 0.02
Split Flow Ratio= 0.02
Log Output Level= 0
Friction Slope Method= 1
Unsteady Friction Slope Method= 2
Unsteady Bridges Friction Slope Method= 1
Parabolic Critical Depth
Global Vel Dist=  1 , 1 , 1
Global Log Level= 0
CheckData=True
Encroach Param= -1, 0, 0, 0
BEGIN DESCRIPTION:
Multiple Run
END DESCRIPTION:

--- East China Creek Trib3.f01 (steady flow) ---

Flow Title=Multiple
Number of Profiles=7
Profile Names=10-year,25-year,50-year,1pct_min,100-year,1pct_plu,500-year
River Rch & RM= East China Creek,Reach-1,11636
     322     453     561     346     690    1376    1054
Boundary for River Rch & Prof#=East China Creek,Reach-1,1
Up Type=0
Dn Type=3
Dn Slope=0.005
Boundary for River Rch & Prof#=East China Creek,Reach-1,2
Up Type=0
Dn Type=3
Dn Slope=0.005
Boundary for River Rch & Prof#=East China Creek,Reach-1,3
Up Type=0
Dn Type=3
Dn Slope=0.005
Boundary for River Rch & Prof#=East China Creek,Reach-1,4
Up Type=0
Dn Type=3
Dn Slope=0.005
Boundary for River Rch & Prof#=East China Creek,Reach-1,5
Up Type=0
Dn Type=3
Dn Slope=0.005
Boundary for River Rch & Prof#=East China Creek,Reach-1,6
Up Type=0
Dn Type=3
Dn Slope=0.005
Boundary for River Rch & Prof#=East China Creek,Reach-1,7
Up Type=0
Dn Type=3
Dn Slope=0.005

--- East China Creek Trib3.g01 (geometry) ---

Geom Title=Existing Conditions

River Reach=East China Creek,Reach-1
Reach XY= 30
      1434355.00      6918088.00      1434761.50      6918145.72
      1434821.36      6918355.11      1435156.50      6918584.39
      1435718.66      6918551.19      1435801.64      6918786.75
      1435562.60      6918941.32      1435997.44      6919534.84
      1435512.62      6920131.50      1435404.84      6920453.24
      1435652.71      6920732.93      1435844.57      6920677.46
      1435801.84      6920986.35      1435304.78      6921308.05
      1435548.95      6921629.88      1435758.33      6921595.61
      1435897.19      6921731.81      1435762.30      6922088.08
      1435857.05      6922432.16      1436204.64      6922653.15
      1436062.69      6922884.33      1436099.82      6923133.44
      1435948.05      6923046.84      1435764.82      6923327.53
      1435456.62      6923444.03      1435462.69      6923844.48
      1435898.10      6924088.00      1435754.46      6924212.88
      1435896.17      6924445.00      1435605.00      6924688.00

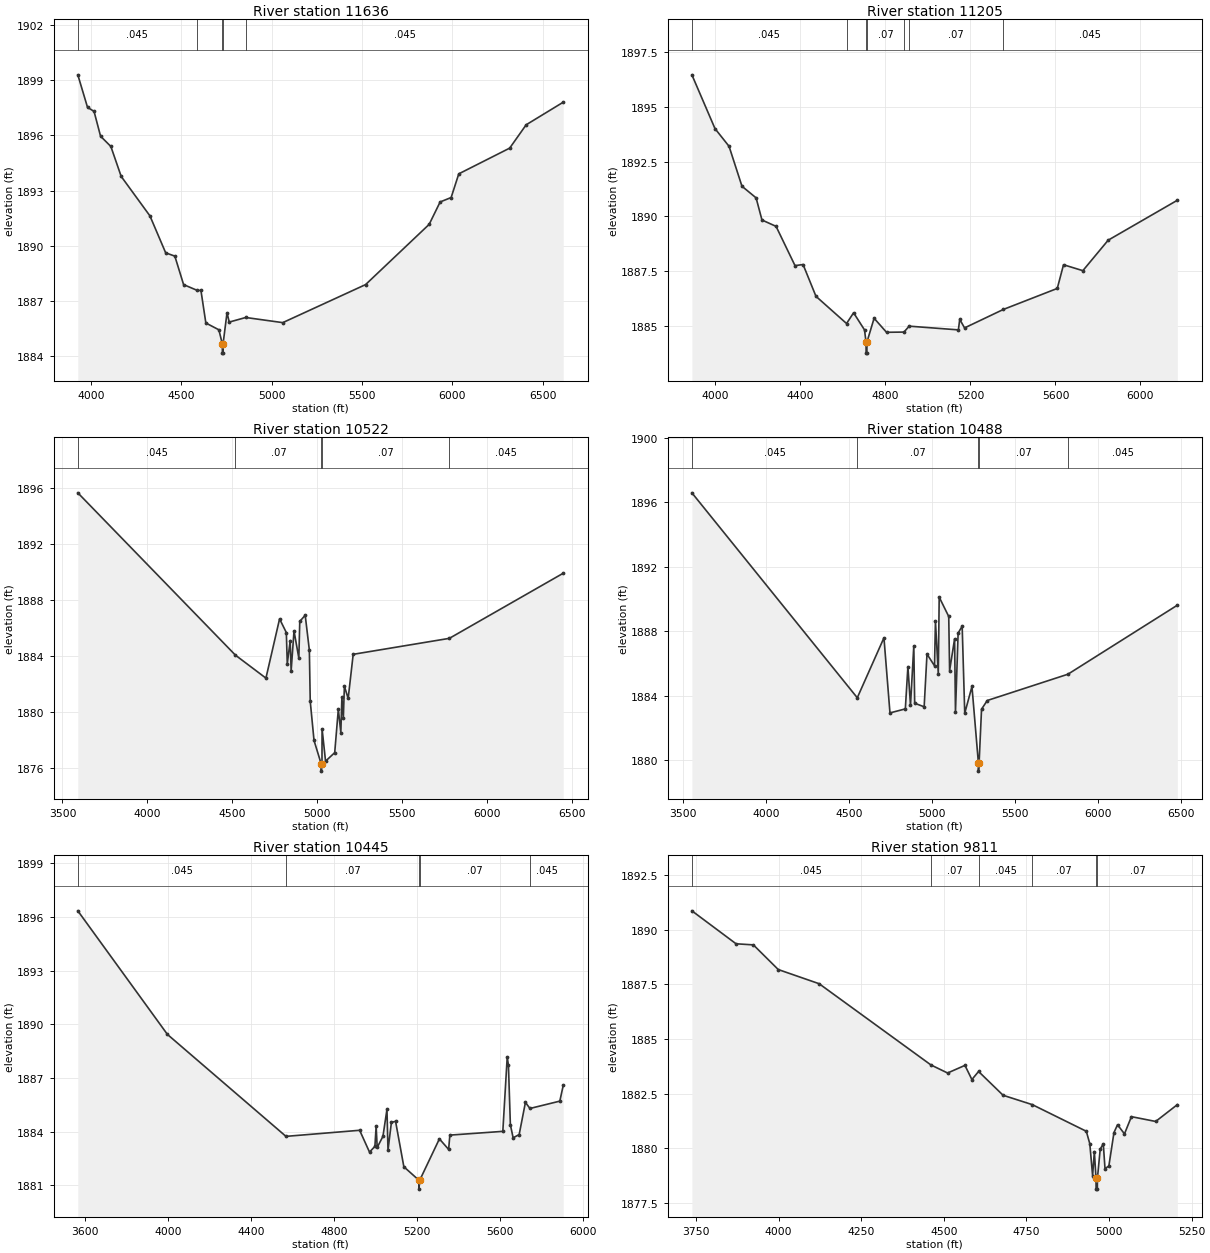
Type RM Length L Ch R = 1,11636,431,431,431
BEGIN DESCRIPTION:
East China Creek Trib3 10.0
END DESCRIPTION:
XS GIS Cut Line= 3
      1433599.10      6918685.42      1434489.65      6918089.02
      1434740.27      6916495.41
#Sta/Elev= 30
  3928.2 1899.30  3981.9 1897.53  4018.0 1897.31  4054.0 1895.96  4111.0 1895.40
  4168.1 1893.77  4327.2 1891.62  4414.2 1889.61  4464.9 1889.43  4513.3 1887.88
  4587.5 1887.57  4609.3 1887.56  4636.4 1885.79  4708.4 1885.42  4727.6 1884.65
  4727.9 1884.15  4731.4 1884.15  4731.6 1884.65  4753.5 1886.35  4765.7 1885.84
  4857.0 1886.09  5061.7 1885.81  5519.8 1887.88  5871.6 1891.16  5932.3 1892.38
  5993.1 1892.62  6035.4 1893.91  6317.0 1895.31  6408.1 1896.58  6613.2 1897.81
#Mann=5,-1,0
  3928.2   0.045       0  4587.5    0.07       0  4727.6   0.045       0
  4731.6    0.07       0  4857.0   0.045       0
Bank Sta=4727.6,4731.6
Exp/Cntr=0.3,0.1

Type RM Length L Ch R = 1,11205,683,683,683
BEGIN DESCRIPTION:
Mapping XS 7ad77122
END DESCRIPTION:
XS GIS Cut Line= 3
      1433824.74      6918763.58      1434801.32      6918255.76
      1435309.11      6917188.09
#Sta/Elev= 30
  3890.2 1896.46  3998.7 1894.01  4065.0 1893.20  4125.7 1891.38  4192.1 1890.85
  4219.8 1889.84  4286.1 1889.55  4375.2 1887.76  4413.1 1887.81  4473.8 1886.36
  4617.6 1885.12  4650.7 1885.61  4702.0 1884.83  4709.3 1884.27  4709.6 1883.77
  4713.2 1883.77  4713.4 1884.27  4747.1 1885.36  4805.5 1884.72  4887.6 1884.73
  4912.1 1885.00  5143.5 1884.83  5149.9 1885.31  5172.6 1884.92  5354.6 1885.76
  5608.6 1886.72  5638.0 1887.80  5728.9 1887.53  5848.0 1888.92  6173.2 1890.74
#Mann=7,-1,0
  3890.2   0.045       0  4617.6    0.07       0  4709.3    0.07       0
  4713.4    0.07       0  4887.6   0.045       0  4912.1    0.07       0
  5354.6   0.045       0
Bank Sta=4709.3,4713.4
Exp/Cntr=0.3,0.1

Type RM Length L Ch R = 1,10522,34,34,34
BEGIN DESCRIPTION:
Mapping XS e5eb5c29
END DESCRIPTION:
XS GIS Cut Line= 6
      1433937.60      6918854.72      1435018.33      6918555.24
      1435235.35      6918637.70      1435278.75      6918494.48
      1435165.90      6918420.69      1435399.98      6917232.96
#Sta/Elev= 30
  3590.6 1895.62  4518.6 1884.03  4698.2 1882.39  4778.5 1886.62  4818.3 1885.64
  4823.8 1883.41  4841.0 1885.07  4846.5 1882.90  4863.5 1885.76  4891.9 1883.82
  4897.4 1886.44  4929.4 1886.88  4953.8 1884.39  4959.0 1880.74  4981.3 1877.94
  5023.9 1876.25  5024.2 1875.75  5028.1 1876.25  5028.7 1878.77  5049.2 1876.46
  5103.1 1877.07  5124.4 1880.17  5139.2 1878.50  5145.3 1881.02  5153.9 1879.56
  5160.1 1881.81  5182.4 1880.94  5211.9 1884.09  5778.1 1885.23  6448.6 1889.88
#Mann=5,-1,0
  3590.6   0.045       0  4518.6    0.07       0  5023.9    0.07       0
  5028.1    0.07       0  5778.1   0.045       0
Bank Sta=5023.9,5028.1
Exp/Cntr=0.3,0.1

Type RM Length L Ch R = 1,10488,43,43,43
BEGIN DESCRIPTION:
Mapping XS fca2acf9
END DESCRIPTION:
XS GIS Cut Line= 6
      1433935.86      6918915.48      1435019.20      6918592.57
      1435253.58      6918675.90      1435316.08      6918545.69
      1435222.33      6918425.90      1435477.53      6917238.44
#Sta/Elev= 30
  3554.0 1896.59  4550.4 1883.88  4711.1 1887.60  4747.3 1882.94  4839.9 1883.19
  4855.4 1885.81  4871.0 1883.42  4890.9 1887.10  4896.2 1883.54  4953.3 1883.32
  4970.4 1886.59  5015.7 1885.86  5021.3 1888.64  5038.4 1885.37  5043.9 1890.12
  5101.4 1888.92  5106.6 1885.56  5136.7 1887.54  5141.9 1882.97  5157.9 1887.89
  5182.3 1888.32  5197.8 1882.92  5241.3 1884.58  5280.1 1879.83  5280.4 1879.33
  5284.3 1879.83  5299.0 1883.17  5333.4 1883.71  5819.4 1885.34  6478.5 1889.62
#Mann=5,-1,0
  3554.0   0.045       0  4550.4    0.07       0  5280.1    0.07       0
  5284.3    0.07       0  5819.4   0.045       0
Bank Sta=5280.1,5284.3
Exp/Cntr=0.3,0.1

Type RM Length L Ch R = 1,10445,634,634,634
BEGIN DESCRIPTION:
Mapping XS 1f2a6e2f
END DESCRIPTION:
XS GIS Cut Line= 6
      1434007.08      6918980.58      1435005.31      6918642.04
      1435283.09      6918711.49      1435335.18      6918537.88
      1435296.92      6918183.38      1435544.33      6917794.02
#Sta/Elev= 30
  3565.7 1896.35  3997.9 1889.44  4569.6 1883.74  4925.0 1884.08  4972.5 1882.86
  4998.6 1883.18  5004.5 1884.31  5009.6 1883.12  5037.3 1883.74  5056.7 1885.25
  5061.7 1882.96  5078.1 1884.52  5098.2 1884.58  5138.2 1882.04  5210.6 1881.29
  5210.8 1880.79  5214.8 1881.29  5309.6 1883.60  5354.1 1883.01  5360.1 1883.81
  5615.5 1884.02  5636.7 1888.18  5642.6 1887.71  5651.9 1884.39  5665.2 1883.66
  5694.3 1883.84  5724.5 1885.64  5746.4 1885.30  5890.3 1885.71  5906.9 1886.59
#Mann=5,-1,0
  3565.7   0.045       0  4569.6    0.07       0  5210.6    0.07       0
  5214.8    0.07       0  5746.4   0.045       0
Bank Sta=5210.6,5214.8
Exp/Cntr=0.3,0.1

Type RM Length L Ch R = 1,9811,607,607,607
BEGIN DESCRIPTION:
Mapping XS f78437ec
END DESCRIPTION:
XS GIS Cut Line= 3
      1434557.71      6919021.07      1435759.99      6918639.12
      1435957.44      6918576.63
#Sta/Elev= 30
  3737.9 1890.87  3871.5 1889.36  3923.9 1889.31  3999.2 1888.18  4122.9 1887.53
  4461.0 1883.81  4511.5 1883.44  4564.0 1883.79  4585.0 1883.14  4605.2 1883.51
  4679.4 1882.42  4767.9 1881.99  4931.2 1880.77  4941.7 1880.20  4950.2 1878.74
  4955.5 1879.84  4960.5 1878.62  4960.8 1878.12  4964.5 1878.12  4964.8 1878.62
  4973.2 1879.95  4982.5 1880.20  4987.7 1879.06  4999.4 1879.18  5014.8 1880.71
  5025.6 1881.07  5046.6 1880.65  5067.6 1881.44  5141.0 1881.22  5206.5 1881.99
#Mann=6,-1,0
  3737.9   0.045       0  4461.0    0.07       0  4605.2   0.045       0
  4767.9    0.07       0  4960.5    0.07       0  4964.8    0.07       0
Bank Sta=4960.5,4964.8
Exp/Cntr=0.3,0.1

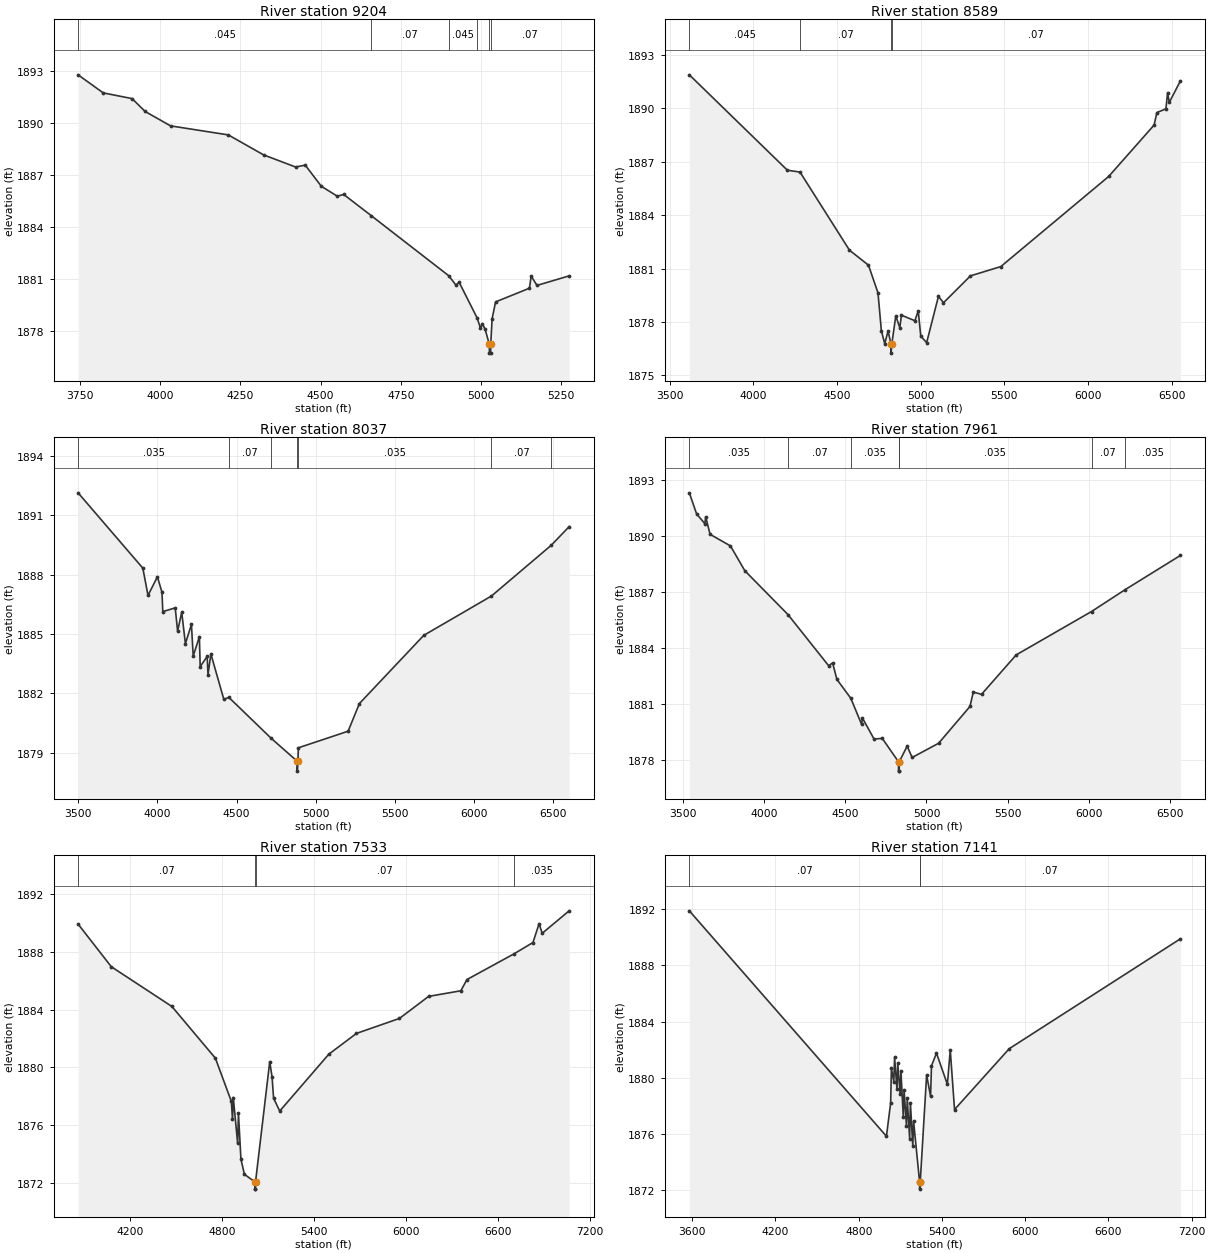
Type RM Length L Ch R = 1,9204,615,615,615
BEGIN DESCRIPTION:
East China Creek Trib3 8.0
END DESCRIPTION:
XS GIS Cut Line= 3
      1434396.62      6919066.73      1435652.91      6919043.86
      1435905.53      6918934.68
#Sta/Elev= 30
  3743.5 1892.78  3821.9 1891.74  3911.9 1891.41  3952.6 1890.67  4031.9 1889.84
  4212.0 1889.32  4322.0 1888.17  4422.0 1887.47  4452.0 1887.58  4502.3 1886.36
  4552.0 1885.79  4572.0 1885.89  4658.5 1884.66  4899.5 1881.21  4922.1 1880.67
  4932.1 1880.83  4988.1 1878.78  4998.5 1878.20  5004.9 1878.43  5013.2 1878.12
  5026.3 1877.25  5026.6 1876.75  5030.3 1876.75  5030.6 1877.25  5035.0 1878.74
  5045.8 1879.70  5151.4 1880.49  5156.8 1881.19  5174.9 1880.65  5275.2 1881.20
#Mann=6,-1,0
  3743.5   0.045       0  4658.5    0.07       0  4899.5   0.045       0
  4988.1    0.07       0  5026.3    0.07       0  5030.6    0.07       0
Bank Sta=5026.3,5030.6
Exp/Cntr=0.3,0.1

Type RM Length L Ch R = 1,8589,552,552,552
BEGIN DESCRIPTION:
Mapping XS b5574936
END DESCRIPTION:
XS GIS Cut Line= 3
      1434540.07      6919368.61      1435920.24      6919451.94
      1437460.92      6919628.91
#Sta/Elev= 30
  3618.4 1891.88  4204.4 1886.52  4279.3 1886.42  4575.1 1882.03  4688.6 1881.19
  4745.4 1879.63  4765.4 1877.52  4785.5 1876.78  4805.5 1877.49  4823.3 1876.75
  4823.6 1876.25  4827.7 1876.75  4851.7 1878.34  4875.6 1877.68  4885.6 1878.38
  4965.8 1878.07  4985.8 1878.62  5001.0 1877.20  5036.1 1876.84  5106.5 1879.44
  5136.7 1879.08  5297.8 1880.59  5479.0 1881.11  6123.2 1886.17  6395.0 1889.06
  6411.3 1889.76  6465.4 1889.97  6475.5 1890.88  6485.5 1890.33  6551.9 1891.54
#Mann=4,-1,0
  3618.4   0.045       0  4279.3    0.07       0  4823.3    0.07       0
  4827.7    0.07       0
Bank Sta=4823.3,4827.7
Exp/Cntr=0.3,0.1

Type RM Length L Ch R = 1,8037,76,76,76
BEGIN DESCRIPTION:
Mapping XS 44f013d1
END DESCRIPTION:
XS GIS Cut Line= 4
      1434425.43      6919540.48      1435800.45      6919837.36
      1435894.20      6919847.77      1437467.16      6920139.45
#Sta/Elev= 30
  3499.0 1892.14  3907.8 1888.33  3940.5 1886.95  3999.8 1887.89  4028.8 1887.11
  4033.9 1886.13  4112.4 1886.32  4127.3 1885.14  4153.3 1886.10  4176.6 1884.51
  4214.7 1885.48  4225.9 1883.88  4264.9 1884.86  4270.0 1883.35  4314.2 1883.86
  4319.3 1882.94  4337.5 1883.99  4419.3 1881.69  4451.2 1881.79  4717.2 1879.73
  4882.7 1878.56  4883.0 1878.06  4887.2 1878.56  4890.0 1879.24  5204.2 1880.08
  5275.4 1881.48  5682.0 1884.93  6109.4 1886.92  6487.2 1889.49  6599.8 1890.43
#Mann=7,-1,0
  3499.0   0.035       0  4451.2    0.07       0  4717.2   0.035       0
  4882.7   0.035       0  4887.2   0.035       0  6109.4    0.07       0
  6487.2   0.035       0
Bank Sta=4882.7,4887.2
Exp/Cntr=0.3,0.1

Type RM Length L Ch R = 1,7961,428,428,428
BEGIN DESCRIPTION:
Mapping XS 303b823e
END DESCRIPTION:
XS GIS Cut Line= 3
      1434409.87      6919613.41      1435831.70      6919899.86
      1437378.55      6920191.52
#Sta/Elev= 30
  3539.6 1892.31  3584.4 1891.18  3635.2 1890.66  3640.3 1891.03  3667.2 1890.09
  3792.7 1889.47  3881.5 1888.14  4146.7 1885.80  4397.5 1883.06  4422.1 1883.21
  4448.3 1882.33  4533.9 1881.32  4600.7 1879.92  4605.8 1880.26  4677.1 1879.14
  4728.1 1879.17  4827.9 1877.92  4828.2 1877.42  4832.0 1877.42  4832.4 1877.92
  4881.2 1878.76  4911.8 1878.15  5074.8 1878.91  5268.1 1880.88  5288.5 1881.65
  5339.3 1881.53  5553.0 1883.64  6016.8 1885.96  6222.1 1887.12  6564.1 1888.96
#Mann=7,-1,0
  3539.6   0.035       0  4146.7    0.07       0  4533.9   0.035       0
  4827.9   0.035       0  4832.4   0.035       0  6016.8    0.07       0
  6222.1   0.035       0
Bank Sta=4827.9,4832.4
Exp/Cntr=0.3,0.1

Type RM Length L Ch R = 1,7533,392,392,392
BEGIN DESCRIPTION:
East China Creek Trib3 5.0
END DESCRIPTION:
XS GIS Cut Line= 3
      1434415.05      6919821.73      1435505.00      6920138.00
      1437570.63      6920227.95
#Sta/Elev= 30
  3861.2 1889.94  4077.8 1886.98  4473.0 1884.22  4756.6 1880.63  4860.7 1877.63
  4868.2 1876.40  4873.4 1877.90  4901.8 1874.71  4907.0 1876.80  4923.2 1873.62
  4945.8 1872.57  5013.9 1872.04  5014.2 1871.54  5018.1 1871.54  5018.4 1872.04
  5111.1 1880.39  5126.2 1879.33  5136.2 1877.85  5176.3 1876.96  5496.6 1880.91
  5676.8 1882.35  5957.0 1883.39  6147.2 1884.92  6357.4 1885.31  6397.4 1886.09
  6705.2 1887.88  6827.8 1888.66  6867.9 1889.97  6887.9 1889.30  7063.7 1890.86
#Mann=4,-1,0
  3861.2    0.07       0  5013.9    0.07       0  5018.4    0.07       0
  6705.2   0.035       0
Bank Sta=5013.9,5018.4
Exp/Cntr=0.3,0.1

Type RM Length L Ch R = 1,7141,36,36,36
BEGIN DESCRIPTION:
Mapping XS 50fd4bd6
END DESCRIPTION:
XS GIS Cut Line= 6
      1434112.97      6919931.12      1435211.91      6920457.15
      1435415.04      6920431.11      1435592.12      6920514.44
      1435805.66      6920363.40      1437435.89      6920264.44
#Sta/Elev= 30
  3579.4 1891.87  5000.0 1875.84  5030.3 1878.21  5035.8 1880.66  5053.1 1879.72
  5058.6 1881.45  5075.9 1879.18  5081.4 1881.05  5098.7 1878.81  5104.2 1880.48
  5121.5 1877.22  5127.0 1879.14  5144.3 1876.56  5149.8 1878.54  5167.1 1875.68
  5172.6 1878.23  5189.9 1875.12  5195.4 1876.93  5239.0 1872.58  5239.3 1872.08
  5243.5 1872.58  5289.6 1880.20  5318.0 1878.68  5324.7 1880.85  5360.7 1881.75
  5439.1 1879.53  5459.9 1881.97  5490.8 1877.74  5885.4 1882.07  7118.6 1889.88
#Mann=3,-1,0
  3579.4    0.07       0  5239.0    0.07       0  5243.5    0.07       0
Bank Sta=5239,5243.5
Exp/Cntr=0.3,0.1

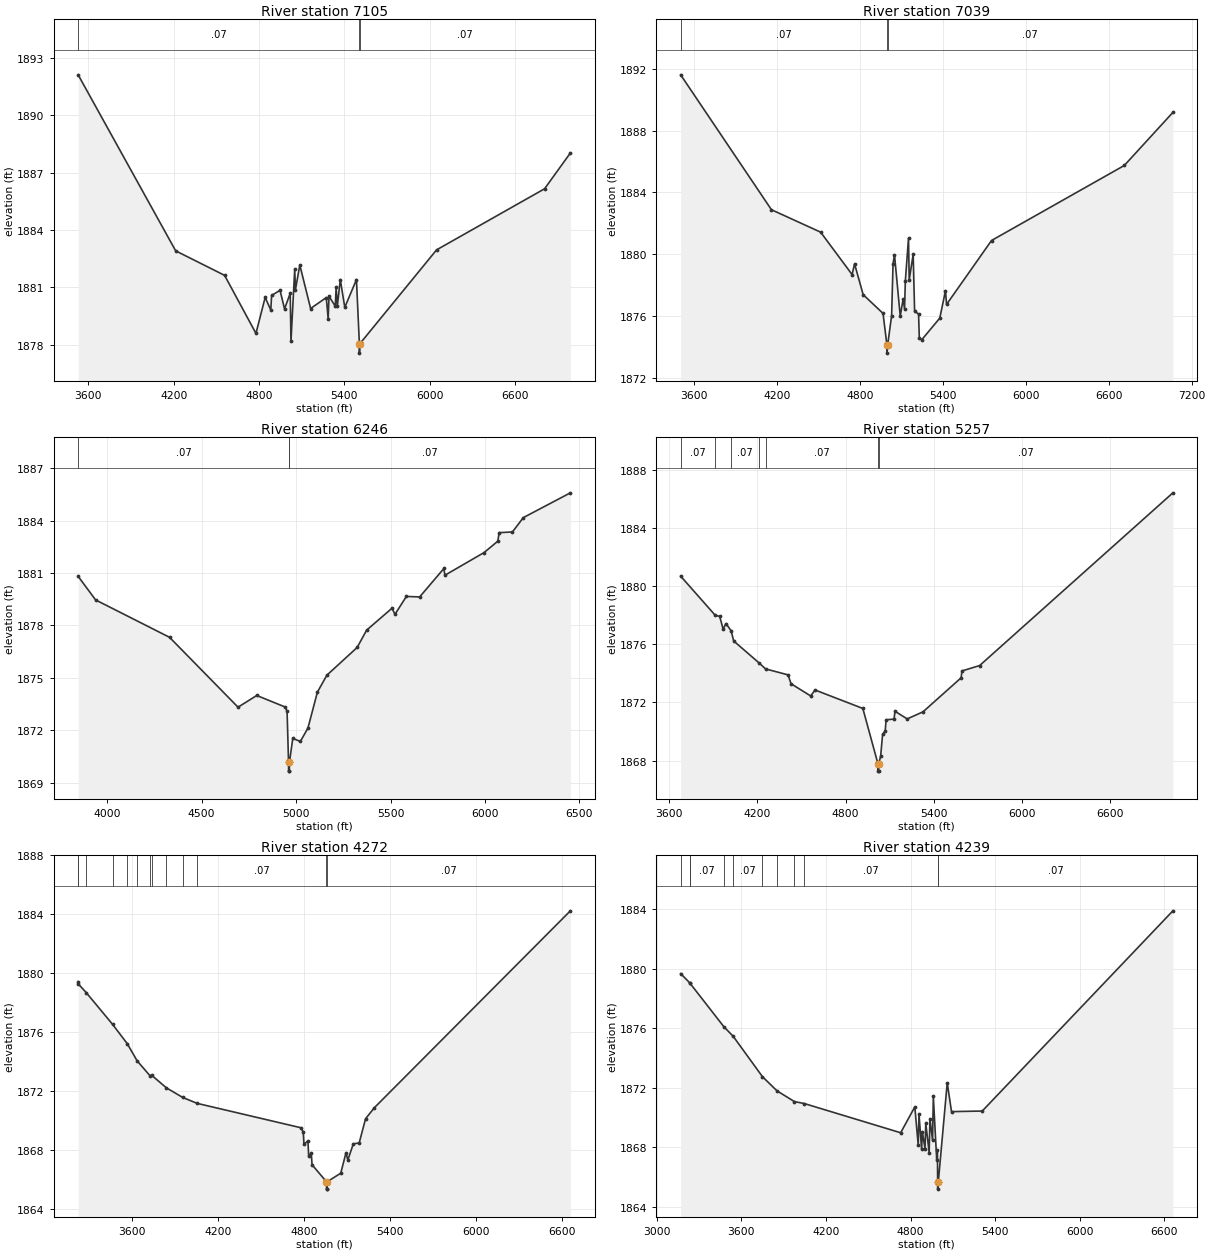
Type RM Length L Ch R = 1,7105,66,66,66
BEGIN DESCRIPTION:
Mapping XS 93163ee7
END DESCRIPTION:
XS GIS Cut Line= 6
      1434060.86      6919972.77      1435227.54      6920514.44
      1435394.20      6920462.36      1435659.83      6920550.90
      1435831.70      6920384.23      1437305.66      6920337.36
#Sta/Elev= 30
  3528.3 1892.10  4214.2 1882.91  4558.2 1881.63  4778.7 1878.60  4843.4 1880.48
  4883.2 1879.82  4888.5 1880.58  4948.1 1880.85  4979.6 1879.88  5019.6 1880.69
  5024.9 1878.19  5051.2 1881.94  5056.5 1880.89  5087.1 1882.17  5163.0 1879.90
  5273.4 1880.47  5286.4 1879.36  5292.6 1880.54  5336.4 1880.02  5342.6 1881.02
  5350.9 1880.03  5371.8 1881.41  5403.4 1879.96  5485.4 1881.41  5505.9 1878.07
  5506.2 1877.57  5510.4 1878.07  6048.7 1882.96  6808.2 1886.15  6989.8 1888.02
#Mann=3,-1,0
  3528.3    0.07       0  5505.9    0.07       0  5510.4    0.07       0
Bank Sta=5505.9,5510.4
Exp/Cntr=0.3,0.1

Type RM Length L Ch R = 1,7039,793,793,793
BEGIN DESCRIPTION:
Mapping XS 9ab22688
END DESCRIPTION:
XS GIS Cut Line= 6
      1434050.43      6920040.47      1435227.54      6920550.90
      1435415.04      6920514.44      1435670.24      6920587.36
      1435873.37      6920446.73      1437446.32      6920394.65
#Sta/Elev= 30
  3503.1 1891.60  4159.8 1882.88  4515.6 1881.43  4743.2 1878.69  4761.2 1879.38
  4823.3 1877.39  4966.9 1876.18  4995.6 1874.11  4995.9 1873.61  5000.1 1874.11
  5029.1 1876.03  5039.5 1879.39  5049.9 1879.97  5091.5 1876.00  5112.3 1877.11
  5122.7 1876.48  5128.3 1878.26  5151.3 1881.04  5156.5 1878.35  5185.1 1880.00
  5195.5 1876.31  5224.1 1876.14  5229.3 1874.62  5246.6 1874.47  5377.4 1875.87
  5418.8 1877.64  5426.8 1876.76  5751.8 1880.89  6712.3 1885.74  7063.8 1889.17
#Mann=3,-1,0
  3503.1    0.07       0  4995.6    0.07       0  5000.1    0.07       0
Bank Sta=4995.6,5000.1
Exp/Cntr=0.3,0.1

Type RM Length L Ch R = 1,6246,989,989,989
BEGIN DESCRIPTION:
Mapping XS 85ddd74a
END DESCRIPTION:
XS GIS Cut Line= 3
      1434612.95      6920790.48      1435758.79      6920889.44
      1437210.96      6920785.34
#Sta/Elev= 30
  3846.1 1880.81  3938.5 1879.46  4329.9 1877.32  4692.6 1873.32  4791.7 1873.99
  4942.2 1873.33  4952.3 1873.08  4960.0 1870.16  4960.3 1869.66  4964.2 1869.66
  4964.6 1870.16  4982.4 1871.53  5022.5 1871.36  5062.6 1872.12  5112.7 1874.18
  5162.8 1875.15  5323.3 1876.74  5373.4 1877.73  5507.3 1878.98  5523.8 1878.64
  5583.9 1879.66  5654.1 1879.63  5782.5 1881.26  5787.5 1880.87  5995.0 1882.17
  6067.7 1882.82  6075.2 1883.31  6145.4 1883.35  6202.8 1884.17  6452.1 1885.59
#Mann=3,-1,0
  3846.1    0.07       0  4960.0    0.07       0  4964.6    0.07       0
Bank Sta=4960,4964.6
Exp/Cntr=0.3,0.1

Type RM Length L Ch R = 1,5257,985,985,985
BEGIN DESCRIPTION:
Mapping XS 00713df0
END DESCRIPTION:
XS GIS Cut Line= 4
      1434123.41      6921311.32      1435201.49      6921566.52
      1435519.20      6921431.11      1437330.87      6920863.66
#Sta/Elev= 30
  3677.2 1880.69  3912.4 1878.00  3942.9 1877.92  3966.6 1877.04  3985.2 1877.43
  4020.6 1876.94  4038.5 1876.23  4213.6 1874.70  4255.4 1874.31  4408.5 1873.90
  4429.0 1873.29  4562.6 1872.45  4592.2 1872.86  4917.7 1871.59  5020.7 1867.78
  5021.1 1867.28  5025.2 1867.28  5025.5 1867.78  5038.9 1868.30  5052.2 1869.80
  5070.3 1870.05  5075.8 1870.81  5130.4 1870.86  5136.5 1871.40  5219.8 1870.87
  5327.6 1871.36  5587.1 1873.70  5592.4 1874.17  5712.9 1874.54  7028.9 1886.42
#Mann=7,-1,0
  3677.2    0.07       0  3912.4   0.035       0  4020.6    0.07       0
  4213.6   0.035       0  4255.4    0.07       0  5020.7    0.07       0
  5025.5    0.07       0
Bank Sta=5020.7,5025.5
Exp/Cntr=0.3,0.1

Type RM Length L Ch R = 1,4272,33,33,33
BEGIN DESCRIPTION:
Mapping XS 58fb615b
END DESCRIPTION:
XS GIS Cut Line= 5
      1434118.12      6921462.35      1435665.04      6921936.32
      1435805.66      6922014.44      1435998.37      6921972.77
      1437367.29      6921462.68
#Sta/Elev= 30
  3222.3 1879.44  3223.0 1879.29  3278.6 1878.70  3462.4 1876.55  3565.7 1875.23
  3633.6 1874.08  3723.4 1873.07  3736.3 1873.09  3839.0 1872.24  3952.9 1871.59
  4053.9 1871.19  4777.4 1869.54  4793.9 1869.25  4799.1 1868.41  4826.7 1868.65
  4831.9 1867.61  4849.9 1867.81  4855.6 1867.03  4956.1 1865.88  4956.5 1865.38
  4960.7 1865.38  4961.1 1865.88  5055.9 1866.46  5092.5 1867.85  5105.2 1867.35
  5143.6 1868.45  5184.5 1868.51  5229.1 1870.15  5290.7 1870.90  6659.1 1884.24
#Mann=13,-1,0
  3222.3    0.07       0  3223.0   0.035       0  3278.6    0.07       0
  3462.4   0.035       0  3565.7    0.07       0  3633.6   0.035       0
  3723.4    0.07       0  3736.3   0.035       0  3839.0    0.07       0
  3952.9   0.035       0  4053.9    0.07       0  4956.1    0.07       0
  4961.1    0.07       0
Bank Sta=4956.1,4961.1
Exp/Cntr=0.3,0.1

Type RM Length L Ch R = 1,4239,43,43,43
BEGIN DESCRIPTION:
Mapping XS 97dd0bc4
END DESCRIPTION:
XS GIS Cut Line= 5
      1434055.63      6921477.97      1435623.37      6921977.98
      1435790.04      6922045.69      1435972.33      6922019.65
      1437371.67      6921530.66
#Sta/Elev= 30
  3169.0 1879.68  3234.2 1879.05  3234.6 1879.04  3474.5 1876.12  3542.1 1875.46
  3749.2 1872.75  3852.2 1871.80  3975.1 1871.08  4047.4 1870.94  4729.7 1868.98
  4830.2 1870.72  4854.3 1868.14  4859.7 1870.24  4878.3 1867.87  4883.7 1869.03
  4902.4 1867.92  4907.8 1869.62  4931.9 1867.65  4937.3 1869.93  4956.0 1868.48
  4961.4 1871.42  4985.5 1867.16  4990.8 1867.79  4991.9 1865.69  4992.3 1865.19
  4996.9 1865.69  5060.1 1872.34  5090.4 1870.40  5308.5 1870.44  6660.9 1883.90
#Mann=11,-1,0
  3169.0    0.07       0  3234.2   0.035       0  3234.6    0.07       0
  3474.5   0.035       0  3542.1    0.07       0  3749.2   0.035       0
  3852.2    0.07       0  3975.1   0.035       0  4047.4    0.07       0
  4991.9    0.07       0  4996.9    0.07       0
Bank Sta=4991.9,4996.9
Exp/Cntr=0.3,0.1

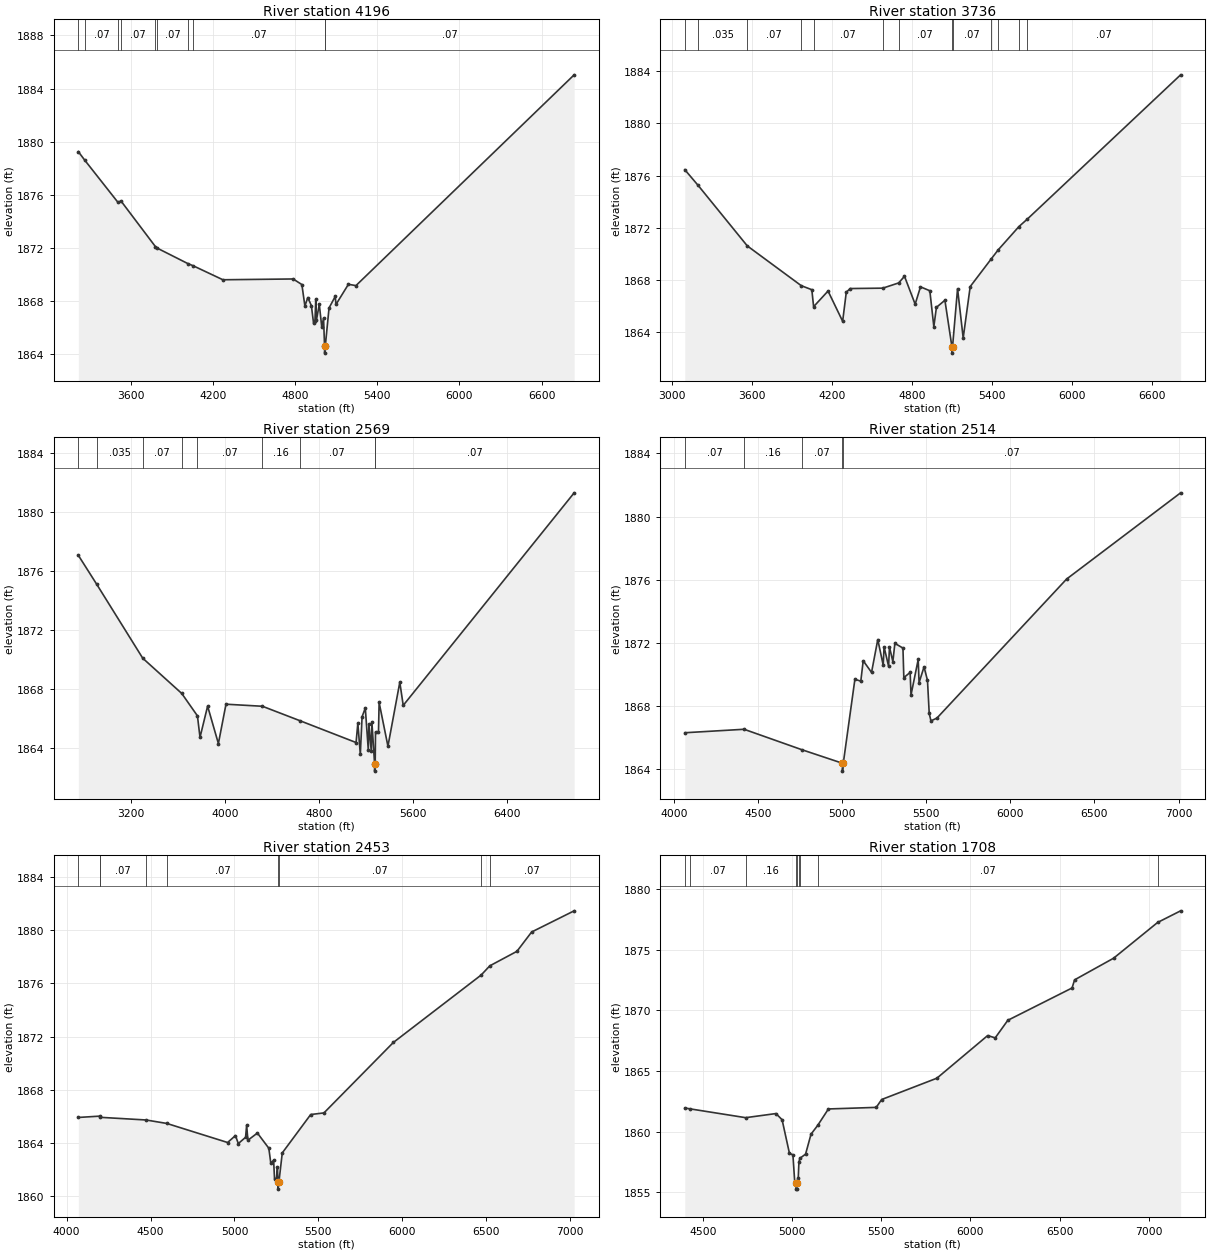
Type RM Length L Ch R = 1,4196,460,460,460
BEGIN DESCRIPTION:
Mapping XS b448af02
END DESCRIPTION:
XS GIS Cut Line= 4
      1434071.28      6921530.06      1435763.99      6922076.94
      1435930.66      6922087.36      1437519.17      6921561.33
#Sta/Elev= 30
  3218.1 1879.26  3265.5 1878.61  3506.2 1875.46  3530.0 1875.54  3781.1 1872.11
  3795.9 1871.99  4017.0 1870.84  4057.0 1870.67  4273.3 1869.62  4785.8 1869.68
  4849.8 1869.26  4871.9 1867.64  4892.9 1868.28  4919.1 1867.68  4935.0 1866.36
  4945.5 1866.55  4951.2 1868.15  4956.4 1866.61  4977.0 1867.77  4994.9 1866.07
  5008.0 1866.73  5015.5 1864.60  5015.9 1864.10  5020.5 1864.60  5048.1 1867.50
  5093.6 1868.37  5098.6 1867.76  5189.6 1869.28  5244.5 1869.18  6837.3 1885.04
#Mann=10,-1,0
  3218.1   0.035       0  3265.5    0.07       0  3506.2   0.035       0
  3530.0    0.07       0  3781.1   0.035       0  3795.9    0.07       0
  4017.0   0.035       0  4057.0    0.07       0  5015.5    0.07       0
  5020.5    0.07       0
Bank Sta=5015.5,5020.5
Exp/Cntr=0.3,0.1

Type RM Length L Ch R = 1,3736,1167,1167,1167
BEGIN DESCRIPTION:
Mapping XS 55834a25
END DESCRIPTION:
XS GIS Cut Line= 4
      1434261.93      6921623.64      1435483.23      6922471.58
      1435888.99      6922488.40      1437621.69      6921905.63
#Sta/Elev= 30
  3094.7 1876.46  3194.3 1875.26  3563.5 1870.62  3968.7 1867.57  4048.0 1867.26
  4061.4 1865.96  4169.7 1867.16  4279.3 1864.84  4306.6 1867.07  4336.3 1867.35
  4580.6 1867.38  4699.7 1867.78  4743.4 1868.29  4823.5 1866.15  4863.5 1867.48
  4933.6 1867.18  4963.6 1864.43  4983.1 1865.91  5046.7 1866.45  5099.2 1862.90
  5099.6 1862.40  5104.2 1862.90  5141.7 1867.34  5183.9 1863.56  5236.6 1867.50
  5391.3 1869.58  5447.1 1870.32  5602.3 1872.10  5665.0 1872.67  6815.7 1883.73
#Mann=13,-1,0
  3094.7    0.07       0  3194.3   0.035       0  3563.5    0.07       0
  3968.7    0.16       0  4061.4    0.07       0  4580.6    0.16       0
  4699.7    0.07       0  5099.2    0.07       0  5104.2    0.07       0
  5391.3    0.16       0  5447.1    0.07       0  5602.3    0.16       0
  5665.0    0.07       0
Bank Sta=5099.2,5104.2
Exp/Cntr=0.3,0.1

Type RM Length L Ch R = 1,2569,55,55,55
BEGIN DESCRIPTION:
Mapping XS 94930b11
END DESCRIPTION:
XS GIS Cut Line= 6
      1434218.23      6921616.50      1435294.64      6922415.12
      1436050.45      6923201.94      1436180.66      6923248.82
      1436295.24      6923217.57      1437560.41      6922363.71
#Sta/Elev= 30
  2751.0 1877.04  2906.3 1875.09  3299.0 1870.06  3630.8 1867.67  3764.3 1866.15
  3786.2 1864.69  3850.9 1866.81  3942.6 1864.27  4007.3 1866.94  4317.3 1866.80
  4636.6 1865.82  5114.0 1864.34  5129.0 1865.65  5150.1 1863.54  5165.1 1866.09
  5192.5 1866.68  5217.9 1863.84  5223.2 1865.58  5243.3 1863.75  5248.6 1865.72
  5271.4 1862.90  5271.8 1862.40  5276.7 1862.90  5279.3 1865.06  5304.7 1865.05
  5310.0 1867.06  5385.1 1864.09  5486.0 1868.43  5515.1 1866.86  6969.4 1881.28
#Mann=9,-1,0
  2751.0    0.07       0  2906.3   0.035       0  3299.0    0.07       0
  3630.8    0.16       0  3764.3    0.07       0  4317.3    0.16       0
  4636.6    0.07       0  5271.4    0.07       0  5276.7    0.07       0
Bank Sta=5271.4,5276.7
Exp/Cntr=0.3,0.1

Type RM Length L Ch R = 1,2514,61,61,61
BEGIN DESCRIPTION:
Mapping XS bbe8400f
END DESCRIPTION:
XS GIS Cut Line= 6
      1435227.51      6922446.71      1435909.83      6923087.36
      1436034.83      6923238.40      1436165.04      6923280.07
      1436368.16      6923233.19      1437580.89      6922400.42
#Sta/Elev= 30
  4064.1 1866.31  4416.6 1866.53  4759.0 1865.24  5001.2 1864.38  5001.6 1863.88
  5006.5 1864.38  5075.5 1869.69  5110.7 1869.58  5125.0 1870.87  5174.5 1870.13
  5211.6 1872.21  5243.8 1870.59  5249.0 1871.75  5275.9 1870.52  5281.2 1871.74
  5301.3 1870.81  5313.3 1871.97  5361.3 1871.67  5366.5 1869.80  5404.1 1870.13
  5409.2 1868.70  5452.0 1870.95  5457.1 1869.48  5486.7 1870.48  5507.2 1869.62
  5517.5 1867.53  5527.8 1867.06  5563.5 1867.24  6334.3 1876.04  7012.4 1881.50
#Mann=5,-1,0
  4064.1    0.07       0  4416.6    0.16       0  4759.0    0.07       0
  5001.2    0.07       0  5006.5    0.07       0
Bank Sta=5001.2,5006.5
Exp/Cntr=0.3,0.1

Type RM Length L Ch R = 1,2453,745,745,745
BEGIN DESCRIPTION:
Mapping XS 98646183
END DESCRIPTION:
XS GIS Cut Line= 6
      1435211.91      6922514.44      1435998.37      6923274.86
      1436112.95      6923326.94      1436232.74      6923326.94
      1436326.49      6923306.11      1437597.30      6922478.00
#Sta/Elev= 30
  4069.7 1865.93  4198.4 1866.03  4200.9 1865.94  4473.3 1865.74  4597.0 1865.48
  4959.0 1864.05  5005.9 1864.57  5022.8 1863.97  5066.1 1864.44  5072.5 1865.34
  5080.0 1864.22  5136.6 1864.76  5204.6 1863.62  5216.5 1862.49  5233.2 1862.72
  5238.6 1861.33  5249.5 1861.29  5256.2 1862.19  5259.1 1861.05  5259.5 1860.55
  5264.4 1861.05  5284.8 1863.27  5454.2 1866.15  5533.0 1866.27  5946.6 1871.56
  6469.7 1876.62  6521.1 1877.31  6682.9 1878.40  6770.4 1879.85  7023.8 1881.44
#Mann=9,-1,0
  4069.7    0.07       0  4198.4    0.16       0  4200.9    0.07       0
  4473.3    0.16       0  4597.0    0.07       0  5259.1    0.07       0
  5264.4    0.07       0  6469.7    0.16       0  6521.1    0.07       0
Bank Sta=5259.1,5264.4
Exp/Cntr=0.3,0.1

Type RM Length L Ch R = 1,1708,1073,1073,1073
BEGIN DESCRIPTION:
Mapping XS 9497dd03
END DESCRIPTION:
XS GIS Cut Line= 5
      1435075.00      6923246.50      1435252.97      6923550.34
      1435496.02      6923585.06      1436368.42      6923745.65
      1437297.24      6922838.52
#Sta/Elev= 30
  4396.6 1861.95  4425.0 1861.88  4738.2 1861.15  4908.2 1861.49  4942.7 1860.98
  4983.9 1858.21  5003.4 1858.08  5013.5 1855.87  5021.0 1855.75  5021.4 1855.25
  5026.0 1855.25  5026.4 1855.75  5033.5 1856.20  5037.1 1857.46  5042.2 1857.79
  5074.5 1858.14  5105.1 1859.79  5142.4 1860.51  5202.7 1861.87  5471.1 1862.00
  5501.6 1862.65  5811.6 1864.41  6096.5 1867.93  6138.9 1867.74  6209.6 1869.19
  6570.3 1871.86  6584.4 1872.53  6803.6 1874.32  7050.5 1877.27  7179.6 1878.23
#Mann=9,-1,0
  4396.6    0.16       0  4425.0    0.07       0  4738.2    0.16       0
  5021.0    0.07       0  5026.4    0.16       0  5037.1    0.07       0
  5042.2    0.16       0  5142.4    0.07       0  7050.5    0.16       0
Bank Sta=5021,5026.4
Exp/Cntr=0.3,0.1

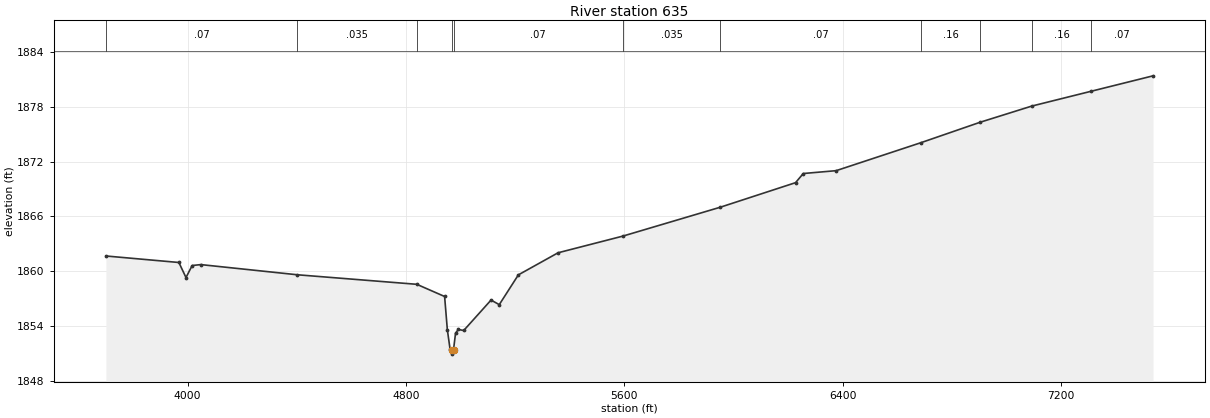
Type RM Length L Ch R = 1,635,0,0,0
BEGIN DESCRIPTION:
East China Creek Trib3 1.0
END DESCRIPTION:
XS GIS Cut Line= 5
      1435083.27      6923319.15      1435243.56      6923784.71
      1435525.68      6924255.63      1436159.36      6924283.84
      1437605.41      6922678.42
#Sta/Elev= 30
  3700.4 1861.69  3967.8 1860.98  3993.8 1859.34  4016.5 1860.65  4048.2 1860.75
  4401.6 1859.64  4839.3 1858.60  4941.3 1857.27  4951.3 1853.64  4961.3 1851.52
  4968.5 1851.48  4969.0 1850.98  4974.0 1851.48  4981.3 1853.26  4991.3 1853.67
  5011.3 1853.56  5111.4 1856.88  5141.5 1856.38  5211.5 1859.63  5356.9 1862.04
  5594.4 1863.86  5951.1 1867.01  6226.9 1869.69  6255.3 1870.69  6375.6 1871.00
  6686.9 1874.06  6903.8 1876.29  7092.5 1878.05  7310.5 1879.67  7536.7 1881.35
#Mann=11,-1,0
  3700.4    0.07       0  4401.6   0.035       0  4839.3    0.07       0
  4968.5    0.07       0  4974.0    0.07       0  5594.4   0.035       0
  5951.1    0.07       0  6686.9    0.16       0  6903.8    0.07       0
  7092.5    0.16       0  7310.5    0.07       0
Bank Sta=4968.5,4974
Exp/Cntr=0.3,0.1

Chan Stop Cuts=-1