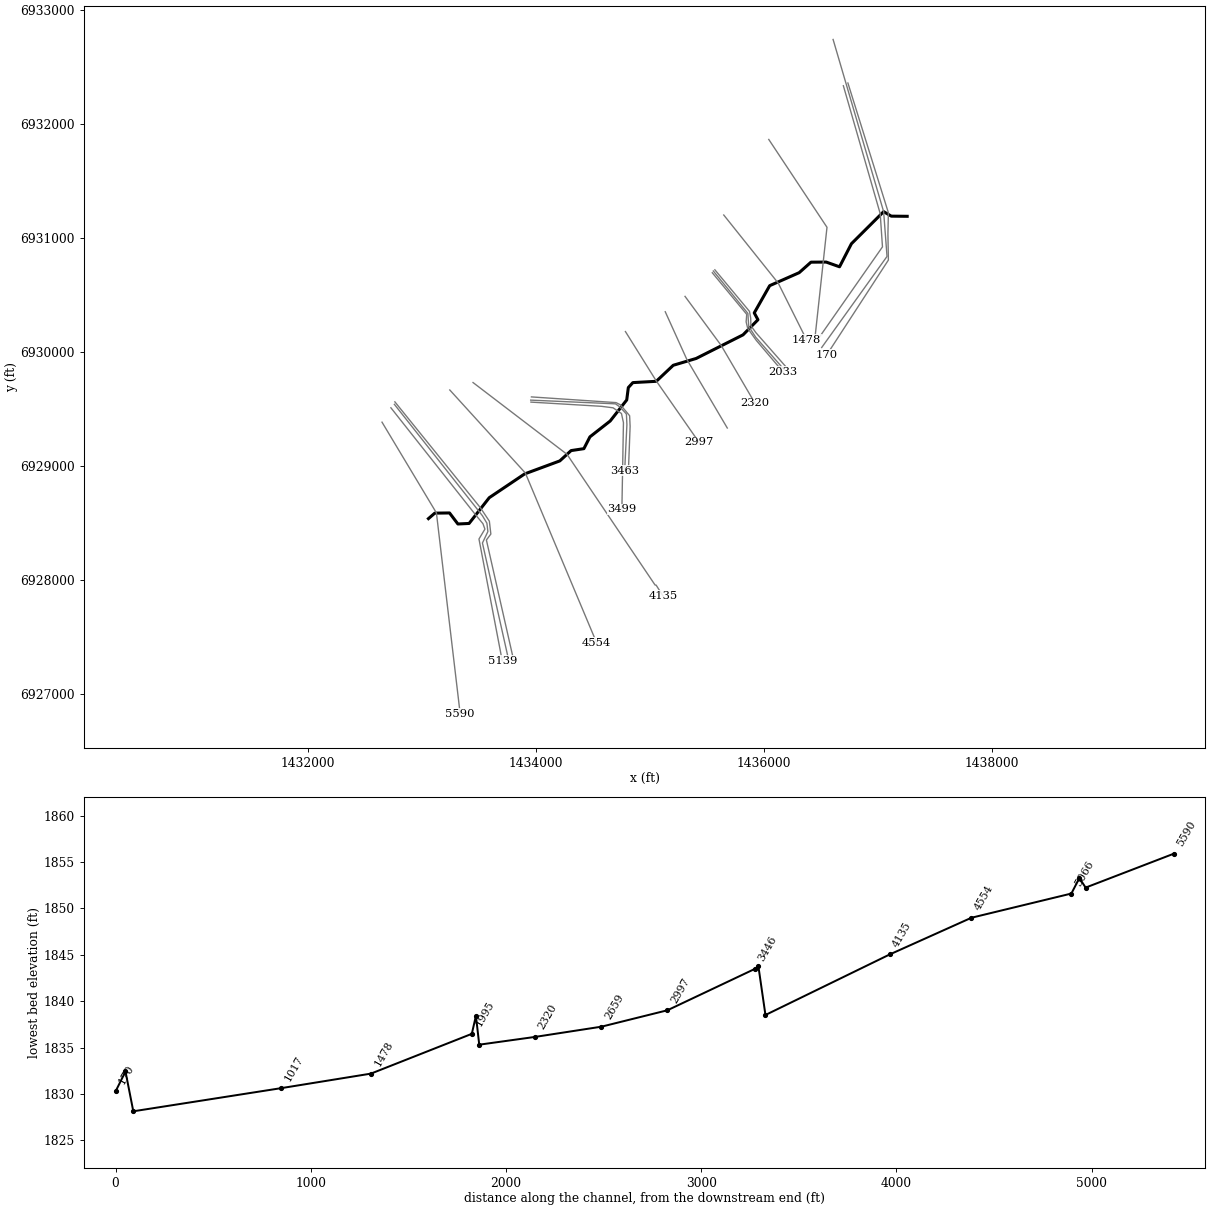
--- East China Creek Trib4.prj (project) ---

Proj Title=East China Creek Trib4 Base Level Engineering
Current Plan=p01
Default Exp/Contr=0.3,0.1
English Units
Geom File=g01
Flow File=f01
Plan File=p01
BEGIN DESCRIPTION:
East China Creek Trib4
END DESCRIPTION:

--- East China Creek Trib4.p01 (plan) ---

Plan Title=Multiple Run
Short Identifier=Multiple
Geom File=g01
Flow File=f01
Subcritical Flow
K Sum by GR= 0
Std Step Tol= 0.01
Critical Tol= 0.01
Num of Std Step Trials= 20
Max Error Tol= 0.3
Flow Tol Ratio= 0.001
Split Flow NTrial= 30
Split Flow Tol= 0.02
Split Flow Ratio= 0.02
Log Output Level= 0
Friction Slope Method= 1
Unsteady Friction Slope Method= 2
Unsteady Bridges Friction Slope Method= 1
Parabolic Critical Depth
Global Vel Dist=  1 , 1 , 1
Global Log Level= 0
CheckData=True
Encroach Param= -1, 0, 0, 0
BEGIN DESCRIPTION:
Multiple Run
END DESCRIPTION:

--- East China Creek Trib4.f01 (steady flow) ---

Flow Title=Multiple
Number of Profiles=7
Profile Names=10-year,25-year,50-year,1pct_min,100-year,1pct_plu,500-year
River Rch & RM= East China Creek,Reach-1,5590
     192     261     316     191     381     760     558
River Rch & RM= East China Creek,Reach-1,4554
     343     483     600     370     738    1472    1130
River Rch & RM= East China Creek,Reach-1,2997
     377     534     665     411     820    1636    1265
Boundary for River Rch & Prof#=East China Creek,Reach-1,1
Up Type=0
Dn Type=3
Dn Slope=0.005
Boundary for River Rch & Prof#=East China Creek,Reach-1,2
Up Type=0
Dn Type=3
Dn Slope=0.005
Boundary for River Rch & Prof#=East China Creek,Reach-1,3
Up Type=0
Dn Type=3
Dn Slope=0.005
Boundary for River Rch & Prof#=East China Creek,Reach-1,4
Up Type=0
Dn Type=3
Dn Slope=0.005
Boundary for River Rch & Prof#=East China Creek,Reach-1,5
Up Type=0
Dn Type=3
Dn Slope=0.005
Boundary for River Rch & Prof#=East China Creek,Reach-1,6
Up Type=0
Dn Type=3
Dn Slope=0.005
Boundary for River Rch & Prof#=East China Creek,Reach-1,7
Up Type=0
Dn Type=3
Dn Slope=0.005

--- East China Creek Trib4.g01 (geometry) ---

Geom Title=Existing Conditions

River Reach=East China Creek,Reach-1
Reach XY= 30
      1433055.00      6928538.00      1433110.79      6928586.12
      1433239.96      6928587.67      1433313.36      6928491.00
      1433411.41      6928495.62      1433588.33      6928721.35
      1433898.95      6928929.84      1434207.29      6929043.85
      1434306.50      6929134.37      1434418.65      6929151.26
      1434471.66      6929254.66      1434649.38      6929393.62
      1434794.48      6929578.22      1434808.51      6929686.75
      1434848.48      6929730.32      1435053.54      6929741.54
      1435202.70      6929882.17      1435403.42      6929941.83
      1435814.68      6930148.76      1435945.70      6930281.33
      1435913.25      6930341.23      1436048.66      6930579.98
      1436307.29      6930693.85      1436410.86      6930785.95
      1436544.50      6930786.77      1436661.34      6930745.36
      1436765.76      6930947.68      1437048.26      6931228.88
      1437115.41      6931189.35      1437255.00      6931188.00

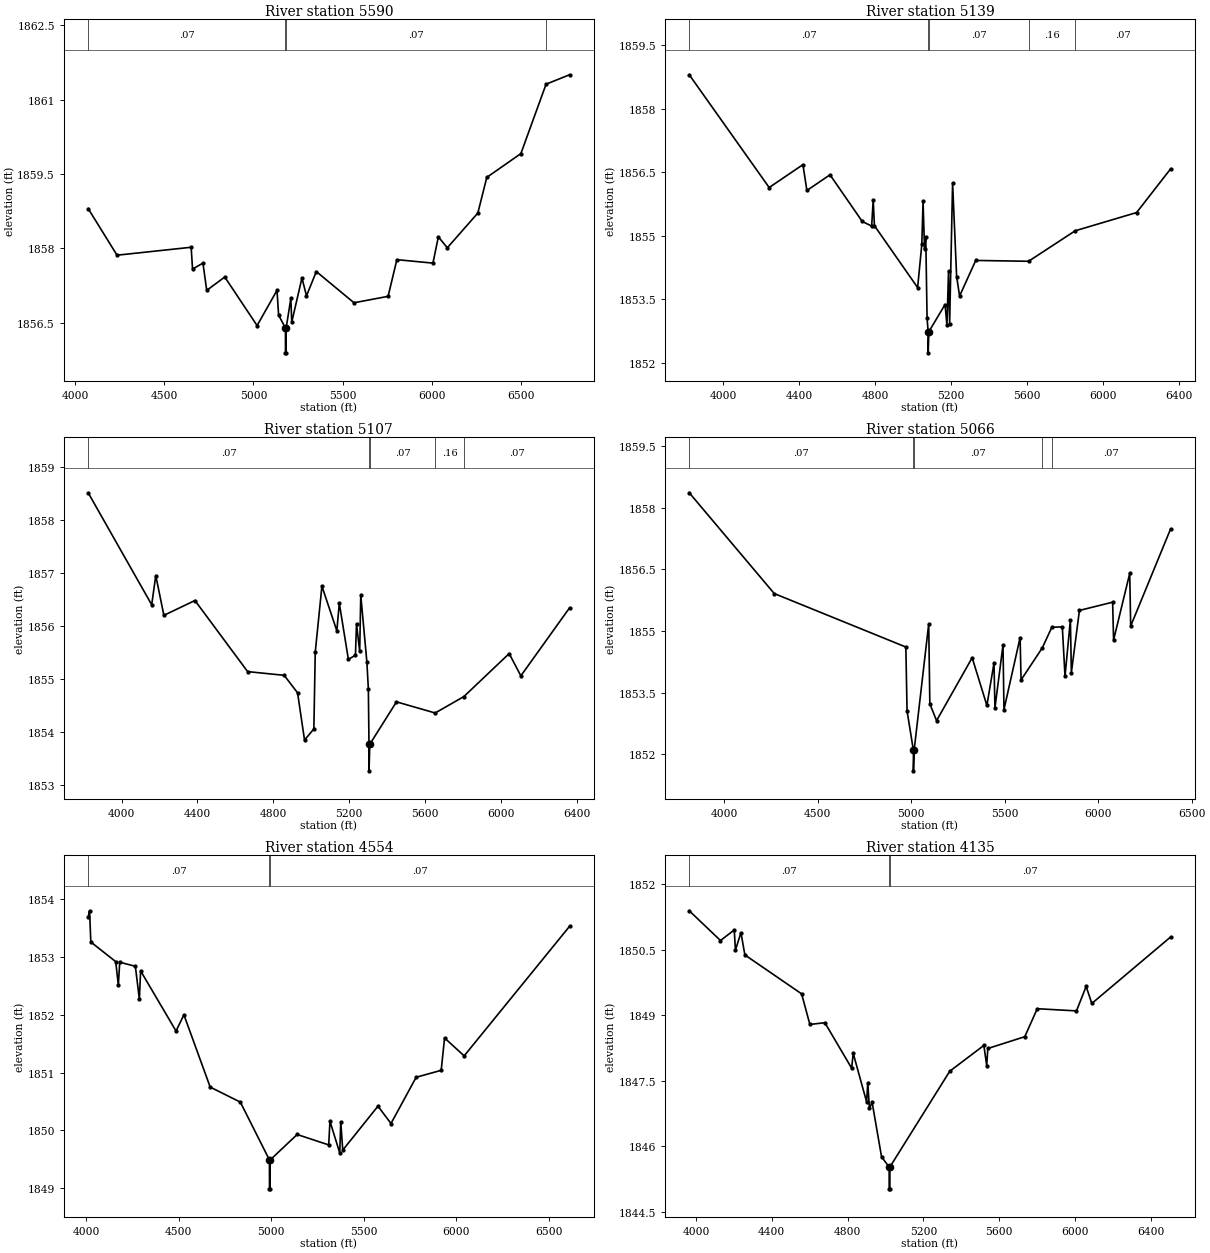
Type RM Length L Ch R = 1,5590,451,451,451
BEGIN DESCRIPTION:
East China Creek Trib4 9.0
END DESCRIPTION:
XS GIS Cut Line= 3
      1432647.65      6929383.50      1433125.00      6928588.04
      1433333.39      6926827.13
#Sta/Elev= 30
  4072.3 1858.80  4234.3 1857.86  4650.2 1858.02  4658.0 1857.58  4716.3 1857.70
  4737.6 1857.15  4838.7 1857.42  5020.2 1856.44  5131.8 1857.15  5141.0 1856.65
  5179.3 1856.39  5179.5 1855.89  5183.0 1855.89  5183.3 1856.39  5209.6 1856.99
  5214.6 1856.51  5271.9 1857.40  5297.4 1857.04  5352.5 1857.53  5564.0 1856.90
  5755.3 1857.03  5804.5 1857.77  6007.0 1857.70  6037.2 1858.23  6087.6 1858.01
  6258.8 1858.71  6309.1 1859.43  6500.4 1859.91  6641.7 1861.31  6773.2 1861.50
#Mann=4,-1,0
  4072.3    0.07       0  5179.3    0.07       0  5183.3    0.07       0
  6641.7    0.16       0
Bank Sta=5179.3,5183.3
Exp/Cntr=0.3,0.1

Type RM Length L Ch R = 1,5139,32,32,32
BEGIN DESCRIPTION:
Mapping XS b77a3900
END DESCRIPTION:
XS GIS Cut Line= 6
      1432725.78      6929509.37      1433467.94      6928571.91
      1433533.04      6928493.78      1433550.40      6928446.04
      1433498.32      6928359.24      1433702.18      6927292.24
#Sta/Elev= 30
  3819.9 1858.80  4240.9 1856.14  4418.8 1856.68  4439.6 1856.07  4561.4 1856.44
  4731.2 1855.34  4780.9 1855.23  4789.0 1855.85  4795.4 1855.24  5023.0 1853.78
  5045.1 1854.80  5051.6 1855.82  5059.4 1854.69  5065.9 1854.97  5072.7 1853.07
  5078.3 1852.74  5078.5 1852.24  5082.3 1852.74  5167.5 1853.38  5177.4 1852.89
  5185.8 1854.16  5191.6 1852.92  5207.2 1856.25  5228.5 1854.04  5244.1 1853.58
  5329.1 1854.42  5607.3 1854.40  5853.3 1855.12  6176.7 1855.55  6355.6 1856.58
#Mann=5,-1,0
  3819.9    0.07       0  5078.3    0.07       0  5082.3    0.07       0
  5607.3    0.16       0  5853.3    0.07       0
Bank Sta=5078.3,5082.3
Exp/Cntr=0.3,0.1

Type RM Length L Ch R = 1,5107,41,41,41
BEGIN DESCRIPTION:
Mapping XS 7bbda422
END DESCRIPTION:
XS GIS Cut Line= 6
      1432756.13      6929539.79      1433528.70      6928563.23
      1433567.76      6928498.12      1433576.44      6928424.34
      1433528.70      6928324.51      1433754.40      6927317.54
#Sta/Elev= 30
  3823.8 1858.51  4158.9 1856.40  4180.4 1856.95  4223.2 1856.20  4387.0 1856.48
  4664.9 1855.14  4857.8 1855.07  4928.4 1854.74  4965.1 1853.85  5014.3 1854.06
  5021.7 1855.51  5056.8 1856.75  5135.5 1855.91  5148.5 1856.43  5196.4 1855.37
  5233.7 1855.45  5239.3 1856.04  5256.1 1855.52  5261.7 1856.58  5294.0 1855.32
  5301.7 1854.82  5305.2 1853.77  5305.4 1853.27  5309.2 1853.77  5450.2 1854.57
  5654.2 1854.36  5805.8 1854.67  6044.6 1855.48  6106.1 1855.06  6362.8 1856.34
#Mann=5,-1,0
  3823.8    0.07       0  5305.2    0.07       0  5309.2    0.07       0
  5654.2    0.16       0  5805.8    0.07       0
Bank Sta=5305.2,5309.2
Exp/Cntr=0.3,0.1

Type RM Length L Ch R = 1,5066,512,512,512
BEGIN DESCRIPTION:
Mapping XS 911b9081
END DESCRIPTION:
XS GIS Cut Line= 6
      1432760.49      6929561.47      1433511.34      6928632.67
      1433589.46      6928515.49      1433602.49      6928402.64
      1433563.42      6928350.56      1433797.79      6927317.59
#Sta/Elev= 30
  3814.2 1858.36  4268.5 1855.91  4972.1 1854.61  4978.5 1853.06  5012.4 1852.10
  5012.6 1851.60  5016.4 1852.10  5094.3 1855.17  5100.3 1853.23  5136.3 1852.82
  5326.6 1854.35  5405.3 1853.19  5443.3 1854.22  5448.4 1853.13  5491.5 1854.66
  5496.6 1853.09  5582.9 1854.84  5588.0 1853.81  5701.6 1854.59  5752.4 1855.09
  5808.6 1855.10  5822.9 1853.90  5851.7 1855.27  5856.9 1853.99  5900.0 1855.50
  6077.5 1855.70  6082.6 1854.78  6168.9 1856.40  6174.0 1855.12  6387.3 1857.48
#Mann=5,-1,0
  3814.2    0.07       0  5012.4    0.07       0  5016.4    0.07       0
  5701.6    0.16       0  5752.4    0.07       0
Bank Sta=5012.4,5016.4
Exp/Cntr=0.3,0.1

Type RM Length L Ch R = 1,4554,419,419,419
BEGIN DESCRIPTION:
East China Creek Trib4 7.0
END DESCRIPTION:
XS GIS Cut Line= 3
      1433242.26      6929665.64      1433905.00      6928938.00
      1434530.65      6927449.35
#Sta/Elev= 30
  4011.5 1853.69  4019.0 1853.80  4025.8 1853.26  4160.3 1852.92  4174.4 1852.51
  4181.9 1852.91  4266.3 1852.84  4288.0 1852.27  4294.7 1852.76  4485.9 1851.72
  4528.5 1852.00  4670.4 1850.75  4833.2 1850.49  4990.3 1849.49  4990.6 1848.99
  4994.1 1848.99  4994.3 1849.49  5139.9 1849.93  5310.3 1849.75  5317.0 1850.16
  5370.0 1849.61  5375.4 1850.15  5386.2 1849.66  5576.2 1850.42  5646.6 1850.12
  5782.5 1850.92  5917.7 1851.04  5935.9 1851.60  6041.7 1851.29  6610.5 1853.53
#Mann=3,-1,0
  4011.5    0.07       0  4990.3    0.07       0  4994.3    0.07       0
Bank Sta=4990.3,4994.3
Exp/Cntr=0.3,0.1

Type RM Length L Ch R = 1,4135,636,636,636
BEGIN DESCRIPTION:
Mapping XS 7681cef8
END DESCRIPTION:
XS GIS Cut Line= 5
      1433446.24      6929730.76      1434270.89      6929101.42
      1435043.46      6927955.59      1435052.14      6927955.59
      1435112.00      6927861.52
#Sta/Elev= 30
  3964.7 1851.39  4129.4 1850.71  4202.1 1850.95  4208.4 1850.49  4237.4 1850.89
  4258.2 1850.38  4557.5 1849.49  4601.1 1848.79  4680.1 1848.83  4821.5 1847.79
  4829.7 1848.13  4900.4 1847.02  4906.7 1847.46  4915.0 1846.87  4929.5 1847.01
  4979.4 1845.76  5019.3 1845.53  5019.6 1845.03  5023.1 1845.03  5023.3 1845.53
  5339.1 1847.72  5519.0 1848.31  5534.0 1847.85  5540.0 1848.24  5734.9 1848.51
  5800.8 1849.15  6007.7 1849.10  6058.7 1849.66  6088.6 1849.27  6504.2 1850.79
#Mann=3,-1,0
  3964.7    0.07       0  5019.3    0.07       0  5023.3    0.07       0
Bank Sta=5019.3,5023.3
Exp/Cntr=0.3,0.1

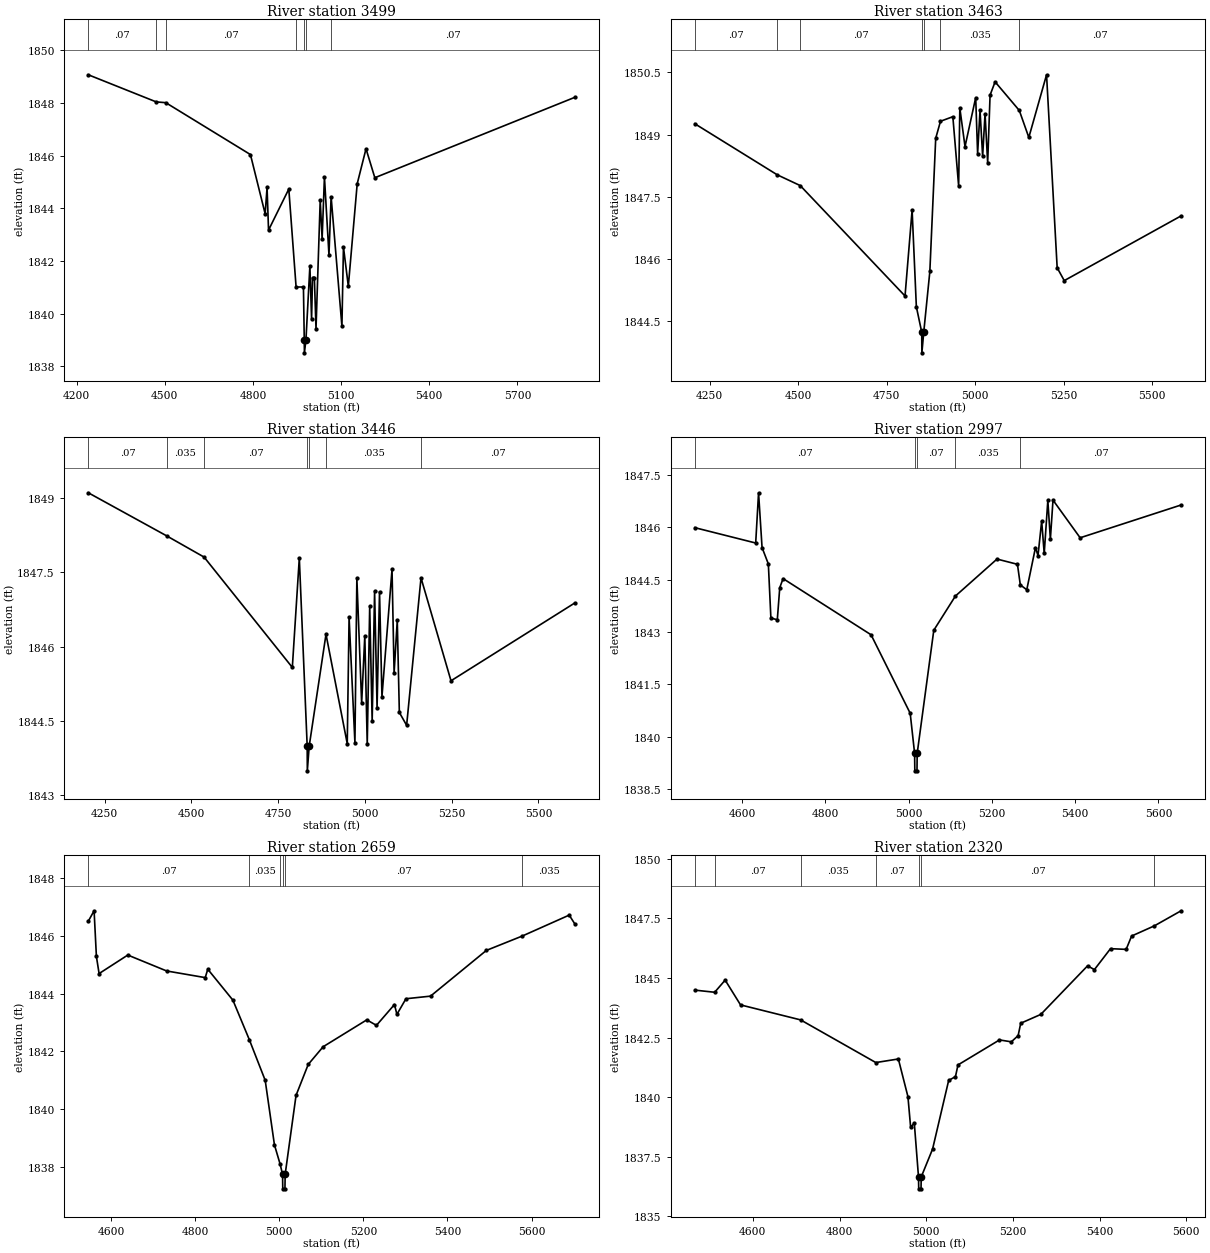
Type RM Length L Ch R = 1,3499,36,36,36
BEGIN DESCRIPTION:
Mapping XS 281655c2
END DESCRIPTION:
XS GIS Cut Line= 6
      1433954.08      6929559.32      1434572.54      6929522.43
      1434674.53      6929509.41      1434748.32      6929459.50
      1434765.68      6929379.20      1434752.03      6928618.19
#Sta/Elev= 30
  4239.4 1849.07  4470.6 1848.04  4503.2 1848.01  4791.3 1846.04  4841.4 1843.79
  4847.9 1844.79  4852.9 1843.17  4921.9 1844.73  4946.7 1841.01  4971.7 1841.01
  4974.5 1839.01  4975.0 1838.51  4980.3 1839.01  4993.7 1841.81  4999.4 1839.79
  5002.7 1841.37  5008.9 1841.37  5014.5 1839.43  5028.8 1844.30  5035.3 1842.84
  5043.2 1845.19  5058.6 1842.23  5065.9 1844.44  5102.7 1839.52  5107.9 1842.53
  5124.5 1841.04  5154.7 1844.93  5184.7 1846.26  5214.7 1845.16  5894.6 1848.21
#Mann=7,-1,0
  4239.4    0.07       0  4470.6   0.035       0  4503.2    0.07       0
  4946.7   0.035       0  4974.5   0.035       0  4980.3   0.035       0
  5065.9    0.07       0
Bank Sta=4974.5,4980.3
Exp/Cntr=0.3,0.1

Type RM Length L Ch R = 1,3463,17,17,17
BEGIN DESCRIPTION:
Mapping XS bc160acc
END DESCRIPTION:
XS GIS Cut Line= 6
      1433951.90      6929576.68      1434696.24      6929544.13
      1434735.30      6929515.92      1434791.72      6929455.16
      1434796.06      6929361.84      1434776.53      6928958.22
#Sta/Elev= 30
  4208.0 1849.26  4440.8 1848.03  4505.9 1847.77  4802.0 1845.11  4822.0 1847.18
  4834.0 1844.85  4849.1 1844.24  4849.6 1843.74  4854.9 1844.24  4872.1 1845.70
  4888.7 1848.91  4902.2 1849.32  4937.1 1849.43  4953.5 1847.76  4956.8 1849.64
  4971.5 1848.71  5001.7 1849.89  5007.1 1848.54  5013.9 1849.58  5021.3 1848.48
  5028.1 1849.50  5035.5 1848.32  5042.3 1849.95  5056.5 1850.27  5124.9 1849.58
  5151.8 1848.93  5201.9 1850.44  5231.9 1845.79  5251.9 1845.48  5582.1 1847.04
#Mann=7,-1,0
  4208.0    0.07       0  4440.8   0.035       0  4505.9    0.07       0
  4849.1   0.035       0  4854.9    0.07       0  4902.2   0.035       0
  5124.9    0.07       0
Bank Sta=4849.1,4854.9
Exp/Cntr=0.3,0.1

Type RM Length L Ch R = 1,3446,449,449,449
BEGIN DESCRIPTION:
Mapping XS f6b4856d
END DESCRIPTION:
XS GIS Cut Line= 6
      1433958.44      6929604.89      1434700.58      6929554.98
      1434739.64      6929535.45      1434819.93      6929439.97
      1434824.27      6929346.65      1434809.11      6928952.31
#Sta/Elev= 30
  4203.3 1849.11  4428.9 1848.24  4536.9 1847.81  4791.1 1845.58  4811.2 1847.79
  4833.9 1843.99  4834.3 1843.49  4839.7 1843.99  4888.1 1846.25  4949.3 1844.04
  4954.6 1846.59  4971.4 1844.06  4977.0 1847.38  4990.8 1844.86  4999.9 1846.22
  5006.9 1844.03  5014.0 1846.82  5021.1 1844.49  5028.1 1847.12  5035.2 1844.77
  5042.3 1847.11  5049.3 1844.99  5078.3 1847.56  5084.3 1845.47  5093.4 1846.53
  5099.4 1844.67  5120.4 1844.41  5161.8 1847.39  5248.2 1845.31  5604.2 1846.88
#Mann=7,-1,0
  4203.3    0.07       0  4428.9   0.035       0  4536.9    0.07       0
  4833.9   0.035       0  4839.7    0.07       0  4888.1   0.035       0
  5161.8    0.07       0
Bank Sta=4833.9,4839.7
Exp/Cntr=0.3,0.1

Type RM Length L Ch R = 1,2997,338,338,338
BEGIN DESCRIPTION:
Mapping XS 482a18f4
END DESCRIPTION:
XS GIS Cut Line= 3
      1434783.05      6930177.79      1435054.31      6929743.78
      1435429.74      6929205.60
#Sta/Elev= 30
  4486.5 1845.99  4632.7 1845.55  4639.6 1846.99  4648.0 1845.42  4663.1 1844.95
  4669.2 1843.40  4684.6 1843.35  4690.5 1844.27  4698.5 1844.53  4909.8 1842.92
  5003.8 1840.67  5014.4 1839.52  5014.9 1839.02  5020.1 1839.02  5020.6 1839.52
  5060.5 1843.05  5112.4 1844.03  5212.3 1845.09  5261.4 1844.94  5268.3 1844.35
  5283.8 1844.21  5304.7 1845.42  5310.8 1845.19  5319.6 1846.18  5325.7 1845.25
  5334.4 1846.77  5340.5 1845.66  5346.8 1846.78  5412.0 1845.70  5654.5 1846.64
#Mann=5,-1,0
  4486.5    0.07       0  5014.4    0.07       0  5020.6    0.07       0
  5112.4   0.035       0  5268.3    0.07       0
Bank Sta=5014.4,5020.6
Exp/Cntr=0.3,0.1

Type RM Length L Ch R = 1,2659,339,339,339
BEGIN DESCRIPTION:
Mapping XS fd971b69
END DESCRIPTION:
XS GIS Cut Line= 3
      1435132.44      6930351.40      1435321.24      6929934.76
      1435676.69      6929332.21
#Sta/Elev= 30
  4545.4 1846.50  4559.2 1846.86  4564.7 1845.28  4571.1 1844.69  4639.4 1845.33
  4731.8 1844.78  4823.6 1844.55  4829.7 1844.84  4889.5 1843.77  4928.4 1842.41
  4966.3 1841.00  4988.3 1838.77  5001.9 1838.10  5007.6 1837.75  5008.1 1837.25
  5013.3 1837.25  5013.8 1837.75  5039.7 1840.48  5068.7 1841.55  5104.1 1842.16
  5208.0 1843.09  5231.0 1842.90  5273.9 1843.62  5279.7 1843.28  5301.2 1843.82
  5359.7 1843.91  5492.5 1845.49  5578.4 1845.99  5689.6 1846.71  5702.4 1846.42
#Mann=6,-1,0
  4545.4    0.07       0  4928.4   0.035       0  5001.9    0.07       0
  5007.6   0.035       0  5013.8    0.07       0  5578.4   0.035       0
Bank Sta=5007.6,5013.8
Exp/Cntr=0.3,0.1

Type RM Length L Ch R = 1,2320,287,287,287
BEGIN DESCRIPTION:
Mapping XS b01c2b53
END DESCRIPTION:
XS GIS Cut Line= 3
      1435306.02      6930486.01      1435622.88      6930056.28
      1435920.11      6929548.61
#Sta/Elev= 30
  4466.1 1844.49  4511.9 1844.40  4536.1 1844.91  4571.6 1843.87  4710.3 1843.24
  4883.8 1841.45  4935.8 1841.60  4957.9 1840.02  4964.1 1838.74  4972.6 1838.91
  4982.3 1836.65  4982.8 1836.15  4988.1 1836.15  4988.6 1836.65  5014.8 1837.82
  5051.9 1840.70  5067.6 1840.86  5073.4 1841.35  5169.2 1842.40  5196.5 1842.32
  5212.2 1842.58  5218.2 1843.10  5264.5 1843.47  5372.5 1845.51  5388.2 1845.35
  5425.4 1846.23  5461.5 1846.20  5474.1 1846.76  5526.9 1847.19  5588.3 1847.82
#Mann=7,-1,0
  4466.1   0.045       0  4511.9    0.07       0  4710.3   0.035       0
  4883.8    0.07       0  4982.3    0.07       0  4988.6    0.07       0
  5526.9   0.035       0
Bank Sta=4982.3,4988.6
Exp/Cntr=0.3,0.1

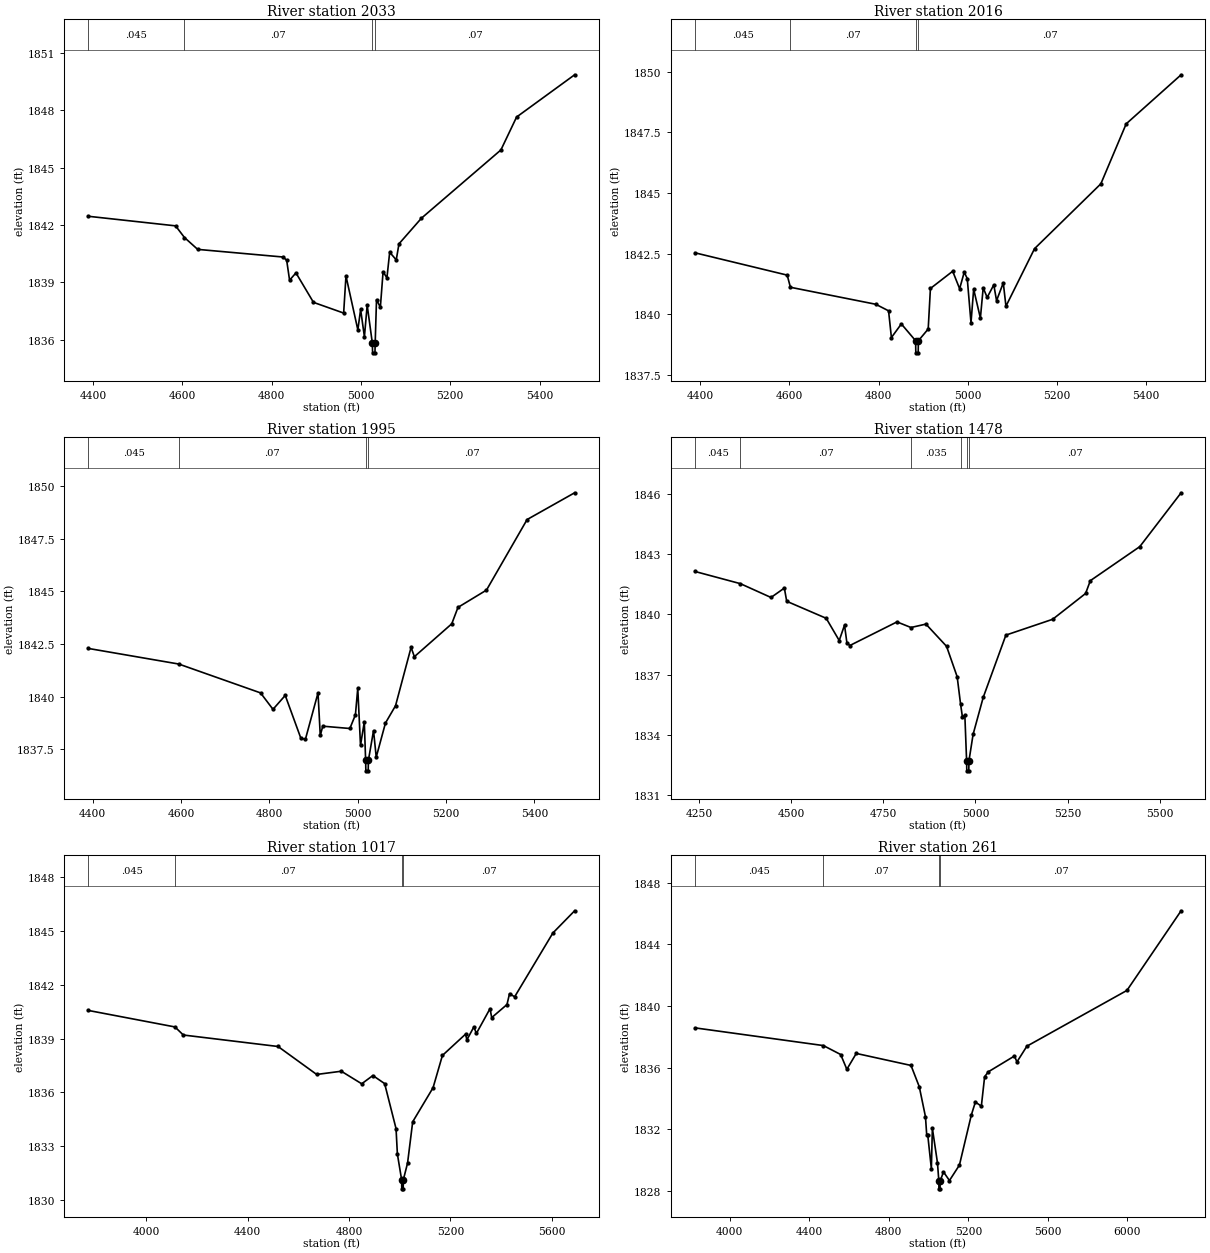
Type RM Length L Ch R = 1,2033,17,17,17
BEGIN DESCRIPTION:
Mapping XS 985f5a69
END DESCRIPTION:
XS GIS Cut Line= 6
      1435545.19      6930693.01      1435847.28      6930328.42
      1435842.07      6930262.45      1435855.96      6930205.16
      1435930.61      6930100.99      1436164.99      6929824.94
#Sta/Elev= 30
  4389.6 1842.45  4584.8 1841.95  4604.7 1841.34  4634.3 1840.72  4825.7 1840.32
  4833.6 1840.15  4840.1 1839.11  4854.4 1839.49  4893.6 1837.95  4961.2 1837.39
  4966.4 1839.33  4993.0 1836.51  4999.2 1837.58  5007.7 1836.15  5013.9 1837.80
  5025.5 1835.81  5026.0 1835.31  5031.3 1835.31  5031.8 1835.81  5034.8 1838.09
  5043.4 1837.69  5049.5 1839.55  5058.1 1839.23  5064.3 1840.57  5079.0 1840.17
  5085.1 1841.01  5135.4 1842.35  5313.4 1845.92  5348.5 1847.64  5478.5 1849.85
#Mann=4,-1,0
  4389.6   0.045       0  4604.7    0.07       0  5025.5    0.07       0
  5031.8    0.07       0
Bank Sta=5025.5,5031.8
Exp/Cntr=0.3,0.1

Type RM Length L Ch R = 1,2016,21,21,21
BEGIN DESCRIPTION:
Mapping XS 57ac768d
END DESCRIPTION:
XS GIS Cut Line= 6
      1435553.96      6930708.62      1435857.27      6930337.07
      1435861.17      6930273.75      1435865.16      6930221.88
      1435925.40      6930128.77      1436180.18      6929839.05
#Sta/Elev= 30
  4387.6 1842.54  4594.9 1841.62  4602.1 1841.12  4793.8 1840.42  4822.5 1840.15
  4828.9 1839.05  4851.2 1839.61  4883.2 1838.92  4883.7 1838.42  4889.0 1838.42
  4889.5 1838.92  4911.5 1839.40  4916.5 1841.07  4966.5 1841.78  4982.1 1841.06
  4992.4 1841.74  4999.2 1841.48  5007.6 1839.66  5013.6 1841.04  5028.7 1839.85
  5035.0 1841.10  5043.9 1840.70  5058.8 1841.22  5065.0 1840.57  5080.1 1841.30
  5086.1 1840.34  5150.3 1842.71  5299.2 1845.38  5356.1 1847.85  5479.4 1849.87
#Mann=4,-1,0
  4387.6   0.045       0  4602.1    0.07       0  4883.2    0.07       0
  4889.5    0.07       0
Bank Sta=4883.2,4889.5
Exp/Cntr=0.3,0.1

Type RM Length L Ch R = 1,1995,517,517,517
BEGIN DESCRIPTION:
Mapping XS e3199461
END DESCRIPTION:
XS GIS Cut Line= 6
      1435567.78      6930719.02      1435871.58      6930354.46
      1435882.00      6930295.43      1435883.74      6930229.46
      1435927.14      6930168.70      1436208.41      6929849.23
#Sta/Elev= 30
  4390.2 1842.29  4594.8 1841.55  4779.9 1840.18  4808.1 1839.40  4835.8 1840.06
  4871.3 1838.02  4881.5 1837.98  4910.0 1840.18  4915.1 1838.16  4920.8 1838.60
  4982.1 1838.49  4994.7 1839.14  5000.0 1840.40  5006.2 1837.69  5014.8 1838.80
  5017.8 1836.98  5018.3 1836.48  5023.6 1836.48  5024.1 1836.98  5035.7 1838.39
  5041.8 1837.13  5062.7 1838.75  5085.5 1839.57  5120.7 1842.34  5128.2 1841.90
  5212.8 1843.46  5226.9 1844.24  5291.4 1845.06  5383.4 1848.41  5491.0 1849.68
#Mann=4,-1,0
  4390.2   0.045       0  4594.8    0.07       0  5017.8    0.07       0
  5024.1    0.07       0
Bank Sta=5017.8,5024.1
Exp/Cntr=0.3,0.1

Type RM Length L Ch R = 1,1478,461,461,461
BEGIN DESCRIPTION:
Mapping XS 3de6f06e
END DESCRIPTION:
XS GIS Cut Line= 3
      1435645.73      6931199.34      1436124.48      6930600.90
      1436371.85      6930106.17
#Sta/Elev= 30
  4238.7 1842.15  4362.2 1841.54  4445.3 1840.85  4481.5 1841.32  4487.9 1840.66
  4595.1 1839.81  4630.4 1838.70  4644.8 1839.47  4651.2 1838.59  4659.2 1838.45
  4787.2 1839.63  4825.1 1839.35  4865.7 1839.52  4921.7 1838.41  4950.5 1836.89
  4959.6 1835.54  4964.9 1834.86  4971.3 1834.98  4976.1 1832.69  4976.6 1832.19
  4982.0 1832.19  4982.5 1832.69  4993.7 1834.01  5021.2 1835.86  5082.7 1838.97
  5209.6 1839.76  5299.0 1841.05  5311.9 1841.69  5446.1 1843.39  5558.2 1846.08
#Mann=6,-1,0
  4238.7   0.045       0  4362.2    0.07       0  4825.1   0.035       0
  4959.6    0.07       0  4976.1    0.07       0  4982.5    0.07       0
Bank Sta=4976.1,4982.5
Exp/Cntr=0.3,0.1

Type RM Length L Ch R = 1,1017,756,756,756
BEGIN DESCRIPTION:
Mapping XS 17c8d409
END DESCRIPTION:
XS GIS Cut Line= 3
      1436040.70      6931861.62      1436551.37      6931091.63
      1436443.70      6930102.61
#Sta/Elev= 30
  3771.1 1840.57  4112.7 1839.65  4145.6 1839.20  4519.4 1838.56  4671.9 1837.00
  4769.1 1837.18  4849.6 1836.48  4893.7 1836.94  4940.1 1836.49  4985.1 1833.98
  4990.4 1832.56  5007.2 1831.12  5007.7 1830.62  5013.3 1830.62  5013.8 1831.12
  5030.6 1832.06  5050.8 1834.36  5131.2 1836.26  5168.1 1838.06  5259.5 1839.25
  5264.6 1838.93  5292.2 1839.65  5302.2 1839.29  5356.0 1840.67  5362.6 1840.17
  5422.9 1840.90  5433.0 1841.51  5453.1 1841.33  5604.0 1844.89  5689.9 1846.13
#Mann=4,-1,0
  3771.1   0.045       0  4112.7    0.07       0  5007.2    0.07       0
  5013.8    0.07       0
Bank Sta=5007.2,5013.8
Exp/Cntr=0.3,0.1

Type RM Length L Ch R = 1,261,40,40,40
BEGIN DESCRIPTION:
Mapping XS 78d2f936
END DESCRIPTION:
XS GIS Cut Line= 4
      1436695.01      6932332.37      1437018.16      6931211.31
      1437038.11      6930920.07      1436472.56      6930111.57
#Sta/Elev= 30
  3824.5 1838.58  4470.8 1837.43  4557.6 1836.85  4588.8 1835.89  4636.2 1836.92
  4911.4 1836.14  4953.0 1834.76  4984.2 1832.81  4990.3 1831.65  4995.4 1831.65
  5013.8 1829.44  5018.9 1832.06  5044.6 1829.81  5051.4 1828.63  5051.9 1828.13
  5057.5 1828.13  5058.0 1828.63  5074.7 1829.23  5104.8 1828.67  5154.9 1829.67
  5215.0 1832.93  5235.1 1833.76  5265.2 1833.50  5281.7 1835.41  5300.6 1835.73
  5431.4 1836.75  5444.3 1836.37  5494.2 1837.39  5997.4 1841.01  6269.8 1846.18
#Mann=4,-1,0
  3824.5   0.045       0  4470.8    0.07       0  5051.4    0.07       0
  5058.0    0.07       0
Bank Sta=5051.4,5058
Exp/Cntr=0.3,0.1

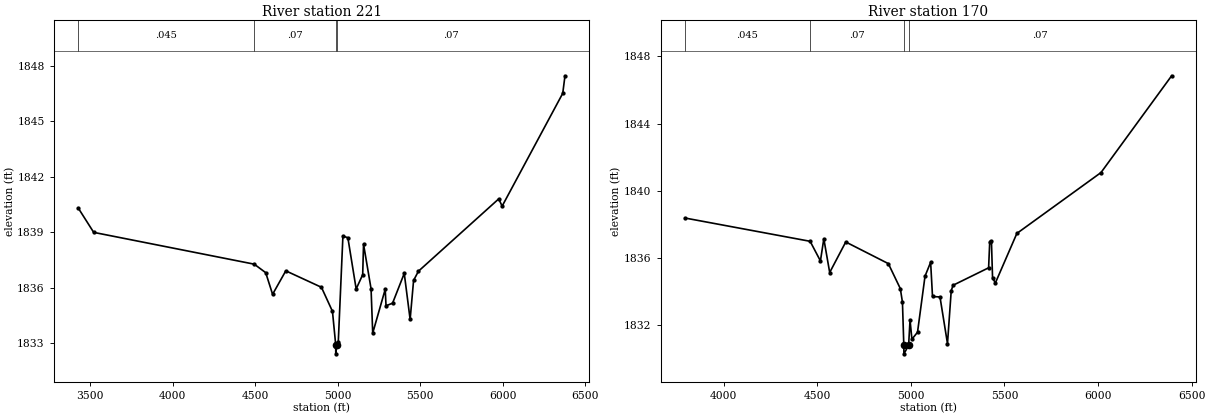
Type RM Length L Ch R = 1,221,51,51,51
BEGIN DESCRIPTION:
East China Creek Trib4 1.0
END DESCRIPTION:
XS GIS Cut Line= 4
      1436604.99      6932738.02      1437048.26      6931228.88
      1437078.01      6930836.29      1436504.98      6930037.97
#Sta/Elev= 30
  3427.1 1840.31  3521.0 1838.99  4493.7 1837.27  4563.2 1836.81  4604.9 1835.64
  4684.9 1836.91  4900.8 1836.02  4967.6 1834.72  4987.2 1832.92  4987.7 1832.42
  4993.8 1832.92  5002.9 1833.07  5031.0 1838.79  5061.0 1838.70  5111.2 1835.93
  5150.8 1836.70  5155.9 1838.35  5201.5 1835.94  5211.5 1833.54  5287.2 1835.91
  5292.2 1835.02  5331.8 1835.16  5402.6 1836.77  5438.2 1834.28  5459.1 1836.39
  5488.6 1836.89  5974.8 1840.80  5995.7 1840.41  6362.8 1846.51  6376.4 1847.46
#Mann=4,-1,0
  3427.1   0.045       0  4493.7    0.07       0  4987.2    0.07       0
  4993.8    0.07       0
Bank Sta=4987.2,4993.8
Exp/Cntr=0.3,0.1

Type RM Length L Ch R = 1,170,0,0,0
BEGIN DESCRIPTION:
Mapping XS 4a058548
END DESCRIPTION:
XS GIS Cut Line= 5
      1436734.90      6932356.33      1437089.97      6931219.29
      1437085.98      6931035.77      1437089.97      6930804.37
      1436548.21      6929971.81
#Sta/Elev= 30
  3793.6 1838.37  4462.6 1836.98  4517.6 1835.81  4535.7 1837.13  4567.1 1835.12
  4652.8 1836.94  4880.2 1835.65  4944.2 1834.16  4955.6 1833.35  4962.9 1830.77
  4963.4 1830.27  4988.5 1830.77  4996.1 1832.29  5006.1 1831.14  5036.1 1831.56
  5076.1 1834.90  5106.1 1835.73  5116.1 1833.69  5156.1 1833.66  5196.1 1830.88
  5216.1 1834.04  5226.1 1834.36  5415.7 1835.40  5421.7 1836.95  5430.8 1836.99
  5436.8 1834.79  5451.9 1834.50  5566.6 1837.45  6015.9 1841.08  6393.1 1846.85
#Mann=4,-1,0
  3793.6   0.045       0  4462.6    0.07       0  4962.9    0.07       0
  4988.5    0.07       0
Bank Sta=4962.9,4988.5
Exp/Cntr=0.3,0.1

Chan Stop Cuts=-1