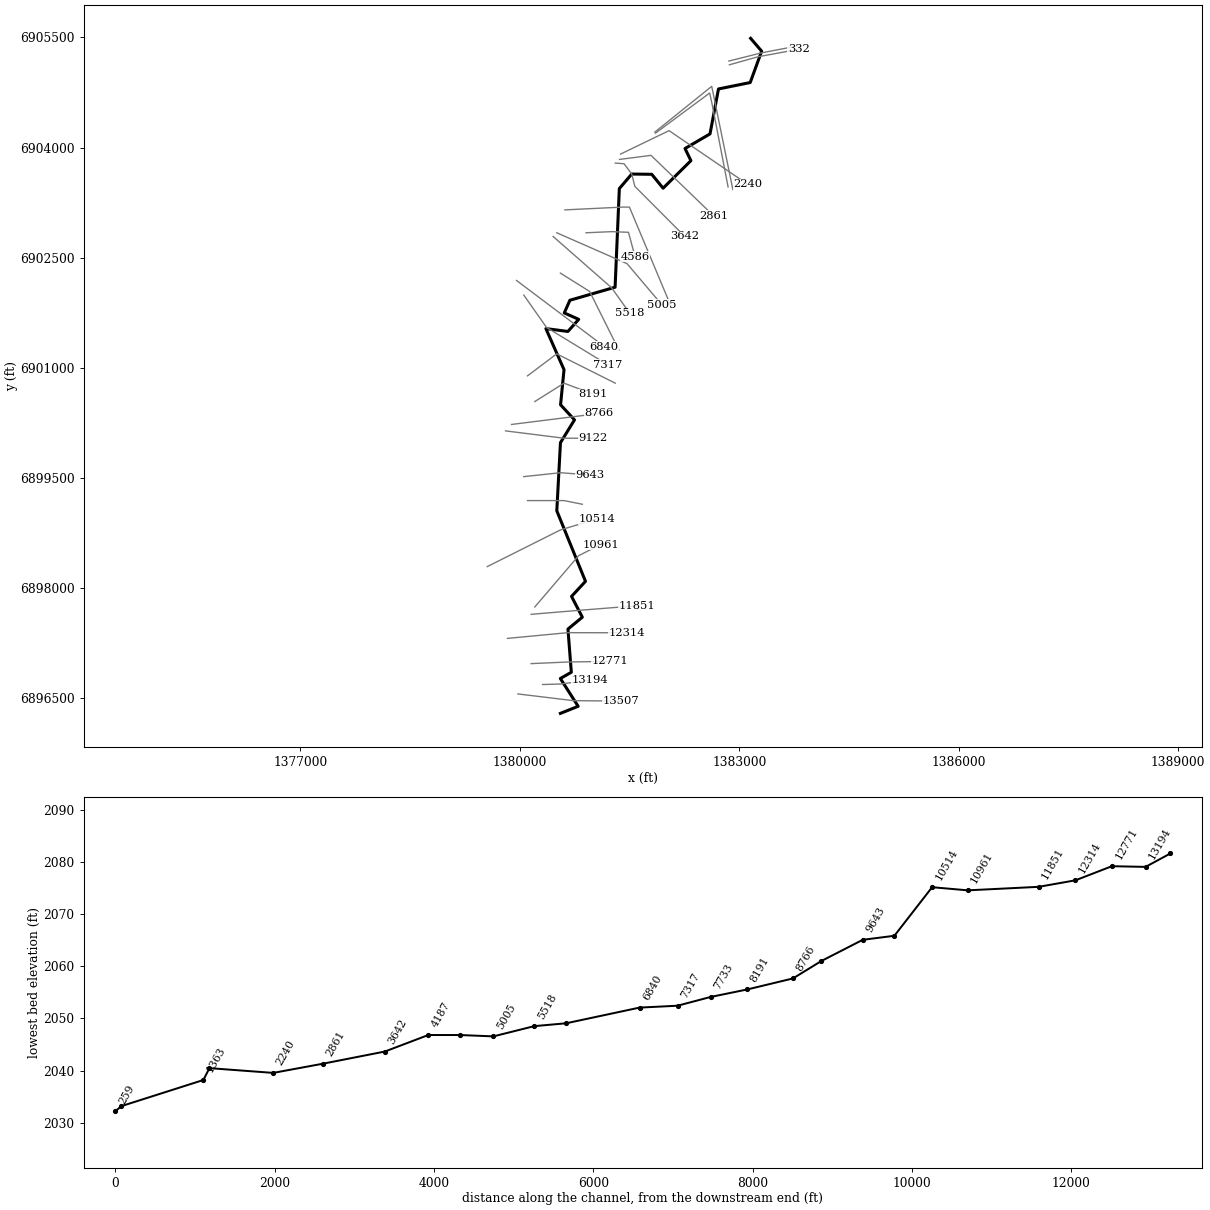
--- Plum Creek Trib1.prj (project) ---

Proj Title=Plum Creek Trib1 Base Level Engineering
Current Plan=p01
Default Exp/Contr=0.3,0.1
English Units
Geom File=g01
Flow File=f01
Plan File=p01
BEGIN DESCRIPTION:
Plum Creek Trib1
END DESCRIPTION:

--- Plum Creek Trib1.p01 (plan) ---

Plan Title=Multiple Run
Short Identifier=Multiple
Geom File=g01
Flow File=f01
Subcritical Flow
K Sum by GR= 0
Std Step Tol= 0.01
Critical Tol= 0.01
Num of Std Step Trials= 20
Max Error Tol= 0.3
Flow Tol Ratio= 0.001
Split Flow NTrial= 30
Split Flow Tol= 0.02
Split Flow Ratio= 0.02
Log Output Level= 0
Friction Slope Method= 1
Unsteady Friction Slope Method= 2
Unsteady Bridges Friction Slope Method= 1
Parabolic Critical Depth
Global Vel Dist=  1 , 1 , 1
Global Log Level= 0
CheckData=True
Encroach Param= -1, 0, 0, 0
BEGIN DESCRIPTION:
Multiple Run
END DESCRIPTION:

--- Plum Creek Trib1.f01 (steady flow) ---

Flow Title=Multiple
Number of Profiles=7
Profile Names=10-year,25-year,50-year,1pct_min,100-year,1pct_plu,500-year
River Rch & RM= Plum Creek Trib1,Reach-1,13507
     191     258     310     185     370     737     532
River Rch & RM= Plum Creek Trib1,Reach-1,10514
     340     475     586     359     715    1427    1081
River Rch & RM= Plum Creek Trib1,Reach-1,2240
     351     492     608     373     743    1483    1127
Boundary for River Rch & Prof#=Plum Creek Trib1,Reach-1,1
Up Type=0
Dn Type=3
Dn Slope=0.005
Boundary for River Rch & Prof#=Plum Creek Trib1,Reach-1,2
Up Type=0
Dn Type=3
Dn Slope=0.005
Boundary for River Rch & Prof#=Plum Creek Trib1,Reach-1,3
Up Type=0
Dn Type=3
Dn Slope=0.005
Boundary for River Rch & Prof#=Plum Creek Trib1,Reach-1,4
Up Type=0
Dn Type=3
Dn Slope=0.005
Boundary for River Rch & Prof#=Plum Creek Trib1,Reach-1,5
Up Type=0
Dn Type=3
Dn Slope=0.005
Boundary for River Rch & Prof#=Plum Creek Trib1,Reach-1,6
Up Type=0
Dn Type=3
Dn Slope=0.005
Boundary for River Rch & Prof#=Plum Creek Trib1,Reach-1,7
Up Type=0
Dn Type=3
Dn Slope=0.005

--- Plum Creek Trib1.g01 (geometry) ---

Geom Title=Existing Conditions

River Reach=Plum Creek Trib1,Reach-1
Reach XY= 30
      1380555.00      6896288.00      1380797.54      6896384.38
      1380554.39      6896763.31      1380704.13      6896848.31
      1380658.04      6897436.58      1380854.61      6897599.01
      1380707.14      6897882.04      1380897.77      6898087.69
      1380505.57      6899049.09      1380555.60      6899977.38
      1380747.49      6900288.04      1380557.23      6900493.90
      1380604.32      6900972.16      1380356.50      6901532.18
      1380657.30      6901493.09      1380805.22      6901658.06
      1380607.96      6901745.58      1380684.79      6901918.41
      1381302.50      6902096.15      1381360.47      6903440.45
      1381529.88      6903638.53      1381803.58      6903634.96
      1381958.57      6903445.48      1382338.96      6903820.96
      1382258.09      6903986.37      1382599.89      6904185.70
      1382715.61      6904798.07      1383149.48      6904885.56
      1383305.59      6905313.00      1383155.00      6905488.00

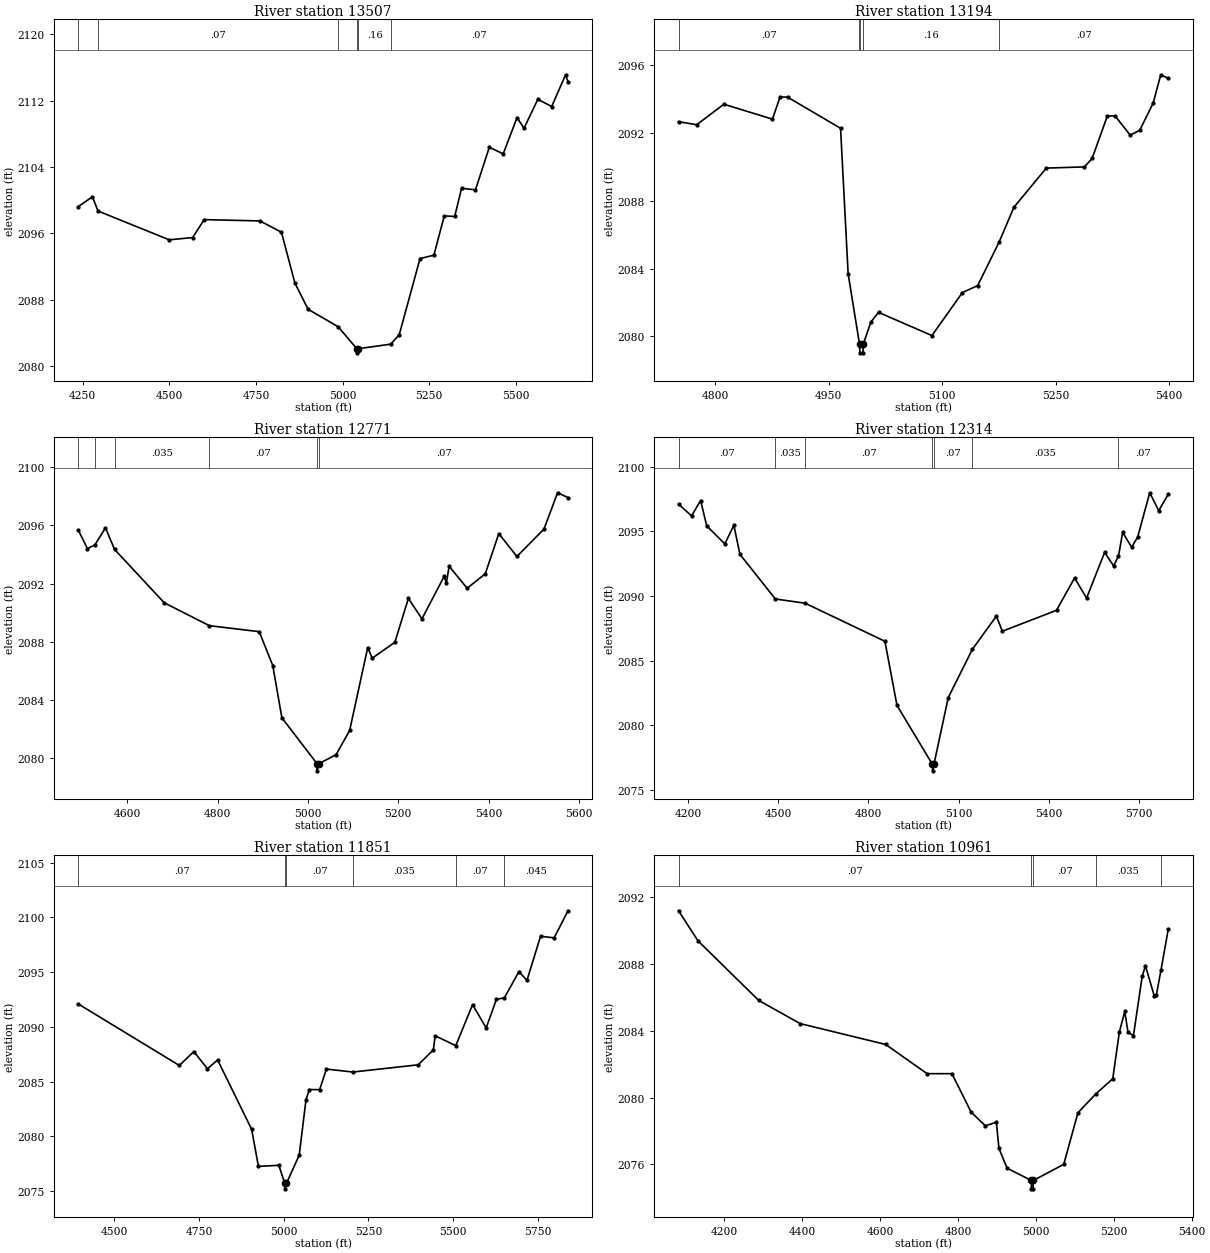
Type RM Length L Ch R = 1,13507,313,313,313
BEGIN DESCRIPTION:
Plum Creek Trib1 22.0
END DESCRIPTION:
XS GIS Cut Line= 3
      1379974.22      6896552.87      1380731.82      6896461.38
      1381381.99      6896455.66
#Sta/Elev= 30
  4236.9 2099.24  4278.0 2100.42  4293.9 2098.71  4499.6 2095.23  4567.2 2095.51
  4600.3 2097.67  4761.5 2097.51  4823.3 2096.15  4862.2 2090.01  4900.3 2086.85
  4986.7 2084.76  5040.8 2082.10  5041.1 2081.60  5045.6 2082.10  5138.9 2082.65
  5163.2 2083.78  5223.2 2092.97  5263.2 2093.38  5293.2 2098.12  5323.2 2098.05
  5343.2 2101.45  5383.2 2101.26  5423.2 2106.40  5463.2 2105.60  5503.2 2109.98
  5523.2 2108.68  5563.2 2112.18  5603.2 2111.31  5643.2 2115.14  5650.2 2114.30
#Mann=6,-1,0
  4236.9   0.035       0  4293.9    0.07       0  4986.7    0.16       0
  5040.8    0.07       0  5045.6    0.16       0  5138.9    0.07       0
Bank Sta=5040.8,5045.6
Exp/Cntr=0.3,0.1

Type RM Length L Ch R = 1,13194,423,423,423
BEGIN DESCRIPTION:
Plum Creek Trib1 21.0
END DESCRIPTION:
XS GIS Cut Line= 3
      1380310.97      6896681.34      1380555.00      6896688.00
      1380954.96      6896738.00
#Sta/Elev= 30
  4751.6 2092.67  4775.6 2092.49  4811.5 2093.70  4875.7 2092.82  4885.7 2094.13
  4895.7 2094.12  4965.7 2092.28  4975.7 2083.69  4990.6 2079.57  4990.8 2079.52
  4991.2 2079.02  4995.3 2079.02  4995.6 2079.52  5005.8 2080.84  5015.9 2081.41
  5086.4 2080.04  5126.7 2082.58  5146.9 2082.99  5175.4 2085.58  5194.8 2087.62
  5237.6 2089.93  5288.0 2090.00  5298.1 2090.50  5318.2 2093.00  5328.3 2093.02
  5348.4 2091.88  5361.0 2092.16  5378.7 2093.76  5388.8 2095.44  5398.8 2095.23
#Mann=5,-1,0
  4751.6    0.07       0  4990.6    0.16       0  4990.8    0.07       0
  4995.6    0.16       0  5175.4    0.07       0
Bank Sta=4990.8,4995.6
Exp/Cntr=0.3,0.1

Type RM Length L Ch R = 1,12771,457,457,457
BEGIN DESCRIPTION:
Plum Creek Trib1 20.0
END DESCRIPTION:
XS GIS Cut Line= 3
      1380154.77      6896966.06      1380655.00      6896988.00
      1381238.11      6896997.31
#Sta/Elev= 30
  4491.7 2095.68  4512.0 2094.40  4528.6 2094.65  4552.0 2095.83  4572.0 2094.35
  4682.1 2090.68  4782.1 2089.11  4892.3 2088.70  4922.3 2086.37  4942.4 2082.79
  5020.0 2079.65  5020.3 2079.15  5024.9 2079.65  5062.4 2080.26  5092.4 2081.92
  5132.4 2087.61  5142.4 2086.88  5192.4 2087.97  5222.4 2090.98  5252.4 2089.58
  5301.5 2092.49  5306.5 2092.04  5312.5 2093.19  5352.5 2091.68  5392.5 2092.67
  5422.5 2095.43  5462.5 2093.86  5522.5 2095.74  5552.5 2098.23  5575.6 2097.90
#Mann=6,-1,0
  4491.7   0.035       0  4528.6    0.07       0  4572.0   0.035       0
  4782.1    0.07       0  5020.0    0.07       0  5024.9    0.07       0
Bank Sta=5020,5024.9
Exp/Cntr=0.3,0.1

Type RM Length L Ch R = 1,12314,463,463,463
BEGIN DESCRIPTION:
Plum Creek Trib1 19.0
END DESCRIPTION:
XS GIS Cut Line= 3
      1379831.81      6897309.81      1380655.00      6897388.00
      1381456.80      6897386.20
#Sta/Elev= 30
  4168.9 2097.12  4212.3 2096.21  4242.4 2097.40  4262.5 2095.44  4322.8 2094.04
  4352.9 2095.48  4373.0 2093.23  4490.8 2089.77  4590.0 2089.44  4855.2 2086.49
  4895.3 2081.52  5013.3 2076.95  5013.7 2076.45  5018.2 2076.95  5065.8 2082.13
  5145.8 2085.86  5225.8 2088.44  5245.8 2087.27  5425.8 2088.89  5485.8 2091.40
  5525.8 2089.84  5585.8 2093.38  5615.8 2092.33  5631.9 2093.09  5645.8 2094.93
  5675.8 2093.78  5695.8 2094.58  5735.8 2098.00  5765.8 2096.61  5797.6 2097.90
#Mann=7,-1,0
  4168.9    0.07       0  4490.8   0.035       0  4590.0    0.07       0
  5013.3    0.07       0  5018.2    0.07       0  5145.8   0.035       0
  5631.9    0.07       0
Bank Sta=5013.3,5018.2
Exp/Cntr=0.3,0.1

Type RM Length L Ch R = 1,11851,890,890,890
BEGIN DESCRIPTION:
Plum Creek Trib1 18.0
END DESCRIPTION:
XS GIS Cut Line= 3
      1380155.00      6897638.00      1380755.00      6897688.00
      1381595.71      6897754.26
#Sta/Elev= 30
  4393.5 2092.09  4692.0 2086.47  4734.7 2087.74  4774.8 2086.17  4804.9 2086.97
  4905.3 2080.64  4925.3 2077.25  4985.5 2077.35  5003.1 2075.70  5003.5 2075.20
  5008.1 2075.70  5045.7 2078.28  5065.8 2083.36  5075.8 2084.27  5105.9 2084.26
  5126.0 2086.14  5204.2 2085.87  5396.8 2086.53  5441.5 2087.89  5447.0 2089.18
  5507.8 2088.28  5557.3 2092.03  5597.4 2089.90  5627.5 2092.50  5651.5 2092.66
  5694.2 2095.05  5717.8 2094.24  5757.9 2098.27  5798.1 2098.13  5838.9 2100.60
#Mann=6,-1,0
  4393.5    0.07       0  5003.1    0.07       0  5008.1    0.07       0
  5204.2   0.035       0  5507.8    0.07       0  5651.5   0.045       0
Bank Sta=5003.1,5008.1
Exp/Cntr=0.3,0.1

Type RM Length L Ch R = 1,10961,447,447,447
BEGIN DESCRIPTION:
Plum Creek Trib1 17.0
END DESCRIPTION:
XS GIS Cut Line= 3
      1380205.00      6897738.00      1380805.00      6898438.00
      1381105.03      6898588.02
#Sta/Elev= 30
  4082.5 2091.19  4132.4 2089.39  4288.3 2085.82  4394.8 2084.43  4614.3 2083.18
  4720.7 2081.43  4784.4 2081.43  4833.8 2079.12  4870.0 2078.31  4898.5 2078.52
  4905.1 2076.95  4926.0 2075.77  4988.2 2075.03  4988.6 2074.53  4992.9 2074.53
  4993.3 2075.03  5071.5 2076.00  5107.9 2079.09  5153.5 2080.21  5197.3 2081.13
  5214.1 2083.91  5228.1 2085.16  5236.4 2083.91  5250.4 2083.71  5272.8 2087.26
  5281.2 2087.90  5303.5 2086.11  5309.1 2086.14  5321.3 2087.66  5339.9 2090.10
#Mann=5,-1,0
  4082.5    0.07       0  4988.2    0.07       0  4993.3    0.07       0
  5153.5   0.035       0  5321.3    0.07       0
Bank Sta=4988.2,4993.3
Exp/Cntr=0.3,0.1

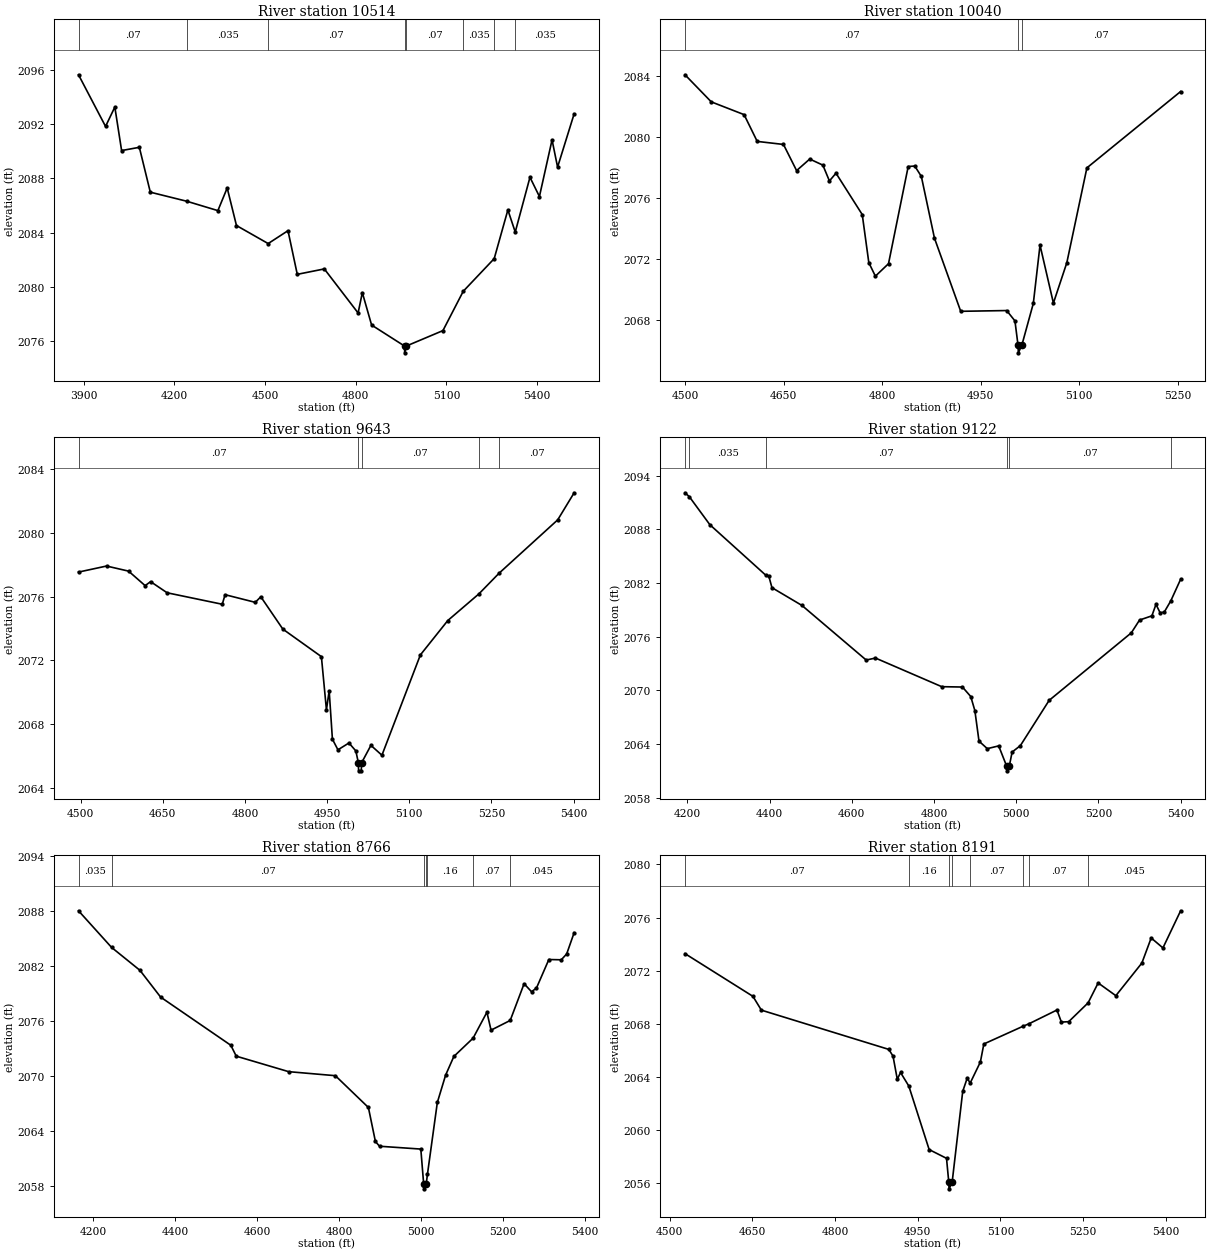
Type RM Length L Ch R = 1,10514,474,474,474
BEGIN DESCRIPTION:
Plum Creek Trib1 16.0
END DESCRIPTION:
XS GIS Cut Line= 3
      1379554.98      6898287.99      1380555.00      6898788.00
      1381055.03      6898938.01
#Sta/Elev= 30
  3882.4 2095.64  3971.9 2091.83  4002.6 2093.26  4025.0 2090.05  4083.7 2090.29
  4120.0 2086.98  4240.9 2086.31  4343.6 2085.62  4374.4 2087.29  4405.1 2084.52
  4510.0 2083.19  4575.6 2084.14  4606.3 2080.92  4695.8 2081.32  4807.6 2078.07
  4821.6 2079.57  4852.3 2077.18  4961.3 2075.63  4961.7 2075.13  4967.0 2075.63
  5088.3 2076.77  5155.5 2079.67  5258.0 2082.08  5303.2 2085.67  5327.6 2084.04
  5376.3 2088.08  5407.6 2086.66  5449.4 2090.84  5467.7 2088.83  5522.5 2092.76
#Mann=8,-1,0
  3882.4    0.07       0  4240.9   0.035       0  4510.0    0.07       0
  4961.3    0.07       0  4967.0    0.07       0  5155.5   0.035       0
  5258.0    0.07       0  5327.6   0.035       0
Bank Sta=4961.3,4967
Exp/Cntr=0.3,0.1

Type RM Length L Ch R = 1,10040,397,397,397
BEGIN DESCRIPTION:
Plum Creek Trib1 15.0
END DESCRIPTION:
XS GIS Cut Line= 3
      1380104.96      6899188.00      1380605.00      6899188.00
      1380855.01      6899138.00
#Sta/Elev= 30
  4499.5 2084.11  4539.5 2082.33  4589.5 2081.49  4609.5 2079.73  4649.5 2079.53
  4669.5 2077.81  4689.5 2078.57  4709.5 2078.17  4719.5 2077.13  4729.5 2077.64
  4769.5 2074.92  4779.5 2071.76  4789.5 2070.87  4809.5 2071.69  4839.5 2078.08
  4849.5 2078.11  4859.5 2077.43  4879.5 2073.37  4919.5 2068.56  4989.5 2068.61
  5002.1 2067.93  5006.8 2066.33  5007.3 2065.83  5012.6 2066.33  5030.1 2069.08
  5040.3 2072.91  5060.7 2069.10  5081.1 2071.75  5111.7 2077.99  5254.5 2083.01
#Mann=3,-1,0
  4499.5    0.07       0  5006.8    0.07       0  5012.6    0.07       0
Bank Sta=5006.8,5012.6
Exp/Cntr=0.3,0.1

Type RM Length L Ch R = 1,9643,521,521,521
BEGIN DESCRIPTION:
Plum Creek Trib1 14.0
END DESCRIPTION:
XS GIS Cut Line= 3
      1380054.10      6899514.68      1380555.07      6899567.97
      1380954.95      6899538.00
#Sta/Elev= 30
  4496.2 2077.54  4547.4 2077.92  4587.6 2077.60  4617.8 2076.69  4627.8 2076.94
  4658.0 2076.24  4758.6 2075.52  4763.8 2076.12  4818.9 2075.64  4829.0 2075.99
  4869.2 2073.96  4939.6 2072.23  4948.8 2068.89  4953.8 2070.09  4959.7 2067.05
  4969.8 2066.38  4989.9 2066.81  5002.5 2066.31  5007.1 2065.56  5007.5 2065.06
  5012.4 2065.06  5012.9 2065.56  5030.0 2066.66  5050.1 2066.04  5120.3 2072.34
  5170.4 2074.50  5227.1 2076.17  5264.0 2077.47  5371.0 2080.82  5401.0 2082.52
#Mann=5,-1,0
  4496.2    0.07       0  5007.1    0.07       0  5012.9    0.07       0
  5227.1   0.045       0  5264.0    0.07       0
Bank Sta=5007.1,5012.9
Exp/Cntr=0.3,0.1

Type RM Length L Ch R = 1,9122,356,356,356
BEGIN DESCRIPTION:
Plum Creek Trib1 13.0
END DESCRIPTION:
XS GIS Cut Line= 3
      1379805.00      6900138.00      1380605.00      6900038.00
      1381004.97      6900038.00
#Sta/Elev= 30
  4194.1 2092.08  4204.5 2091.65  4254.6 2088.51  4391.0 2082.85  4398.2 2082.74
  4405.7 2081.47  4478.8 2079.48  4635.0 2073.38  4657.7 2073.60  4818.9 2070.40
  4869.3 2070.36  4889.5 2069.30  4899.5 2067.73  4909.6 2064.31  4929.8 2063.47
  4957.5 2063.78  4977.1 2061.49  4977.6 2060.99  4983.2 2061.49  4990.2 2063.09
  5010.3 2063.81  5080.3 2068.87  5280.3 2076.42  5300.3 2077.85  5330.3 2078.32
  5340.3 2079.60  5350.3 2078.67  5360.3 2078.73  5376.3 2079.99  5400.3 2082.41
#Mann=6,-1,0
  4194.1    0.07       0  4204.5   0.035       0  4391.0    0.07       0
  4977.1    0.07       0  4983.2    0.07       0  5376.3   0.045       0
Bank Sta=4977.1,4983.2
Exp/Cntr=0.3,0.1

Type RM Length L Ch R = 1,8766,575,575,575
BEGIN DESCRIPTION:
Plum Creek Trib1 12.0
END DESCRIPTION:
XS GIS Cut Line= 3
      1379886.24      6900225.50      1380686.25      6900325.50
      1381086.20      6900375.49
#Sta/Elev= 30
  4163.6 2088.01  4244.3 2084.01  4313.5 2081.51  4363.9 2078.59  4535.2 2073.33
  4548.5 2072.14  4676.3 2070.45  4790.3 2070.01  4870.9 2066.54  4888.0 2062.83
  4898.0 2062.31  4998.8 2062.00  5005.8 2058.16  5006.3 2057.66  5011.9 2058.16
  5015.1 2059.29  5039.1 2067.09  5059.3 2070.07  5079.4 2072.11  5126.4 2074.11
  5160.1 2076.94  5170.1 2074.98  5216.9 2076.04  5250.8 2080.05  5269.0 2079.17
  5281.0 2079.58  5311.2 2082.69  5341.5 2082.66  5354.7 2083.30  5372.9 2085.62
#Mann=7,-1,0
  4163.6   0.035       0  4244.3    0.07       0  5005.8    0.07       0
  5011.9    0.07       0  5015.1    0.16       0  5126.4    0.07       0
  5216.9   0.045       0
Bank Sta=5005.8,5011.9
Exp/Cntr=0.3,0.1

Type RM Length L Ch R = 1,8191,458,458,458
BEGIN DESCRIPTION:
Plum Creek Trib1 11.0
END DESCRIPTION:
XS GIS Cut Line= 3
      1380205.03      6900538.02      1380605.00      6900788.00
      1381005.03      6900637.99
#Sta/Elev= 30
  4527.9 2073.28  4651.1 2070.06  4666.4 2069.02  4897.6 2066.06  4905.2 2065.55
  4912.9 2063.81  4918.8 2064.32  4933.8 2063.30  4970.7 2058.51  5002.2 2057.85
  5006.3 2056.05  5006.8 2055.55  5012.4 2056.05  5031.6 2062.90  5039.6 2063.88
  5045.2 2063.53  5063.6 2065.11  5069.9 2066.47  5140.7 2067.80  5152.1 2068.00
  5202.5 2069.03  5210.5 2068.12  5223.8 2068.15  5259.0 2069.57  5277.2 2071.07
  5309.3 2070.11  5356.5 2072.57  5373.4 2074.46  5394.7 2073.71  5426.8 2076.51
#Mann=8,-1,0
  4527.9    0.07       0  4933.8    0.16       0  5006.3    0.07       0
  5012.4    0.16       0  5045.2    0.07       0  5140.7    0.16       0
  5152.1    0.07       0  5259.0   0.045       0
Bank Sta=5006.3,5012.4
Exp/Cntr=0.3,0.1

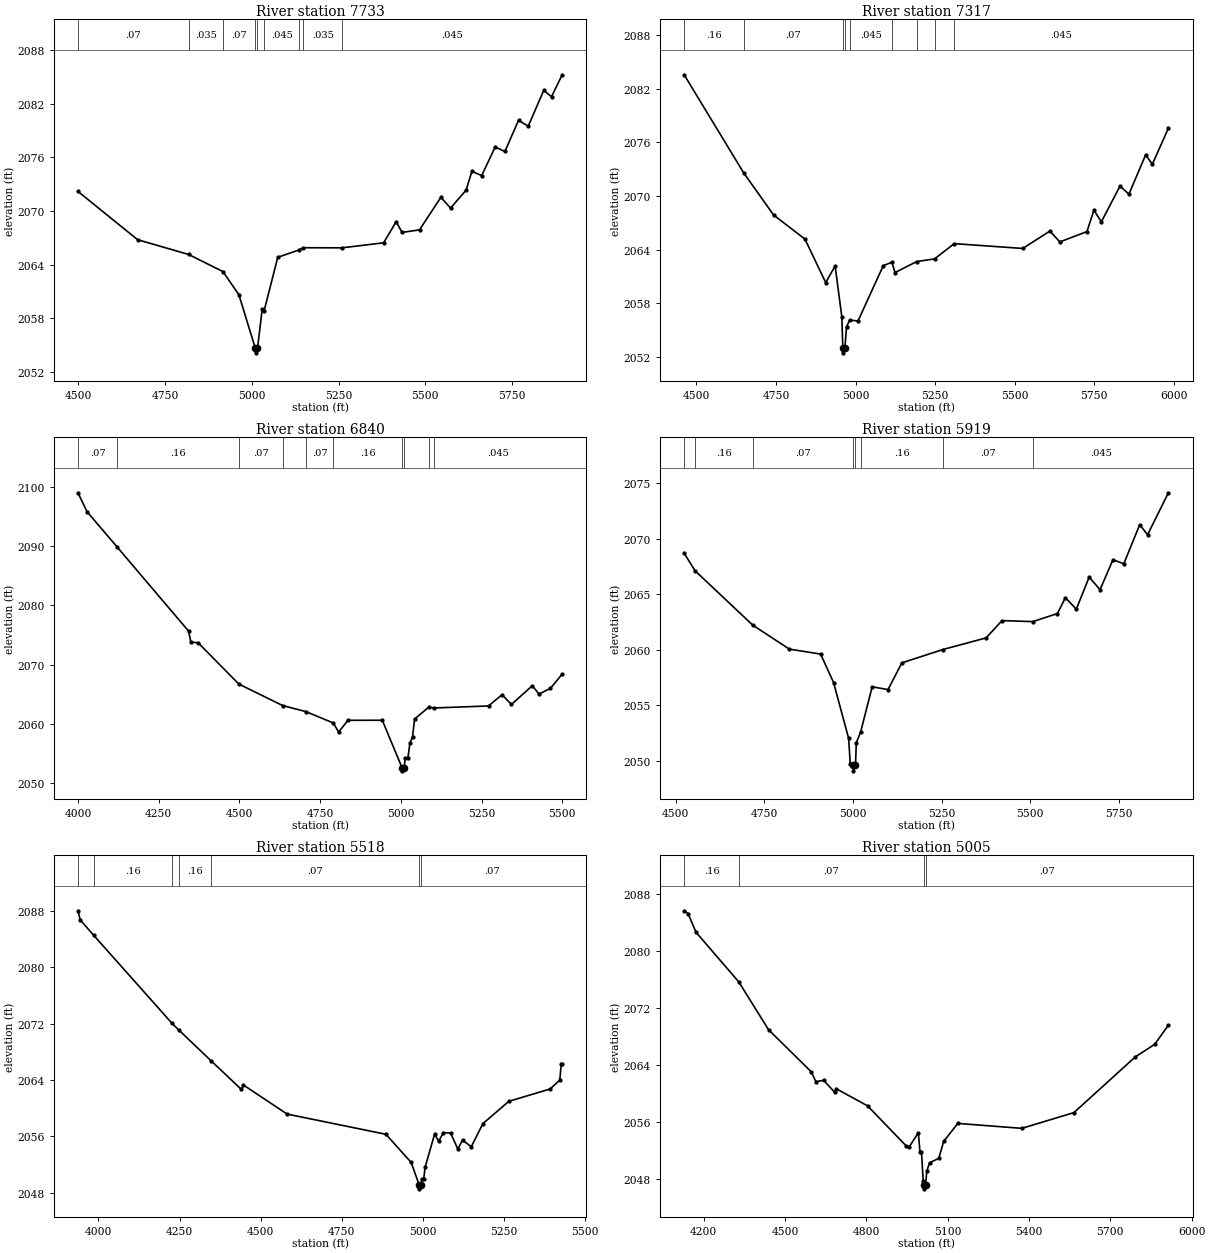
Type RM Length L Ch R = 1,7733,416,416,416
BEGIN DESCRIPTION:
Plum Creek Trib1 10.0
END DESCRIPTION:
XS GIS Cut Line= 3
      1380105.04      6900888.03      1380505.00      6901188.00
      1381305.02      6900787.99
#Sta/Elev= 30
  4499.6 2072.20  4671.4 2066.79  4818.1 2065.14  4917.2 2063.22  4963.1 2060.62
  5010.4 2054.62  5010.9 2054.12  5016.6 2054.62  5030.3 2059.05  5035.5 2058.80
  5075.0 2064.82  5136.0 2065.64  5147.9 2065.89  5260.2 2065.88  5379.7 2066.44
  5416.0 2068.81  5432.8 2067.61  5483.1 2067.89  5544.6 2071.54  5572.5 2070.33
  5617.3 2072.34  5634.0 2074.45  5662.0 2073.97  5701.1 2077.17  5729.1 2076.67
  5768.2 2080.16  5796.2 2079.50  5840.9 2083.52  5863.2 2082.80  5894.0 2085.26
#Mann=9,-1,0
  4499.6    0.07       0  4818.1   0.035       0  4917.2    0.07       0
  5010.4    0.07       0  5016.6    0.07       0  5035.5   0.045       0
  5136.0    0.07       0  5147.9   0.035       0  5260.2   0.045       0
Bank Sta=5010.4,5016.6
Exp/Cntr=0.3,0.1

Type RM Length L Ch R = 1,7317,477,477,477
BEGIN DESCRIPTION:
Plum Creek Trib1 9.0
END DESCRIPTION:
XS GIS Cut Line= 3
      1380054.98      6901988.03      1380365.04      6901548.11
      1381204.98      6901038.01
#Sta/Elev= 30
  4461.8 2083.58  4649.2 2072.57  4742.7 2067.88  4841.1 2065.18  4906.4 2060.31
  4936.0 2062.17  4956.9 2056.49  4960.2 2052.94  4960.7 2052.44  4966.6 2052.94
  4971.7 2055.34  4981.6 2056.11  5007.8 2056.01  5087.3 2062.21  5114.3 2062.58
  5124.1 2061.43  5192.1 2062.66  5248.2 2062.96  5310.0 2064.67  5525.3 2064.13
  5610.6 2066.08  5641.6 2064.86  5726.9 2066.02  5748.7 2068.42  5772.1 2067.11
  5830.6 2071.11  5858.7 2070.21  5911.0 2074.60  5932.3 2073.56  5982.7 2077.60
#Mann=9,-1,0
  4461.8    0.16       0  4649.2    0.07       0  4960.2   0.045       0
  4966.6    0.07       0  4981.6   0.045       0  5114.3    0.07       0
  5192.1    0.16       0  5248.2    0.07       0  5310.0   0.045       0
Bank Sta=4960.2,4966.6
Exp/Cntr=0.3,0.1

Type RM Length L Ch R = 1,6840,921,921,921
BEGIN DESCRIPTION:
Plum Creek Trib1 8.0
END DESCRIPTION:
XS GIS Cut Line= 3
      1379954.98      6902188.02      1380755.00      6901588.00
      1381154.98      6901288.02
#Sta/Elev= 30
  3999.7 2098.96  4027.9 2095.77  4120.9 2089.83  4342.4 2075.64  4349.7 2073.76
  4371.6 2073.69  4498.1 2066.71  4633.6 2063.09  4706.2 2062.06  4790.9 2060.14
  4807.0 2058.62  4836.2 2060.60  4942.4 2060.61  5003.8 2052.58  5004.3 2052.08
  5010.2 2052.58  5013.3 2054.22  5021.6 2054.20  5027.9 2056.74  5036.2 2057.83
  5042.4 2060.81  5085.7 2062.79  5103.0 2062.68  5271.6 2063.02  5313.3 2064.92
  5342.4 2063.27  5407.0 2066.43  5427.9 2065.03  5463.3 2065.99  5499.7 2068.40
#Mann=10,-1,0
  3999.7    0.07       0  4120.9    0.16       0  4498.1    0.07       0
  4633.6    0.16       0  4706.2    0.07       0  4790.9    0.16       0
  5003.8    0.07       0  5010.2    0.16       0  5085.7    0.07       0
  5103.0   0.045       0
Bank Sta=5003.8,5010.2
Exp/Cntr=0.3,0.1

Type RM Length L Ch R = 1,5919,401,401,401
BEGIN DESCRIPTION:
Plum Creek Trib1 7.0
END DESCRIPTION:
XS GIS Cut Line= 3
      1380555.00      6902288.00      1380955.00      6902038.00
      1381354.99      6901238.02
#Sta/Elev= 30
  4523.7 2068.71  4554.4 2067.13  4716.9 2062.23  4820.3 2060.06  4908.7 2059.61
  4945.3 2057.04  4987.7 2052.01  4992.4 2049.67  5000.6 2049.58  5001.1 2049.08
  5007.0 2049.58  5009.4 2051.62  5021.5 2052.58  5054.1 2056.66  5098.8 2056.41
  5137.9 2058.82  5253.4 2060.02  5375.5 2061.07  5420.3 2062.63  5507.5 2062.54
  5576.8 2063.27  5599.1 2064.70  5629.9 2063.66  5666.2 2066.55  5697.0 2065.42
  5733.3 2068.12  5764.0 2067.76  5808.8 2071.28  5831.1 2070.38  5889.8 2074.16
#Mann=8,-1,0
  4523.7    0.07       0  4554.4    0.16       0  4716.9    0.07       0
  5000.6    0.07       0  5007.0    0.07       0  5021.5    0.16       0
  5253.4    0.07       0  5507.5   0.045       0
Bank Sta=5000.6,5007
Exp/Cntr=0.3,0.1

Type RM Length L Ch R = 1,5518,513,513,513
BEGIN DESCRIPTION:
Plum Creek Trib1 6.0
END DESCRIPTION:
XS GIS Cut Line= 3
      1380454.97      6902788.03      1381255.00      6902088.00
      1381505.02      6901737.98
#Sta/Elev= 30
  3936.7 2088.03  3943.9 2086.72  3985.4 2084.54  4227.2 2072.02  4248.0 2071.08
  4347.7 2066.70  4440.2 2062.67  4446.9 2063.28  4581.7 2059.15  4886.3 2056.28
  4964.2 2052.28  4989.3 2049.03  4989.8 2048.53  4995.9 2049.03  4996.4 2049.90
  5002.8 2049.90  5007.1 2051.59  5036.6 2056.32  5048.9 2055.29  5063.7 2056.51
  5085.8 2056.46  5107.9 2054.20  5122.6 2055.43  5149.7 2054.52  5185.3 2057.79
  5265.2 2060.96  5393.0 2062.72  5422.5 2063.99  5426.8 2066.25  5429.9 2066.25
#Mann=7,-1,0
  3936.7    0.07       0  3985.4    0.16       0  4227.2    0.07       0
  4248.0    0.16       0  4347.7    0.07       0  4989.3    0.07       0
  4995.9    0.07       0
Bank Sta=4989.3,4995.9
Exp/Cntr=0.3,0.1

Type RM Length L Ch R = 1,5005,419,419,419
BEGIN DESCRIPTION:
Plum Creek Trib1 5.0
END DESCRIPTION:
XS GIS Cut Line= 4
      1380504.97      6902838.01      1381304.19      6902488.00
      1381466.05      6902416.95      1381943.45      6901854.91
#Sta/Elev= 30
  4127.5 2085.59  4142.0 2085.20  4171.2 2082.58  4329.1 2075.61  4438.9 2068.90
  4597.0 2062.97  4613.5 2061.61  4642.3 2061.80  4683.6 2060.09  4689.1 2060.61
  4804.4 2058.21  4946.3 2052.61  4957.2 2052.42  4991.5 2054.44  4997.7 2051.75
  5003.2 2051.75  5009.4 2047.74  5011.6 2047.07  5012.1 2046.57  5018.2 2047.07
  5022.7 2049.03  5032.8 2050.22  5067.0 2050.85  5084.9 2053.22  5137.1 2055.75
  5373.5 2055.06  5565.7 2057.27  5792.1 2065.09  5863.4 2066.84  5914.2 2069.54
#Mann=4,-1,0
  4127.5    0.16       0  4329.1    0.07       0  5011.6    0.07       0
  5018.2    0.07       0
Bank Sta=5011.6,5018.2
Exp/Cntr=0.3,0.1

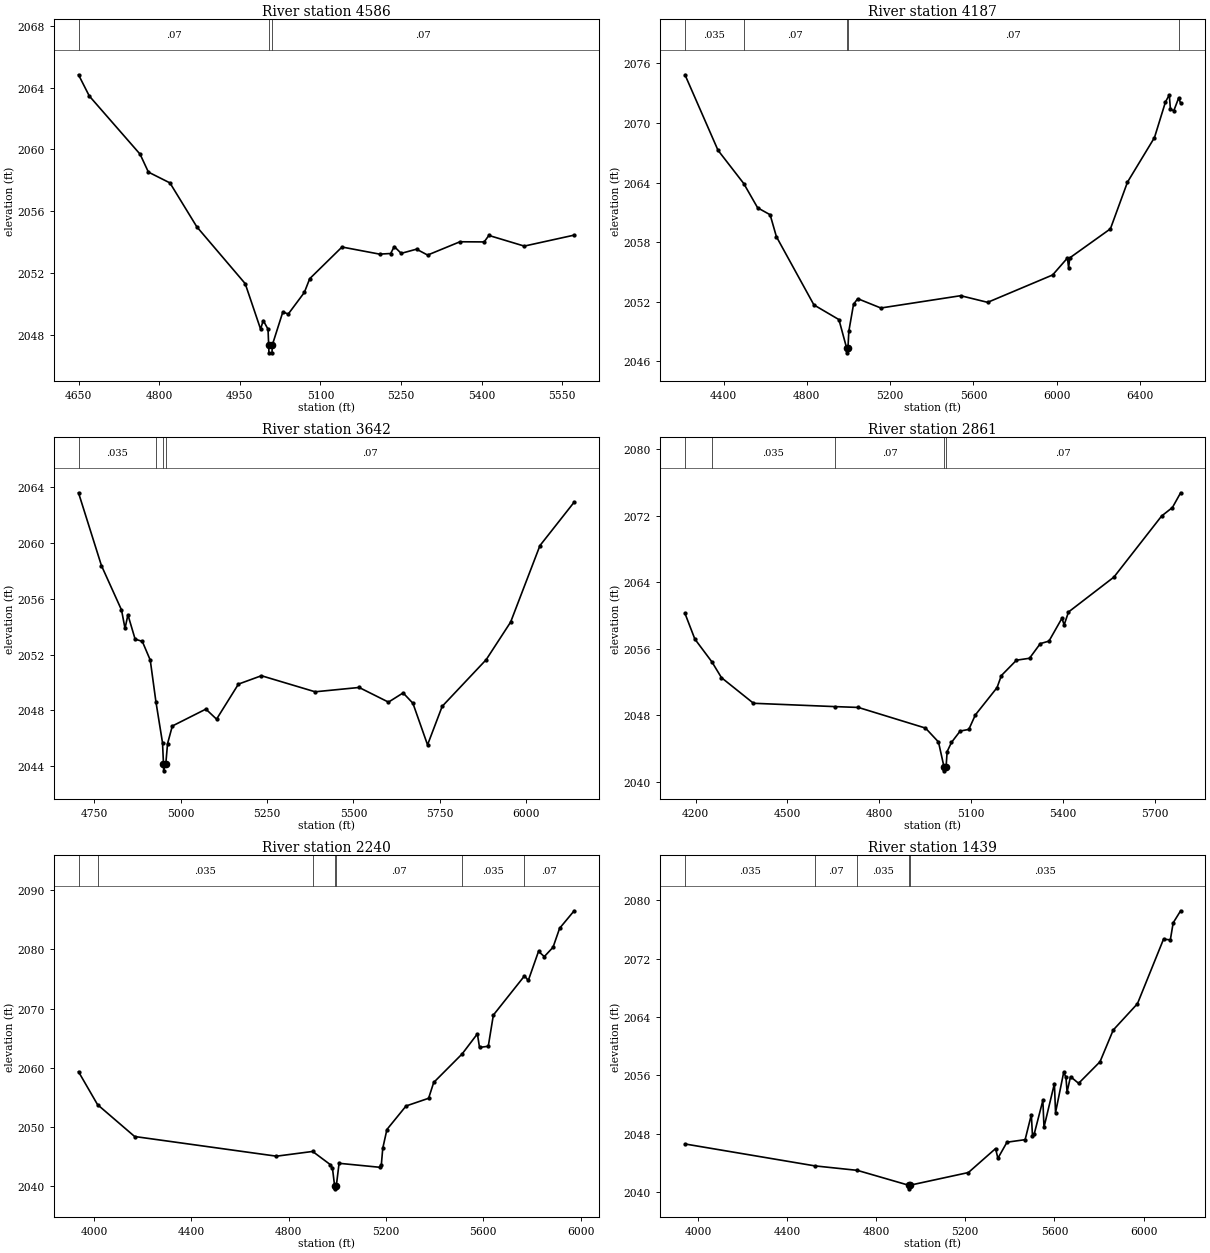
Type RM Length L Ch R = 1,4586,399,399,399
BEGIN DESCRIPTION:
Plum Creek Trib1 4.0
END DESCRIPTION:
XS GIS Cut Line= 4
      1380904.99      6902838.00      1381254.95      6902853.35
      1381485.58      6902844.47      1381574.54      6902514.65
#Sta/Elev= 30
  4649.7 2064.83  4669.7 2063.46  4764.3 2059.69  4779.8 2058.53  4819.9 2057.83
  4869.9 2054.99  4960.0 2051.31  4988.6 2048.37  4993.6 2048.92  5002.5 2048.36
  5003.7 2047.33  5004.2 2046.83  5009.9 2046.83  5010.4 2047.33  5030.1 2049.48
  5040.1 2049.34  5070.1 2050.74  5080.1 2051.63  5140.2 2053.68  5210.2 2053.22
  5230.8 2053.26  5237.5 2053.71  5250.4 2053.27  5278.9 2053.54  5299.6 2053.16
  5359.8 2054.02  5404.9 2054.01  5413.6 2054.43  5479.5 2053.74  5572.4 2054.45
#Mann=3,-1,0
  4649.7    0.07       0  5003.7    0.07       0  5010.4    0.07       0
Bank Sta=5003.7,5010.4
Exp/Cntr=0.3,0.1

Type RM Length L Ch R = 1,4187,545,545,545
BEGIN DESCRIPTION:
Plum Creek Trib1 3.0
END DESCRIPTION:
XS GIS Cut Line= 4
      1380616.55      6903150.09      1381405.00      6903188.00
      1381498.21      6903188.07      1382078.91      6901807.72
#Sta/Elev= 30
  4214.8 2074.86  4373.4 2067.25  4496.9 2063.90  4563.7 2061.45  4623.7 2060.75
  4653.8 2058.54  4834.0 2051.66  4954.1 2050.18  4990.8 2047.33  4991.3 2046.83
  4997.5 2047.33  5001.7 2049.02  5024.2 2051.72  5044.2 2052.29  5155.3 2051.35
  5538.6 2052.59  5668.2 2051.92  5980.2 2054.68  6051.4 2056.39  6056.9 2055.42
  6063.0 2056.41  6257.7 2059.33  6339.7 2064.04  6469.3 2068.53  6522.2 2072.13
  6540.4 2072.83  6546.0 2071.37  6562.1 2071.24  6585.5 2072.52  6594.9 2071.99
#Mann=5,-1,0
  4214.8   0.035       0  4496.9    0.07       0  4990.8    0.07       0
  4997.5    0.07       0  6585.5   0.045       0
Bank Sta=4990.8,4997.5
Exp/Cntr=0.3,0.1

Type RM Length L Ch R = 1,3642,781,781,781
BEGIN DESCRIPTION:
Plum Creek Trib1 2.0
END DESCRIPTION:
XS GIS Cut Line= 5
      1381304.98      6903788.00      1381425.28      6903779.04
      1381529.88      6903638.53      1381572.49      6903470.51
      1382255.03      6902787.97
#Sta/Elev= 30
  4704.2 2063.58  4770.5 2058.37  4828.6 2055.19  4838.8 2053.87  4847.2 2054.84
  4868.0 2053.10  4888.8 2052.94  4911.8 2051.60  4928.2 2048.62  4947.3 2045.68
  4950.1 2044.17  4950.6 2043.67  4956.8 2044.17  4961.9 2045.62  4975.7 2046.88
  5072.8 2048.09  5103.7 2047.37  5167.0 2049.88  5233.5 2050.48  5389.0 2049.33
  5516.3 2049.64  5601.2 2048.59  5643.6 2049.25  5671.9 2048.51  5714.3 2045.53
  5756.7 2048.29  5884.0 2051.63  5954.7 2054.32  6039.6 2059.80  6138.6 2062.91
#Mann=4,-1,0
  4704.2   0.035       0  4928.2    0.07       0  4950.1    0.07       0
  4956.8    0.07       0
Bank Sta=4950.1,4956.8
Exp/Cntr=0.3,0.1

Type RM Length L Ch R = 1,2861,621,621,621
BEGIN DESCRIPTION:
Mapping XS 52b706dd
END DESCRIPTION:
XS GIS Cut Line= 3
      1381363.09      6903837.59      1381793.64      6903893.15
      1382646.37      6903071.61
#Sta/Elev= 30
  4165.3 2060.25  4197.5 2057.17  4253.3 2054.42  4284.4 2052.53  4389.0 2049.45
  4654.9 2049.05  4731.3 2048.95  4950.5 2046.47  4992.9 2044.80  5010.8 2041.83
  5011.3 2041.33  5017.8 2041.83  5021.2 2043.64  5035.4 2044.75  5063.7 2046.11
  5092.0 2046.31  5113.3 2048.05  5184.1 2051.33  5198.2 2052.78  5247.6 2054.63
  5290.1 2054.86  5325.3 2056.62  5353.6 2056.92  5396.0 2059.67  5403.2 2058.87
  5417.4 2060.42  5565.8 2064.62  5721.5 2071.96  5756.7 2072.98  5783.5 2074.75
#Mann=5,-1,0
  4165.3    0.07       0  4253.3   0.035       0  4654.9    0.07       0
  5010.8    0.07       0  5017.8    0.07       0
Bank Sta=5010.8,5017.8
Exp/Cntr=0.3,0.1

Type RM Length L Ch R = 1,2240,801,801,801
BEGIN DESCRIPTION:
Mapping XS 65d0930d
END DESCRIPTION:
XS GIS Cut Line= 3
      1381376.94      6903910.49      1382040.16      6904229.95
      1383116.54      6903497.32
#Sta/Elev= 30
  3935.6 2059.34  4014.0 2053.78  4166.4 2048.41  4749.7 2045.09  4898.4 2045.89
  4971.2 2043.66  4980.0 2043.02  4988.7 2040.08  4989.2 2039.58  4995.7 2040.08
  5007.1 2043.89  5173.6 2043.22  5180.7 2043.56  5186.7 2046.42  5203.8 2049.59
  5282.4 2053.56  5375.2 2054.86  5396.2 2057.53  5513.2 2062.35  5575.8 2065.73
  5584.6 2063.44  5620.6 2063.64  5641.5 2068.90  5769.5 2075.51  5785.2 2074.74
  5827.2 2079.65  5851.0 2078.77  5886.9 2080.34  5914.0 2083.55  5973.8 2086.50
#Mann=7,-1,0
  3935.6    0.07       0  4014.0   0.035       0  4898.4    0.07       0
  4988.7    0.07       0  4995.7    0.07       0  5513.2   0.035       0
  5769.5    0.07       0
Bank Sta=4988.7,4995.7
Exp/Cntr=0.3,0.1

Type RM Length L Ch R = 1,1439,76,76,76
BEGIN DESCRIPTION:
Mapping XS de71923c
END DESCRIPTION:
XS GIS Cut Line= 4
      1381855.13      6904195.85      1382595.17      6904742.74
      1382627.72      6904595.17      1382846.84      6903462.67
#Sta/Elev= 30
  3941.7 2046.63  4525.0 2043.63  4715.2 2043.02  4945.1 2040.99  4945.6 2040.49
  4952.2 2040.99  5213.8 2042.72  5335.9 2046.00  5346.2 2044.67  5387.0 2046.87
  5468.5 2047.22  5496.4 2050.64  5501.4 2047.78  5509.2 2047.99  5548.1 2052.59
  5553.2 2048.92  5599.9 2054.89  5605.0 2050.92  5641.6 2056.44  5651.7 2055.76
  5656.8 2053.75  5672.2 2055.84  5708.6 2054.93  5804.6 2057.88  5863.9 2062.22
  5972.6 2065.82  6089.8 2074.66  6120.3 2074.56  6133.0 2076.89  6166.5 2078.54
#Mann=5,-1,0
  3941.7   0.035       0  4525.0    0.07       0  4715.2   0.035       0
  4945.1   0.035       0  4952.2   0.035       0
Bank Sta=4945.1,4952.2
Exp/Cntr=0.3,0.1

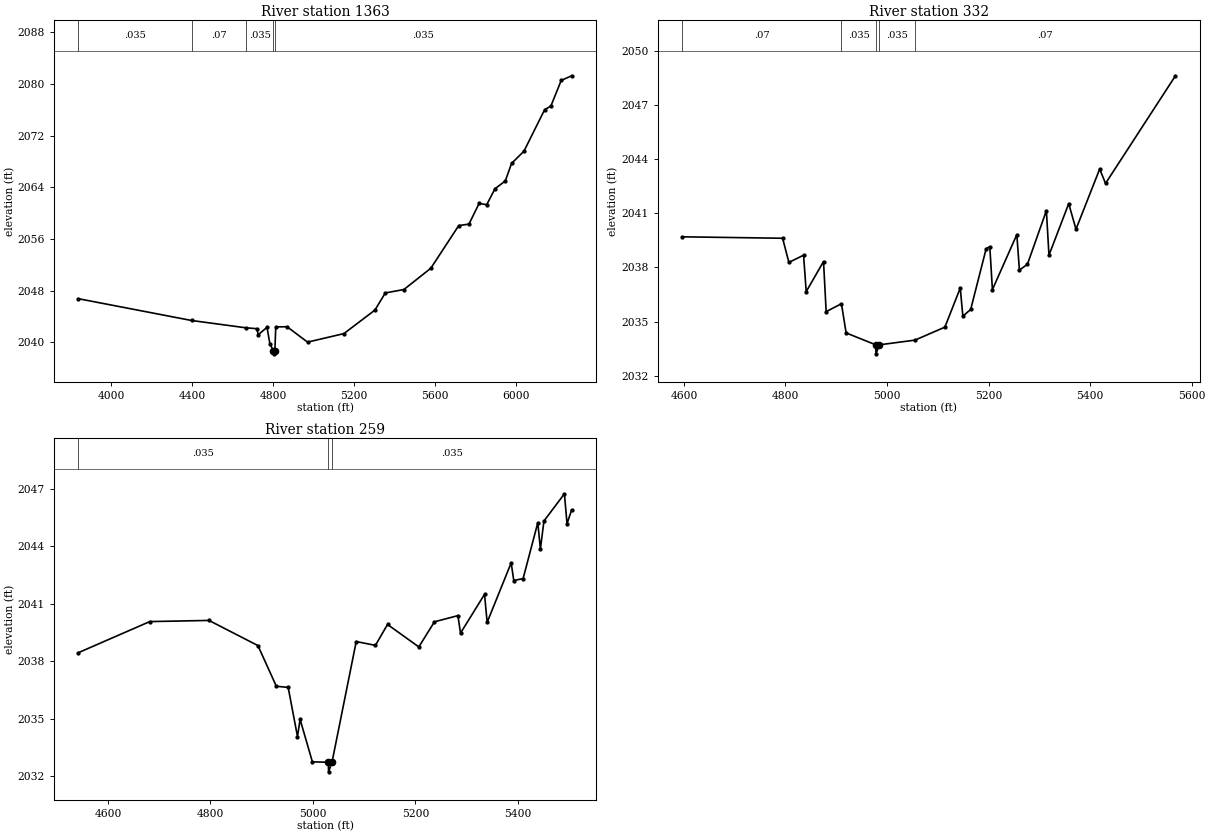
Type RM Length L Ch R = 1,1363,1031,1031,1031
BEGIN DESCRIPTION:
Plum Creek Trib1 1.0
END DESCRIPTION:
XS GIS Cut Line= 3
      1381845.49      6904209.91      1382623.38      6904833.88
      1382912.01      6903427.62
#Sta/Elev= 30
  3839.7 2046.75  4397.8 2043.38  4665.2 2042.25  4720.4 2042.11  4726.8 2041.18
  4770.0 2042.32  4784.4 2039.73  4801.7 2038.72  4802.2 2038.22  4808.8 2038.72
  4813.2 2042.39  4869.2 2042.41  4969.9 2040.03  5149.2 2041.35  5302.3 2044.99
  5353.4 2047.64  5445.2 2048.17  5577.9 2051.46  5715.6 2058.06  5766.0 2058.29
  5816.4 2061.50  5853.6 2061.29  5894.4 2063.76  5945.4 2064.97  5976.1 2067.68
  6037.3 2069.57  6139.4 2076.00  6170.0 2076.55  6221.1 2080.52  6272.5 2081.24
#Mann=5,-1,0
  3839.7   0.035       0  4397.8    0.07       0  4665.2   0.035       0
  4801.7   0.035       0  4808.8   0.035       0
Bank Sta=4801.7,4808.8
Exp/Cntr=0.3,0.1

Type RM Length L Ch R = 1,332,73,73,73
BEGIN DESCRIPTION:
Mapping XS 0eeb18a4
END DESCRIPTION:
XS GIS Cut Line= 3
      1382864.59      6905127.18      1383254.36      6905236.37
      1383811.71      6905338.49
#Sta/Elev= 30
  4596.7 2039.70  4794.4 2039.62  4806.8 2038.28  4835.7 2038.68  4840.9 2036.66
  4875.0 2038.33  4880.2 2035.55  4910.3 2035.99  4919.5 2034.37  4977.8 2033.71
  4978.3 2033.21  4985.0 2033.71  5055.0 2033.97  5114.0 2034.69  5144.3 2036.86
  5149.4 2035.30  5164.8 2035.67  5195.3 2039.04  5202.5 2039.15  5207.6 2036.77
  5255.7 2039.82  5260.8 2037.85  5276.6 2038.18  5313.9 2041.15  5319.0 2038.68
  5357.9 2041.54  5372.2 2040.12  5418.9 2043.46  5430.4 2042.66  5568.1 2048.63
#Mann=5,-1,0
  4596.7    0.07       0  4910.3   0.035       0  4977.8   0.035       0
  4985.0   0.035       0  5055.0    0.07       0
Bank Sta=4977.8,4985
Exp/Cntr=0.3,0.1

Type RM Length L Ch R = 1,259,0,0,0
BEGIN DESCRIPTION:
Mapping XS 45f7c13c
END DESCRIPTION:
XS GIS Cut Line= 3
      1382857.59      6905178.46      1383301.89      6905289.65
      1383798.15      6905384.82
#Sta/Elev= 30
  4542.0 2038.45  4681.4 2040.07  4797.0 2040.13  4892.6 2038.82  4928.6 2036.70
  4951.7 2036.64  4969.9 2034.08  4975.0 2034.97  4999.0 2032.76  5030.1 2032.74
  5030.6 2032.24  5037.3 2032.74  5084.6 2039.03  5122.1 2038.83  5145.7 2039.92
  5206.8 2038.75  5237.4 2040.06  5283.2 2040.38  5288.3 2039.47  5335.2 2041.49
  5340.3 2040.03  5387.2 2043.13  5392.3 2042.21  5410.5 2042.31  5439.2 2045.22
  5444.3 2043.85  5451.2 2045.31  5491.2 2046.73  5496.3 2045.17  5505.3 2045.89
#Mann=3,-1,0
  4542.0   0.035       0  5030.1   0.035       0  5037.3   0.035       0
Bank Sta=5030.1,5037.3
Exp/Cntr=0.3,0.1

Chan Stop Cuts=-1