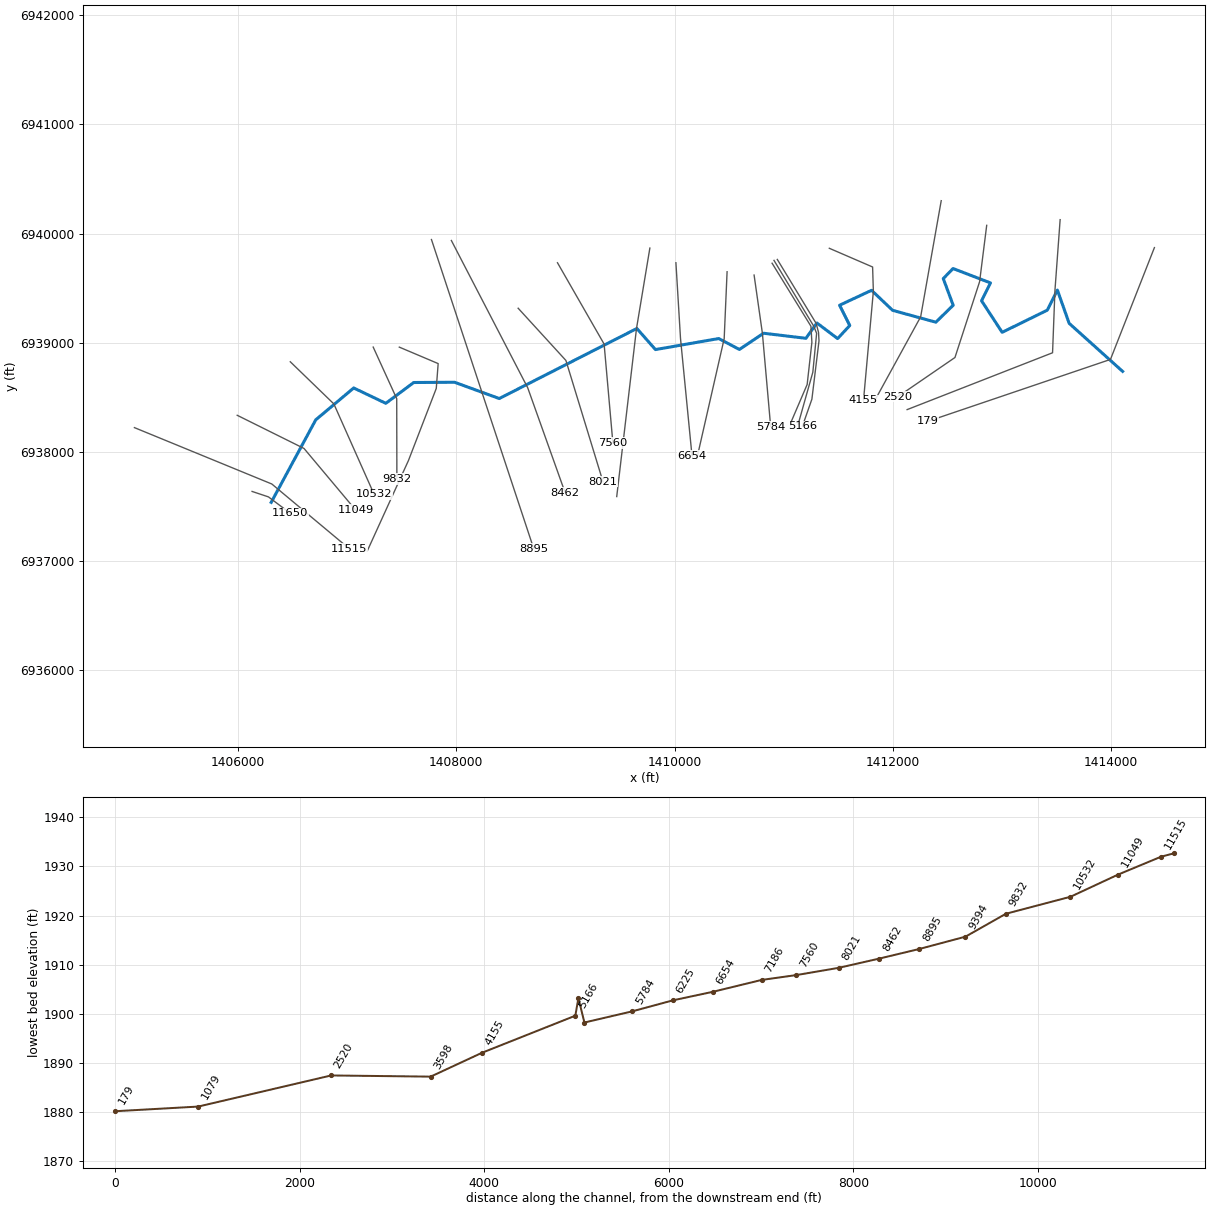
--- Plum Creek Trib10.prj (project) ---

Proj Title=Plum Creek Trib10 Base Level Engineering
Current Plan=p01
Default Exp/Contr=0.3,0.1
English Units
Geom File=g01
Flow File=f01
Plan File=p01
Y Axis Title=Elevation
X Axis Title(PF)=Main Channel Distance
X Axis Title(XS)=Station
BEGIN DESCRIPTION:
Plum Creek Trib10
END DESCRIPTION:
DSS Export Rating Curves= 0
DSS Export Rating Curve Sorted= 0
DSS Export Volume Flow Curves= 0
DXF OffsetX= 0
DXF OffsetY= 0
DXF ScaleX= 1
DXF ScaleY= 10

--- Plum Creek Trib10.p01 (plan) ---

Plan Title=Multiple Run
Short Identifier=Multiple
Geom File=g01
Flow File=f01
Subcritical Flow
K Sum by GR= 0
Std Step Tol= 0.01
Critical Tol= 0.01
Num of Std Step Trials= 20
Max Error Tol= 0.3
Flow Tol Ratio= 0.001
Split Flow NTrial= 30
Split Flow Tol= 0.02
Split Flow Ratio= 0.02
Log Output Level= 0
Friction Slope Method= 1
Unsteady Friction Slope Method= 2
Unsteady Bridges Friction Slope Method= 1
Parabolic Critical Depth
Global Vel Dist=  1 , 1 , 1
Global Log Level= 0
CheckData=True
Encroach Param= -1, 0, 0, 0
BEGIN DESCRIPTION:
Multiple Run
END DESCRIPTION:

--- Plum Creek Trib10.f01 (steady flow) ---

Flow Title=Multiple
Number of Profiles=7
Profile Names=10-year,25-year,50-year,1pct_min,100-year,1pct_plu,500-year
River Rch & RM= Plum Creek Trib1,Reach-1,11650
     208     289     357     219     436     871     662
River Rch & RM= Plum Creek Trib1,Reach-1,11515
     283     401     499     310     618    1232     957
River Rch & RM= Plum Creek Trib1,Reach-1,8462
     405     585     738     463     924    1843    1466
River Rch & RM= Plum Creek Trib1,Reach-1,6225
     496     721     915     576    1150    2295    1841
Boundary for River Rch & Prof#=Plum Creek Trib1,Reach-1,1
Up Type=0
Dn Type=3
Dn Slope=0.005
Boundary for River Rch & Prof#=Plum Creek Trib1,Reach-1,2
Up Type=0
Dn Type=3
Dn Slope=0.005
Boundary for River Rch & Prof#=Plum Creek Trib1,Reach-1,3
Up Type=0
Dn Type=3
Dn Slope=0.005
Boundary for River Rch & Prof#=Plum Creek Trib1,Reach-1,4
Up Type=0
Dn Type=3
Dn Slope=0.005
Boundary for River Rch & Prof#=Plum Creek Trib1,Reach-1,5
Up Type=0
Dn Type=3
Dn Slope=0.005
Boundary for River Rch & Prof#=Plum Creek Trib1,Reach-1,6
Up Type=0
Dn Type=3
Dn Slope=0.005
Boundary for River Rch & Prof#=Plum Creek Trib1,Reach-1,7
Up Type=0
Dn Type=3
Dn Slope=0.005

--- Plum Creek Trib10.g01 (geometry) ---

Geom Title=Existing Conditions
Program Version=4.10

River Reach=Plum Creek Trib1,Reach-1
Reach XY= 30
        1406305.        6937538.      1406713.14      6938294.06
      1407060.97      6938585.86        1407355.       6938445.5
      1407610.89      6938636.04      1407984.83      6938638.29
       1408394.5      6938489.19        1409655.      6939130.91
      1409825.34      6938937.69      1410405.01      6939038.85
       1410594.3       6938938.7      1410815.62       6939087.4
      1411203.57      6939041.07      1411304.79      6939181.02
      1411494.37      6939038.54      1411605.47      6939158.16
      1411512.45      6939344.07       1411805.1      6939480.68
      1411998.26      6939297.13      1412394.38      6939188.59
      1412552.95      6939343.86      1412462.08      6939588.03
      1412551.55      6939680.21      1412894.83      6939548.39
      1412812.88      6939384.78      1413001.59      6939095.77
      1413415.11      6939298.65      1413507.49      6939483.04
      1413615.48       6939178.2        1414105.        6938738.

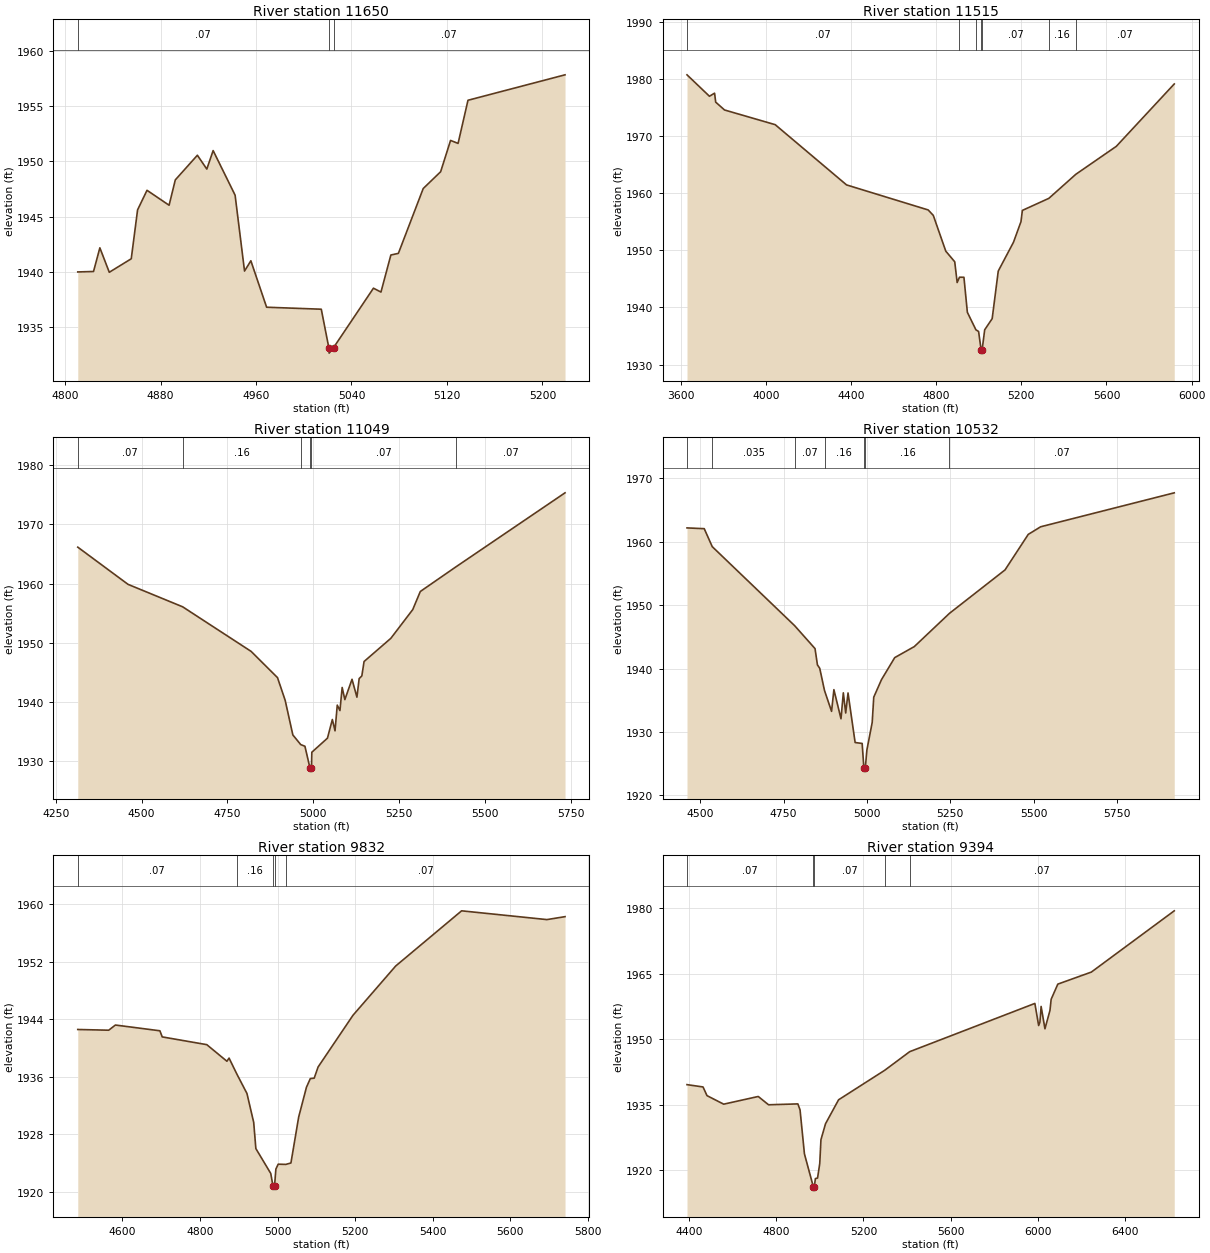
Type RM Length L Ch R = 1 ,11650   ,135,135,135
BEGIN DESCRIPTION:
Plum Creek Trib10 18.0
END DESCRIPTION:
XS GIS Cut Line= 3
      1406129.96      6937638.01        1406280.        6937588.
      1406480.04      6937437.97
#Sta/Elev= 30
  4810.7 1939.99  4823.9 1940.03  4829.2 1942.17  4837.1 1939.96  4855.5 1941.18
  4860.8  1945.6  4868.7 1947.37  4887.2 1946.02  4892.4 1948.31  4910.9 1950.54
  4918.8 1949.29  4924.1 1950.96  4942.5 1946.93  4950.4 1940.07  4955.7    1941
  4968.9  1936.8  5014.7 1936.62    5021 1933.15  5021.3 1932.65    5025 1933.15
  5058.4 1938.52  5064.7 1938.17    5073 1941.52  5079.3 1941.67  5100.1 1947.53
  5114.7 1949.05    5123 1951.88  5129.3 1951.61  5137.6 1955.51  5218.9 1957.81
#Mann= 3 ,-1 , 0
  4810.7     .07       0    5021     .07       0    5025     .07       0
Bank Sta=5021,5025
XS Rating Curve= 0 ,0
Exp/Cntr=0.3,0.1

Type RM Length L Ch R = 1 ,11515   ,466,466,466
BEGIN DESCRIPTION:
Mapping XS 4539966b
END DESCRIPTION:
XS GIS Cut Line= 3
       1405051.9      6938222.75       1406310.6      6937706.26
      1407022.38      6937111.66
#Sta/Elev= 30
  3630.3 1980.68  3735.7 1976.93  3759.7 1977.47  3765.1  1975.9  3806.6 1974.53
  4044.4 1971.96  4379.5 1961.42  4762.8 1957.04  4786.8 1956.09  4845.5 1949.83
  4887.5 1947.97  4898.9 1944.34  4909.8 1945.27  4930.7 1945.26  4946.8 1939.13
    4987 1936.07  4999.5 1935.78  5011.7 1932.49    5012 1931.99  5015.9 1932.49
  5028.1 1936.07  5063.3 1938.02  5091.9 1946.35  5163.5  1951.4  5198.6    1955
  5205.1 1956.96  5329.5 1959.07  5455.9 1963.27  5646.3 1968.17  5918.3 1979.08
#Mann= 7 ,-1 , 0
  3630.3     .07       0  4909.8     .16       0    4987     .07       0
  5011.7     .07       0  5015.9     .07       0  5329.5     .16       0
  5455.9     .07       0
Bank Sta=5011.7,5015.9
XS Rating Curve= 0 ,0
Exp/Cntr=0.3,0.1

Type RM Length L Ch R = 1 ,11049   ,517,517,517
BEGIN DESCRIPTION:
Mapping XS 0161abf0
END DESCRIPTION:
XS GIS Cut Line= 3
      1405993.77      6938335.59      1406605.74      6938031.78
      1407078.85      6937467.51
#Sta/Elev= 30
  4314.3 1966.15  4460.8 1959.87  4619.9 1956.08  4819.3 1948.56  4896.2 1944.13
  4918.6 1940.29  4940.9 1934.46  4963.8 1932.83  4976.1 1932.55  4990.9 1928.85
  4991.1 1928.35  4995.1 1928.85  4996.2 1931.54  5041.7 1933.91    5056 1937.06
  5063.8 1935.15  5070.3 1939.49  5078.1 1938.57  5084.6 1942.47  5092.4 1940.42
  5113.3 1943.85  5127.6 1940.83  5134.1 1943.97  5141.9 1944.42  5148.4 1946.85
  5226.5 1950.77  5290.2 1955.61  5312.3 1958.67  5415.4  1962.8  5733.9 1975.32
#Mann= 6 ,-1 , 0
  4314.3     .07       0  4619.9     .16       0  4963.8     .07       0
  4990.9     .07       0  4995.1     .07       0  5415.4     .07       0
Bank Sta=4990.9,4995.1
XS Rating Curve= 0 ,0
Exp/Cntr=0.3,0.1

Type RM Length L Ch R = 1 ,10532   ,700,700,700
BEGIN DESCRIPTION:
Mapping XS 89a0965d
END DESCRIPTION:
XS GIS Cut Line= 3
      1406479.85      6938826.07      1406879.17      6938439.76
      1407247.62      6937611.84
#Sta/Elev= 30
  4460.3 1962.16    4512 1962.04    4536 1959.21  4783.3 1946.75  4844.4 1943.14
  4851.6 1940.57  4858.5 1940.04  4872.9 1936.52    4894 1933.25    4901 1936.67
  4922.3 1932.08  4929.3 1936.17  4936.4 1932.99  4943.4 1936.15  4964.7 1928.34
  4985.8 1928.19  4990.9 1924.33  4991.2 1923.83  4995.2 1924.33    5000 1927.17
  5015.9  1931.5  5020.6 1935.49  5043.9 1938.26  5083.5 1941.72  5142.3 1943.46
  5247.8  1948.7  5414.4 1955.54  5484.1 1961.14  5521.3 1962.34  5922.1 1967.69
#Mann= 7 ,-1 , 0
  4460.3     .07       0    4536    .035       0  4783.3     .07       0
  4872.9     .16       0  4990.9     .07       0  4995.2     .16       0
  5247.8     .07       0
Bank Sta=4990.9,4995.2
XS Rating Curve= 0 ,0
Exp/Cntr=0.3,0.1

Type RM Length L Ch R = 1 ,9832    ,438,438,438
BEGIN DESCRIPTION:
Plum Creek Trib10 15.0
END DESCRIPTION:
XS GIS Cut Line= 3
      1407239.41      6938960.61        1407455.        6938488.
      1407456.43      6937751.36
#Sta/Elev= 30
  4484.8 1942.58  4564.6 1942.48  4581.8  1943.2  4696.5  1942.4  4702.5 1941.55
  4817.4 1940.47  4869.3 1938.16  4874.8  1938.6  4894.5 1936.42  4920.9 1933.68
  4938.3 1929.66  4943.9 1926.01  4982.3 1922.55  4987.8 1920.87  4988.1 1920.37
  4992.1 1920.87  4995.5 1923.16  5001.5 1923.84  5021.1 1923.81  5034.3 1924.01
  5054.3 1930.41  5074.3 1934.54  5084.3 1935.75  5094.3 1935.81  5104.3 1937.36
  5194.3 1944.56  5304.3 1951.41  5474.3 1959.09  5694.3 1957.87  5740.9 1958.28
#Mann= 5 ,-1 , 0
  4484.8     .07       0  4894.5     .16       0  4987.8     .07       0
  4992.1     .16       0  5021.1     .07       0
Bank Sta=4987.8,4992.1
XS Rating Curve= 0 ,0
Exp/Cntr=0.3,0.1

Type RM Length L Ch R = 1 ,9394    ,499,499,499
BEGIN DESCRIPTION:
Mapping XS 56771202
END DESCRIPTION:
XS GIS Cut Line= 5
      1407478.68      6938960.12      1407834.65      6938809.33
      1407817.35      6938581.92      1407562.75      6937921.94
      1407184.91      6937092.16
#Sta/Elev= 30
    4391 1939.63  4464.5  1939.1  4482.7 1937.11  4559.2 1935.16  4717.6 1936.92
  4764.9 1935.02  4899.3 1935.22  4909.3 1933.84  4929.4 1923.77  4970.4 1916.21
  4970.7 1915.71  4974.7 1916.21  4979.5 1918.12  4989.5 1918.25  4999.6 1921.58
  5005.1 1927.03    5026 1930.67  5085.9 1936.16  5297.8 1942.93  5412.1 1947.18
  5985.8 1958.22  6003.1 1953.16  6008.9 1953.94  6014.4 1957.53    6032 1952.42
    6055 1956.61  6060.5 1959.18    6091 1962.64  6244.8  1965.4  6624.8 1979.42
#Mann= 5 ,-1 , 0
    4391     .07       0  4970.4     .07       0  4974.7     .07       0
  5297.8    .035       0  5412.1     .07       0
Bank Sta=4970.4,4974.7
XS Rating Curve= 0 ,0
Exp/Cntr=0.3,0.1

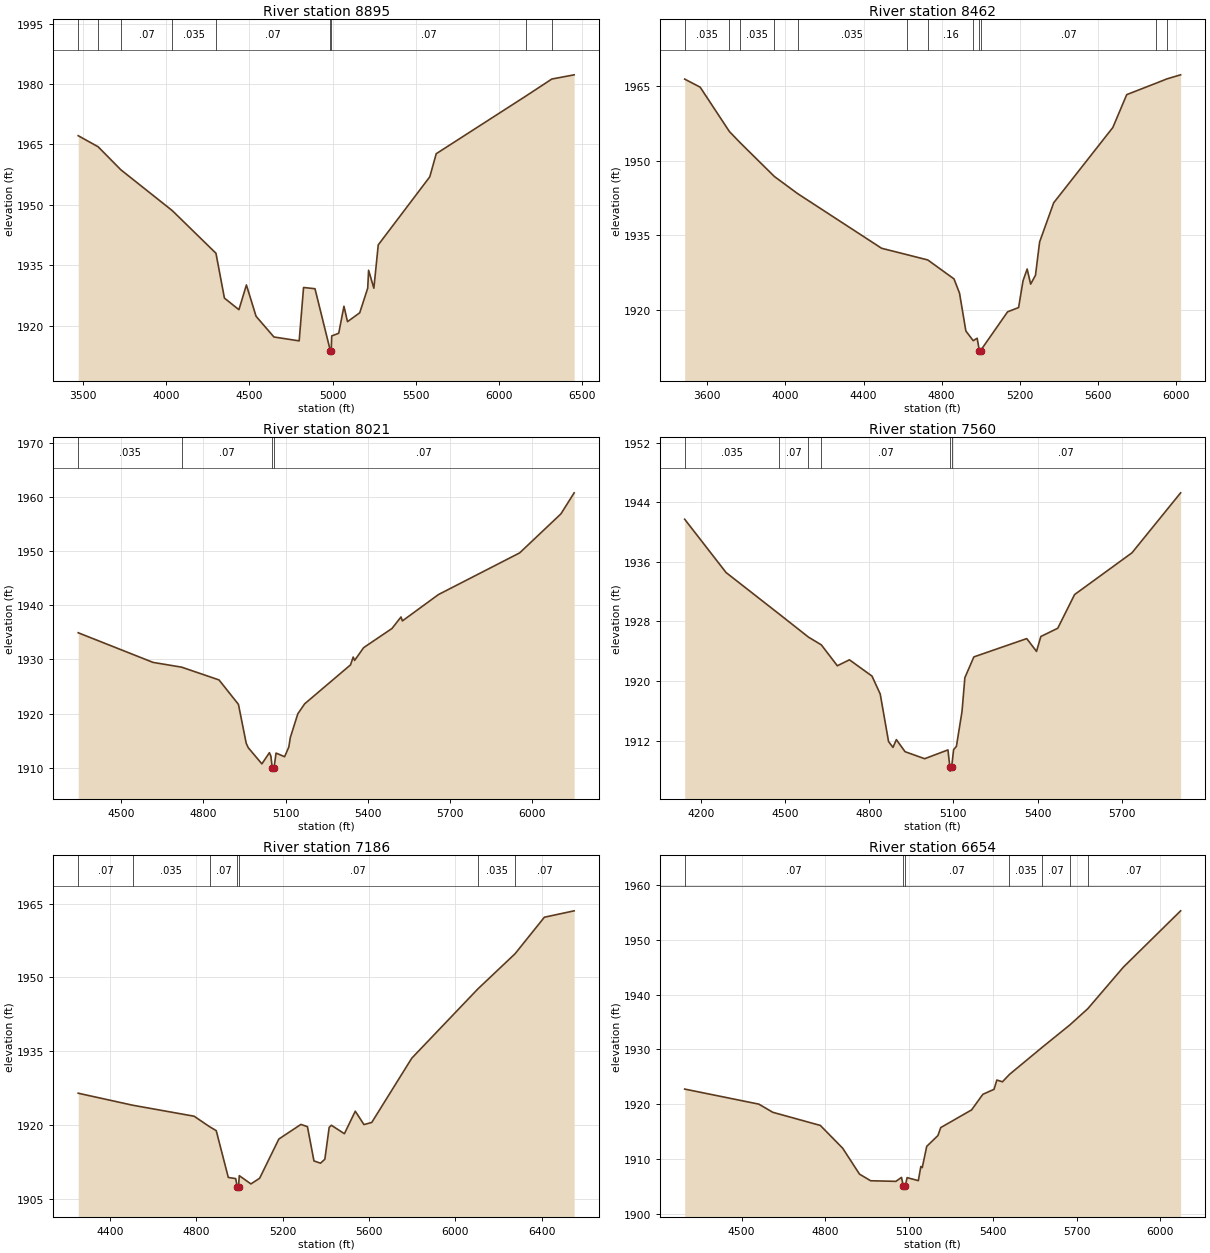
Type RM Length L Ch R = 1 ,8895    ,433,433,433
BEGIN DESCRIPTION:
Plum Creek Trib10 13.0
END DESCRIPTION:
XS GIS Cut Line= 3
      1407773.26      6939945.88        1408255.        6938488.
      1408710.15      6937113.51
#Sta/Elev= 30
  3470.3 1967.18  3590.2 1964.43  3726.5 1958.73  4036.6 1948.57  4298.9    1938
  4349.9 1926.87    4437 1923.99  4482.1 1930.13  4540.3 1922.35  4647.6 1917.22
  4799.4 1916.25  4825.9  1929.5  4894.6  1929.2  4987.6 1913.71  4987.9 1913.21
  4992.1 1913.71  4995.2 1917.48  5037.3 1918.14  5068.9 1924.85  5090.2 1921.02
  5163.7 1923.22  5211.8 1929.34  5217.1 1933.78  5248.8 1929.33  5275.2 1940.08
  5585.1 1956.97    5624 1962.71  6161.4 1976.97  6319.5 1981.25  6453.6 1982.29
#Mann= 9 ,-1 , 0
  3470.3     .07       0  3590.2    .035       0  3726.5     .07       0
  4036.6    .035       0  4298.9     .07       0  4987.6     .07       0
  4992.1     .07       0  6161.4    .035       0  6319.5     .07       0
Bank Sta=4987.6,4992.1
XS Rating Curve= 0 ,0
Exp/Cntr=0.3,0.1

Type RM Length L Ch R = 1 ,8462    ,441,441,441
BEGIN DESCRIPTION:
Plum Creek Trib10 12.0
END DESCRIPTION:
XS GIS Cut Line= 3
      1407955.57      6939937.15        1408655.        6938588.
      1408997.22      6937628.16
#Sta/Elev= 30
  3484.5 1966.46  3563.7 1964.84  3713.4  1955.9  3767.7 1953.68  3943.5 1946.85
  4062.8 1943.39  4492.6 1932.38  4620.8 1931.11  4728.9 1930.03  4863.2 1926.21
  4891.5 1923.33  4923.9 1915.72  4961.5 1913.77  4981.7 1914.26  4992.9 1911.76
  4993.4 1911.26  4998.9 1911.76  5137.5 1919.58  5193.8 1920.44  5216.5 1925.84
  5237.7  1928.2  5255.5 1925.16  5280.2 1926.94  5301.4 1933.65  5373.4 1941.54
  5676.2 1956.71  5747.3 1963.33  5897.9 1965.64  5953.6 1966.51  6023.2 1967.32
#Mann= 12 ,-1 , 0
  3484.5    .035       0  3713.4     .07       0  3767.7    .035       0
  3943.5     .07       0  4062.8    .035       0  4620.8     .07       0
  4728.9     .16       0  4961.5     .07       0  4992.9     .07       0
  4998.9     .07       0  5897.9     .16       0  5953.6     .07       0
Bank Sta=4992.9,4998.9
XS Rating Curve= 0 ,0
Exp/Cntr=0.3,0.1

Type RM Length L Ch R = 1 ,8021    ,461,461,461
BEGIN DESCRIPTION:
Plum Creek Trib10 11.0
END DESCRIPTION:
XS GIS Cut Line= 3
      1408567.52      6939316.52        1409005.        6938838.
      1409344.44        6937728.
#Sta/Elev= 30
  4343.3  1934.9  4616.4 1929.43  4720.7 1928.55  4856.9  1926.2  4927.8 1921.69
  4956.2 1914.51  4963.6 1913.69  5013.3 1910.71  5040.8 1912.77  5046.1 1912.15
  5051.4 1909.87  5051.9 1909.37  5057.4 1909.87  5064.9  1912.7  5096.2 1912.03
  5111.6 1913.83  5117.1 1915.58  5144.4 1919.95  5169.4 1921.79  5336.7 1928.98
  5346.3 1930.42  5351.6  1929.8  5384.4 1932.15  5487.9 1935.69  5520.7 1937.81
  5525.9 1937.09  5657.1 1941.94  5953.7 1949.64  6104.2 1956.84  6152.4 1960.72
#Mann= 4 ,-1 , 0
  4343.3    .035       0  4720.7     .07       0  5051.4     .07       0
  5057.4     .07       0
Bank Sta=5051.4,5057.4
XS Rating Curve= 0 ,0
Exp/Cntr=0.3,0.1

Type RM Length L Ch R = 1 ,7560    ,374,374,374
BEGIN DESCRIPTION:
Plum Creek Trib10 10.0
END DESCRIPTION:
XS GIS Cut Line= 3
      1408927.79      6939733.16        1409355.        6938988.
      1409435.44      6938081.29
#Sta/Elev= 30
  4141.3 1941.74  4288.9 1934.58  4477.8 1929.02  4582.9  1925.9  4628.8 1924.86
  4685.9 1922.05  4729.1 1922.85  4809.6 1920.66  4838.9 1918.25  4868.6 1911.87
  4884.4 1911.08  4896.5 1912.12  4927.6  1910.5  4997.4 1909.56  5080.5 1910.74
  5087.5 1908.39    5088 1907.89  5093.6 1908.39  5100.6 1910.77  5110.7 1911.22
  5130.7 1915.92  5140.8 1920.44  5172.9 1923.24  5361.6  1925.7  5396.5 1923.98
  5411.8 1925.98  5472.1 1927.09  5532.3 1931.62    5737 1937.23  5910.5 1945.29
#Mann= 6 ,-1 , 0
  4141.3    .035       0  4477.8     .07       0  4582.9    .035       0
  4628.8     .07       0  5087.5     .07       0  5093.6     .07       0
Bank Sta=5087.5,5093.6
XS Rating Curve= 0 ,0
Exp/Cntr=0.3,0.1

Type RM Length L Ch R = 1 ,7186    ,532,532,532
BEGIN DESCRIPTION:
Plum Creek Trib10 9.0
END DESCRIPTION:
XS GIS Cut Line= 3
      1409774.13      6939867.68      1409651.67      6939130.38
      1409470.55        6937591.
#Sta/Elev= 30
  4252.6 1926.43  4504.8 1923.99  4789.5 1921.75  4861.3 1919.61    4892 1918.81
  4947.9 1909.29  4982.1 1909.05  4989.2 1907.41  4989.7 1906.91  4995.3 1907.41
  4998.7 1909.65  5052.7 1907.97    5093 1909.12    5182  1917.1  5284.3 1920.08
  5314.5 1919.62  5344.7 1912.65    5375 1912.19  5395.1 1912.99  5415.2 1919.48
  5425.3 1919.91  5485.7 1918.19  5536.1 1922.77  5576.3 1920.05  5612.4 1920.48
  5797.8 1933.56  6104.1 1947.66  6276.4 1954.82  6412.1 1962.25    6550 1963.55
#Mann= 7 ,-1 , 0
  4252.6     .07       0  4504.8    .035       0  4861.3     .07       0
  4989.2     .07       0  4995.3     .07       0  6104.1    .035       0
  6276.4     .07       0
Bank Sta=4989.2,4995.3
XS Rating Curve= 0 ,0
Exp/Cntr=0.3,0.1

Type RM Length L Ch R = 1 ,6654    ,429,429,429
BEGIN DESCRIPTION:
Plum Creek Trib10 8.0
END DESCRIPTION:
XS GIS Cut Line= 3
      1410012.85      6939733.21        1410055.        6939038.
      1410160.39      6937962.64
#Sta/Elev= 30
  4295.8 1922.75  4561.5    1920  4611.6 1918.51  4781.9 1916.11    4862 1911.95
  4922.2 1907.22  4962.2 1906.01  5052.6  1905.9  5072.7 1906.62  5079.6 1904.98
  5080.1 1904.48  5085.8 1904.98  5092.8 1906.58    5133 1906.03    5142 1908.61
    5147  1908.4  5163.1 1912.29  5203.3 1914.27  5213.3 1915.72  5323.9 1918.95
  5364.1 1921.79  5404.3 1922.71  5414.3  1924.4  5434.4 1924.08  5459.4 1925.42
  5577.8 1930.42  5675.8 1934.46  5740.2 1937.43  5867.6 1945.01  6072.8  1955.3
#Mann= 7 ,-1 , 0
  4295.8     .07       0  5079.6     .07       0  5085.8     .07       0
  5459.4    .035       0  5577.8     .07       0  5675.8    .035       0
  5740.2     .07       0
Bank Sta=5079.6,5085.8
XS Rating Curve= 0 ,0
Exp/Cntr=0.3,0.1

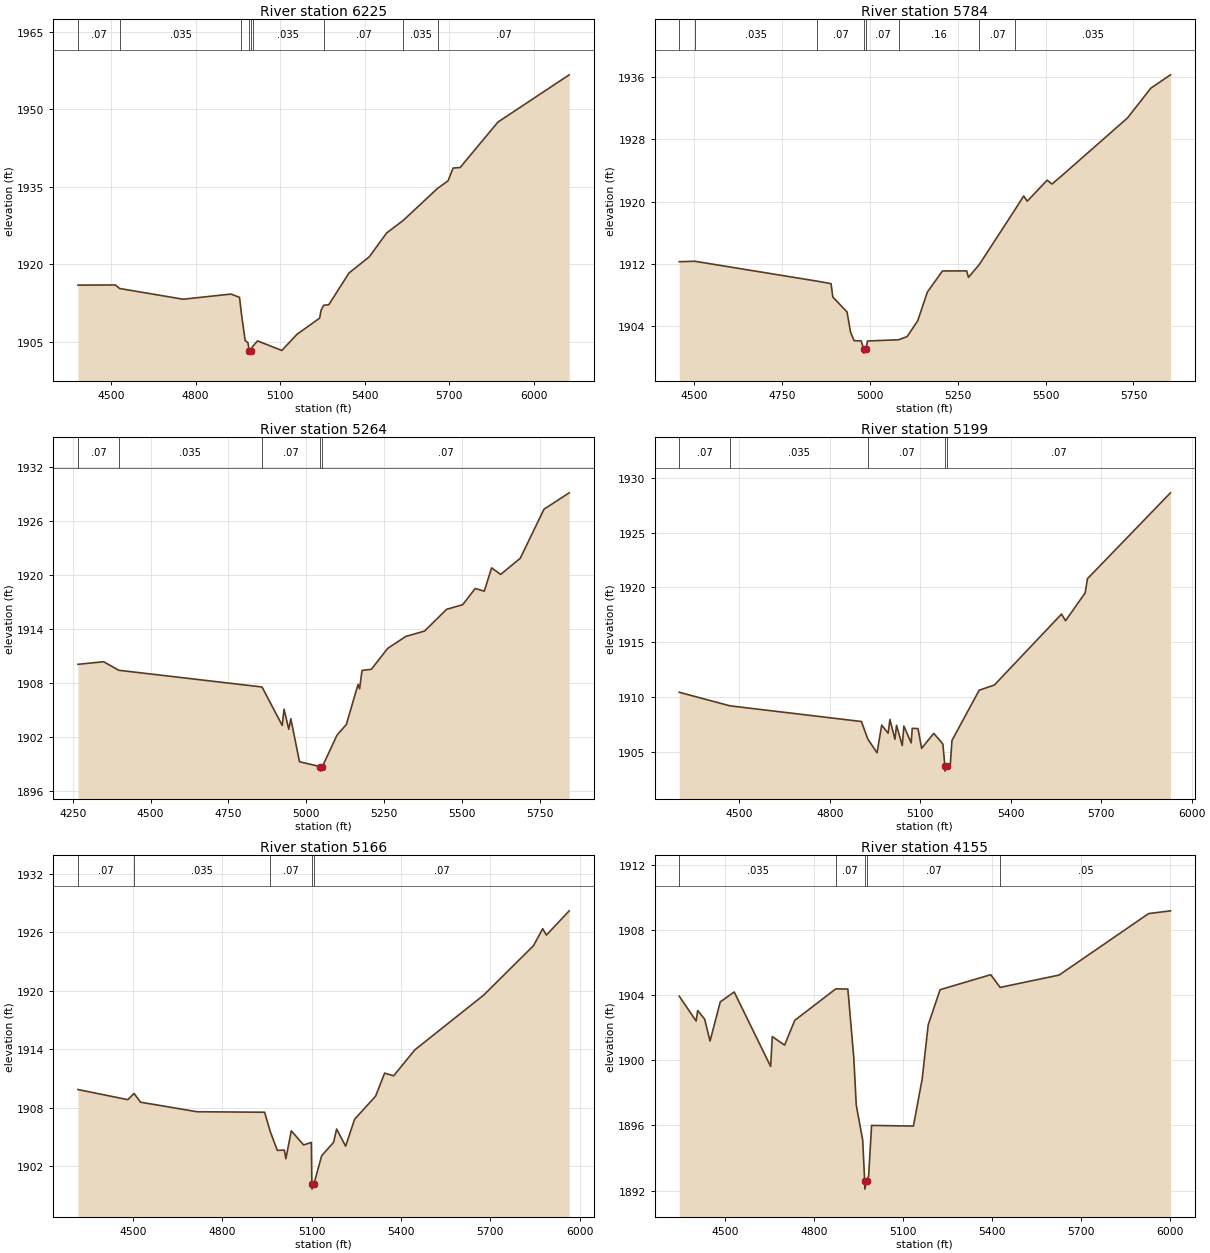
Type RM Length L Ch R = 1 ,6225    ,441,441,441
BEGIN DESCRIPTION:
Plum Creek Trib10 7.0
END DESCRIPTION:
XS GIS Cut Line= 3
      1410481.61      6939650.74        1410455.        6939038.
      1410203.82      6937936.28
#Sta/Elev= 30
  4382.8 1915.93  4515.7 1915.96  4530.5 1915.28  4755.9  1913.2    4926  1914.2
  4956.1 1913.56  4962.4 1910.59  4976.1 1905.19  4986.1 1904.77  4990.4 1903.26
  4990.9 1902.76  4996.8 1903.26  5002.6 1904.06  5020.2 1905.12  5106.2 1903.28
  5160.2 1906.41  5240.3 1909.53  5245.5 1911.06  5254.7 1912.03    5273 1912.14
  5344.8 1918.29  5416.6 1921.41  5478.2 1926.03  5537.5 1928.48  5659.5  1934.7
  5696.1 1936.13  5714.1  1938.6  5739.1 1938.71  5873.2 1947.51  6126.1 1956.66
#Mann= 9 ,-1 , 0
  4382.8     .07       0  4530.5    .035       0  4962.4     .07       0
  4990.4     .07       0  4996.8     .07       0  5002.6    .035       0
  5254.7     .07       0  5537.5    .035       0  5659.5     .07       0
Bank Sta=4990.4,4996.8
XS Rating Curve= 0 ,0
Exp/Cntr=0.3,0.1

Type RM Length L Ch R = 1 ,5784    ,520,520,520
BEGIN DESCRIPTION:
Plum Creek Trib10 6.0
END DESCRIPTION:
XS GIS Cut Line= 3
        1410729.       6939620.3        1410805.        6939088.
      1410880.84      6938232.25
#Sta/Elev= 30
  4458.5 1912.27  4502.4 1912.33  4850.6 1909.77  4890.1 1909.45  4895.2 1907.73
  4935.6 1905.81  4945.7 1903.19  4955.8 1902.12    4976 1902.09  4982.8 1901.02
  4983.3 1900.52  4989.3 1901.02  4993.7 1902.08  5082.5 1902.24  5106.6 1902.65
  5136.7 1904.69    5164 1908.37    5207 1911.08  5275.8 1911.09  5280.9 1910.26
    5312 1911.93  5414.6 1919.06  5437.9 1920.72    5448 1920.05  5504.6 1922.75
  5518.2 1922.25  5548.4 1923.41  5733.3 1930.76  5799.3 1934.57  5855.3 1936.29
#Mann= 8 ,-1 , 0
  4458.5     .07       0  4502.4    .035       0  4850.6     .07       0
  4982.8     .07       0  4989.3     .07       0  5082.5     .16       0
    5312     .07       0  5414.6    .035       0
Bank Sta=4982.8,4989.3
XS Rating Curve= 0 ,0
Exp/Cntr=0.3,0.1

Type RM Length L Ch R = 1 ,5264    ,65,65,65
BEGIN DESCRIPTION:
Mapping XS 4f842d36
END DESCRIPTION:
XS GIS Cut Line= 5
      1410893.91      6939728.86      1411249.83      6939151.57
      1411258.51        6939004.      1411215.11      6938617.71
      1411071.89      6938283.54
#Sta/Elev= 30
  4266.6 1910.11  4349.2  1910.4  4397.5 1909.45    4858 1907.59  4922.8 1903.32
  4928.7 1905.12  4943.9 1902.89  4950.5 1904.06  4978.4 1899.28  5045.3 1898.74
  5045.8 1898.24  5051.8 1898.74  5098.7 1902.23  5128.8 1903.42  5166.5 1907.88
  5171.5 1907.39  5179.2 1909.43  5209.3 1909.56  5261.6 1911.88    5320 1913.21
  5380.4 1913.81  5450.9 1916.22  5502.8 1916.74    5543 1918.54    5572 1918.24
  5595.6 1920.83  5624.6  1920.1  5687.7  1921.9  5763.9 1927.35  5844.9 1929.17
#Mann= 5 ,-1 , 0
  4266.6     .07       0  4397.5    .035       0    4858     .07       0
  5045.3     .07       0  5051.8     .07       0
Bank Sta=5045.3,5051.8
XS Rating Curve= 0 ,0
Exp/Cntr=0.3,0.1

Type RM Length L Ch R = 1 ,5199    ,33,33,33
BEGIN DESCRIPTION:
Mapping XS 5599ceb2
END DESCRIPTION:
XS GIS Cut Line= 5
       1410911.3      6939754.85      1411275.87      6939151.57
      1411301.92      6939086.46      1411267.19      6938730.56
      1411132.65      6938253.15
#Sta/Elev= 30
  4301.2 1910.43  4469.8 1909.19  4905.1 1907.76  4926.7 1906.14  4956.9 1904.91
  4972.4 1907.43  4993.7 1906.69  4999.6 1907.95  5016.3 1906.14  5021.6 1907.41
  5040.5 1905.57  5045.9 1907.35  5070.1 1905.81  5073.6 1907.14  5092.8 1907.11
  5104.8 1905.31    5145 1906.68  5175.1 1905.71  5181.9 1903.73  5182.4 1903.23
  5188.4 1903.73  5199.6 1903.75  5205.3 1906.03  5295.7 1910.62  5345.9 1911.09
  5568.6 1917.57  5581.9 1916.96    5647 1919.51  5654.6  1920.8  5929.8 1928.64
#Mann= 5 ,-1 , 0
  4301.2     .07       0  4469.8    .035       0  4926.7     .07       0
  5181.9     .07       0  5188.4     .07       0
Bank Sta=5181.9,5188.4
XS Rating Curve= 0 ,0
Exp/Cntr=0.3,0.1

Type RM Length L Ch R = 1 ,5166    ,1011,1011,1011
BEGIN DESCRIPTION:
Mapping XS 476b27a8
END DESCRIPTION:
XS GIS Cut Line= 6
      1410941.65      6939763.58      1411297.58      6939177.61
      1411319.28      6939095.15      1411323.62      6939017.02
      1411258.51      6938483.17      1411171.71      6938235.78
#Sta/Elev= 30
  4315.5 1909.86  4482.8 1908.82  4503.8 1909.46  4525.5 1908.56  4715.4 1907.58
  4942.1 1907.53  4961.6 1905.49  4984.8 1903.61  5008.2 1903.64  5013.4 1902.75
  5031.7 1905.62  5073.1 1904.17    5099 1904.43  5100.7 1900.13  5101.2 1899.63
  5107.2 1900.13  5133.6 1903.06  5173.7 1904.44  5183.8 1905.81    5214 1904.04
  5244.2 1906.81  5314.7 1909.18    5345 1911.55  5375.2 1911.27  5446.5 1913.94
  5677.4 1919.56  5844.7 1924.64  5875.7 1926.38  5888.1 1925.73  5964.6 1928.22
#Mann= 5 ,-1 , 0
  4315.5     .07       0  4503.8    .035       0  4961.6     .07       0
  5100.7     .07       0  5107.2     .07       0
Bank Sta=5100.7,5107.2
XS Rating Curve= 0 ,0
Exp/Cntr=0.3,0.1

Type RM Length L Ch R = 1 ,4155    ,557,557,557
BEGIN DESCRIPTION:
Plum Creek Trib10 4.0
END DESCRIPTION:
XS GIS Cut Line= 4
      1411418.17      6939865.65      1411814.75      6939694.27
      1411821.71      6939471.71       1411731.6      6938474.47
#Sta/Elev= 30
  4345.3 1903.93  4402.1 1902.41  4407.5 1903.05    4431 1902.52  4449.1 1901.18
  4483.5 1903.58  4530.5 1904.19  4653.4 1899.62  4658.9 1901.45  4700.4 1900.93
  4734.8 1902.45  4872.9 1904.38  4913.7 1904.37  4933.7 1900.15    4942 1897.25
  4963.7  1895.1  4970.4 1892.59  4970.9 1892.09    4977 1892.59  4983.7 1892.89
  4993.7    1896  5134.7 1895.96  5164.4 1898.87  5184.5 1902.17  5224.6 1904.33
  5395.3 1905.25  5427.1 1904.47  5626.2 1905.23  5927.5    1909  6001.3 1909.17
#Mann= 5 ,-1 , 0
  4345.3    .035       0  4872.9     .07       0  4970.4      .1       0
    4977     .07       0  5427.1     .05       0
Bank Sta=4970.4,4977
XS Rating Curve= 0 ,0
Exp/Cntr=0.3,0.1

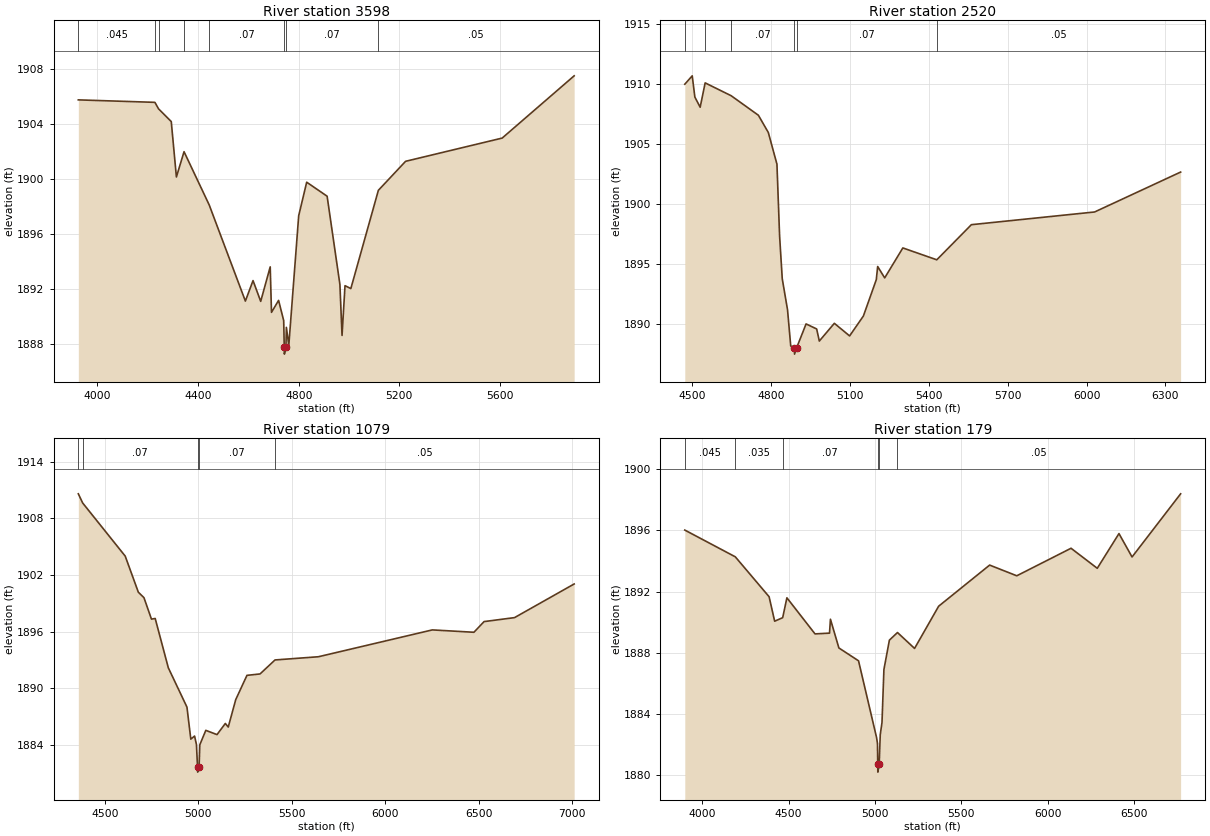
Type RM Length L Ch R = 1 ,3598    ,1078,1078,1078
BEGIN DESCRIPTION:
Plum Creek Trib10 3.0
END DESCRIPTION:
XS GIS Cut Line= 3
      1412443.42      6940301.78        1412255.        6939238.
      1411827.08       6938457.1
#Sta/Elev= 30
  3924.1 1905.73  4228.5 1905.55  4242.9 1905.08  4293.5 1904.15  4313.9 1900.12
  4344.3 1901.96  4444.2 1898.09  4588.1 1891.09  4618.5 1892.58    4649 1891.07
  4686.8 1893.58  4691.9 1890.27  4720.1 1891.14  4740.4 1889.67  4742.6 1887.73
  4743.1 1887.23  4749.2 1887.73    4751 1889.18  4760.7 1887.87    4800  1897.3
  4831.8 1899.74    4913 1898.72  4963.8  1892.3  4972.3 1888.59  4984.1 1892.21
  5007.3    1892  5116.7 1899.15  5224.9 1901.26  5608.8 1902.95  5894.9 1907.48
#Mann= 8 ,-1 , 0
  3924.1    .045       0  4228.5     .05       0  4242.9    .045       0
  4344.3    .035       0  4444.2     .07       0  4742.6     .07       0
  4749.2     .07       0  5116.7     .05       0
Bank Sta=4742.6,4749.2
XS Rating Curve= 0 ,0
Exp/Cntr=0.3,0.1

Type RM Length L Ch R = 1 ,2520    ,1441,1441,1441
BEGIN DESCRIPTION:
Mapping XS 4b1a16d9
END DESCRIPTION:
XS GIS Cut Line= 4
      1412860.07      6940076.04      1412794.97      6939559.55
      1412569.28      6938865.11      1412044.12      6938504.88
#Sta/Elev= 30
  4470.7 1909.99    4499 1910.69    4509 1908.92  4529.2 1908.07  4548.2  1910.1
  4647.2 1909.03  4750.9  1907.4  4788.7 1905.96  4821.5 1903.32  4831.6 1897.34
  4841.7 1893.76  4861.8 1891.17    4874 1888.15    4888 1887.97  4888.5 1887.47
    4896 1887.97  4932.4 1889.99  4972.7 1889.57  4982.8 1888.56    5040 1890.04
  5098.1 1888.99  5150.6 1890.65  5199.7 1893.68    5205 1894.78  5231.7 1893.83
  5300.8 1896.33    5430 1895.34  5561.7 1898.27  6030.8 1899.33  6358.3 1902.66
#Mann= 6 ,-1 , 0
  4470.7    .045       0  4548.2    .035       0  4647.2     .07       0
    4888     .07       0    4896     .07       0    5430     .05       0
Bank Sta=4888,4896
XS Rating Curve= 0 ,0
Exp/Cntr=0.3,0.1

Type RM Length L Ch R = 1 ,1079    ,900,900,900
BEGIN DESCRIPTION:
Mapping XS 3a6c2dca
END DESCRIPTION:
XS GIS Cut Line= 4
      1413532.82      6940128.12      1413485.08      6939477.09
      1413463.37      6938908.51      1412130.92      6938387.68
#Sta/Elev= 30
  4358.6 1910.59  4381.9 1909.62  4609.4    1904  4679.6 1900.18  4709.7  1899.6
  4749.8 1897.33  4769.8  1897.4    4840 1892.18  4939.7 1888.02  4960.3 1884.63
  4980.4 1884.96  4990.4 1884.07  4996.4 1881.64  4996.9 1881.14  5004.5 1881.64
  5008.4 1884.03  5040.5 1885.56  5100.5 1885.11    5145 1886.29  5160.6 1885.91
  5200.6 1888.81  5260.6 1891.38  5330.7 1891.53  5410.7 1893.01    5643 1893.35
  6252.2 1896.19  6474.8 1895.94  6529.1 1897.07  6692.1 1897.49    7011 1901.05
#Mann= 5 ,-1 , 0
  4358.6    .035       0  4381.9     .07       0  4996.4     .07       0
  5004.5     .07       0  5410.7     .05       0
Bank Sta=4996.4,5004.5
XS Rating Curve= 0 ,0
Exp/Cntr=0.3,0.1

Type RM Length L Ch R = 1 ,179     ,0,0,0
BEGIN DESCRIPTION:
Plum Creek Trib10 1.0
END DESCRIPTION:
XS GIS Cut Line= 3
      1414396.54      6939872.06      1413993.91      6938847.54
      1412318.77      6938279.59
#Sta/Elev= 30
  3899.2 1896.02  4191.5 1894.27  4387.1 1891.66  4419.3 1890.06  4465.7 1890.29
  4490.2 1891.59  4652.8 1889.23  4736.8 1889.28  4742.1 1890.19    4791 1888.31
  4904.7 1887.47  5009.1 1882.45  5014.4 1882.06  5015.9 1880.69  5016.4 1880.19
  5024.1 1880.69  5030.5 1882.65  5040.5 1883.44  5051.6  1886.9  5083.3 1888.82
  5130.1 1889.32    5229 1888.28  5368.4 1891.04  5663.5 1893.73  5820.5 1893.03
  6134.6 1894.83  6286.4 1893.52    6412 1895.79  6487.7 1894.26  6768.8 1898.39
#Mann= 6 ,-1 , 0
  3899.2    .045       0  4191.5    .035       0  4465.7     .07       0
  5015.9     .07       0  5024.1     .07       0  5130.1     .05       0
Bank Sta=5015.9,5024.1
XS Rating Curve= 0 ,0
Exp/Cntr=0.3,0.1

Chan Stop Cuts=-1
Use User Specified Reach Order=0
Composite Channel Slope=5