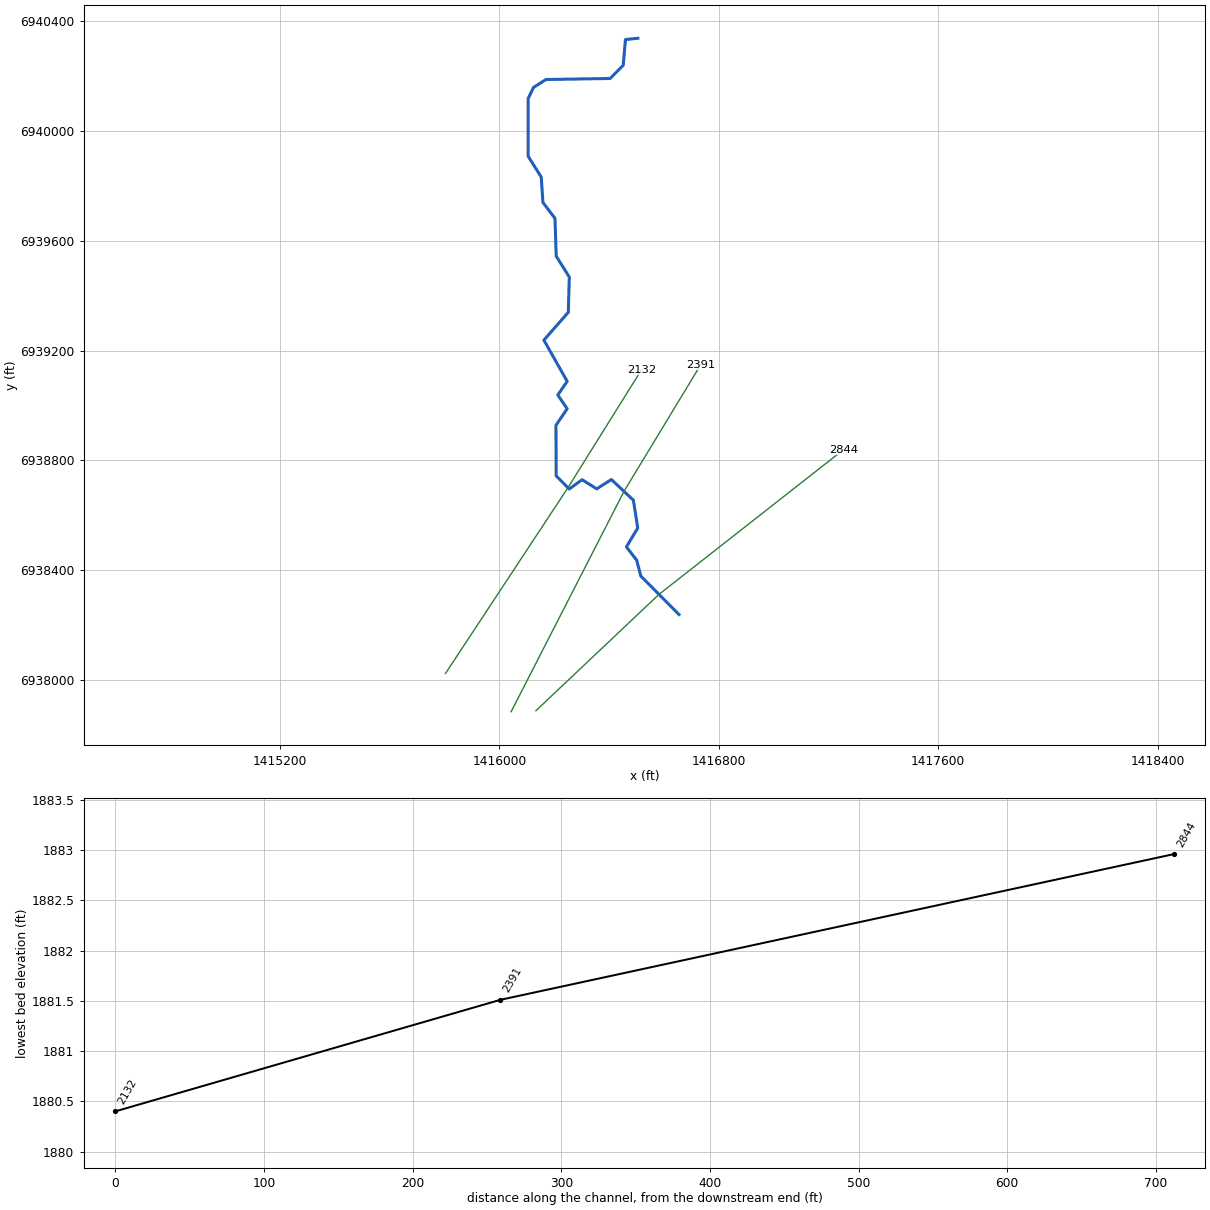
--- Plum Creek Trib11.prj (project) ---

Proj Title=Plum Creek Trib11 Base Level Engineering
Current Plan=p01
Default Exp/Contr=0.3,0.1
English Units
Geom File=g01
Flow File=f01
Plan File=p01
BEGIN DESCRIPTION:
Plum Creek Trib11
END DESCRIPTION:

--- Plum Creek Trib11.p01 (plan) ---

Plan Title=Multiple Run
Short Identifier=Multiple
Geom File=g01
Flow File=f01
Subcritical Flow
K Sum by GR= 0
Std Step Tol= 0.01
Critical Tol= 0.01
Num of Std Step Trials= 20
Max Error Tol= 0.3
Flow Tol Ratio= 0.001
Split Flow NTrial= 30
Split Flow Tol= 0.02
Split Flow Ratio= 0.02
Log Output Level= 0
Friction Slope Method= 1
Unsteady Friction Slope Method= 2
Unsteady Bridges Friction Slope Method= 1
Parabolic Critical Depth
Global Vel Dist=  1 , 1 , 1
Global Log Level= 0
CheckData=True
Encroach Param= -1, 0, 0, 0
BEGIN DESCRIPTION:
Multiple Run
END DESCRIPTION:

--- Plum Creek Trib11.f01 (steady flow) ---

Flow Title=Multiple
Number of Profiles=7
Profile Names=10-year,25-year,50-year,1pct_min,100-year,1pct_plu,500-year
River Rch & RM= Plum Creek Trib1,Reach-1,2844
     250     350     433     266     532    1061     813
River Rch & RM= Plum Creek Trib1,Reach-1,2391
     292     412     512     317     632    1261     975
Boundary for River Rch & Prof#=Plum Creek Trib1,Reach-1,1
Up Type=0
Dn Type=3
Dn Slope=0.005
Boundary for River Rch & Prof#=Plum Creek Trib1,Reach-1,2
Up Type=0
Dn Type=3
Dn Slope=0.005
Boundary for River Rch & Prof#=Plum Creek Trib1,Reach-1,3
Up Type=0
Dn Type=3
Dn Slope=0.005
Boundary for River Rch & Prof#=Plum Creek Trib1,Reach-1,4
Up Type=0
Dn Type=3
Dn Slope=0.005
Boundary for River Rch & Prof#=Plum Creek Trib1,Reach-1,5
Up Type=0
Dn Type=3
Dn Slope=0.005
Boundary for River Rch & Prof#=Plum Creek Trib1,Reach-1,6
Up Type=0
Dn Type=3
Dn Slope=0.005
Boundary for River Rch & Prof#=Plum Creek Trib1,Reach-1,7
Up Type=0
Dn Type=3
Dn Slope=0.005

--- Plum Creek Trib11.g01 (geometry) ---

Geom Title=Existing Conditions

River Reach=Plum Creek Trib1,Reach-1
Reach XY= 30
      1416655.00      6938238.00      1416515.74      6938378.32
      1416500.55      6938436.35      1416463.04      6938484.68
      1416504.49      6938553.22      1416488.60      6938654.82
      1416408.35      6938730.02      1416355.00      6938696.03
      1416301.65      6938729.44      1416254.75      6938695.44
      1416207.06      6938743.46      1416206.37      6938927.57
      1416247.22      6938988.10      1416213.03      6939038.00
      1416247.25      6939087.91      1416162.30      6939238.08
      1416251.45      6939339.47      1416254.95      6939467.96
      1416207.27      6939543.94      1416202.73      6939682.06
      1416158.86      6939739.60      1416152.64      6939832.02
      1416105.07      6939908.03      1416104.91      6940118.13
      1416124.40      6940158.66      1416170.02      6940187.68
      1416403.78      6940191.43      1416451.53      6940239.27
      1416459.75      6940333.32      1416505.00      6940338.00

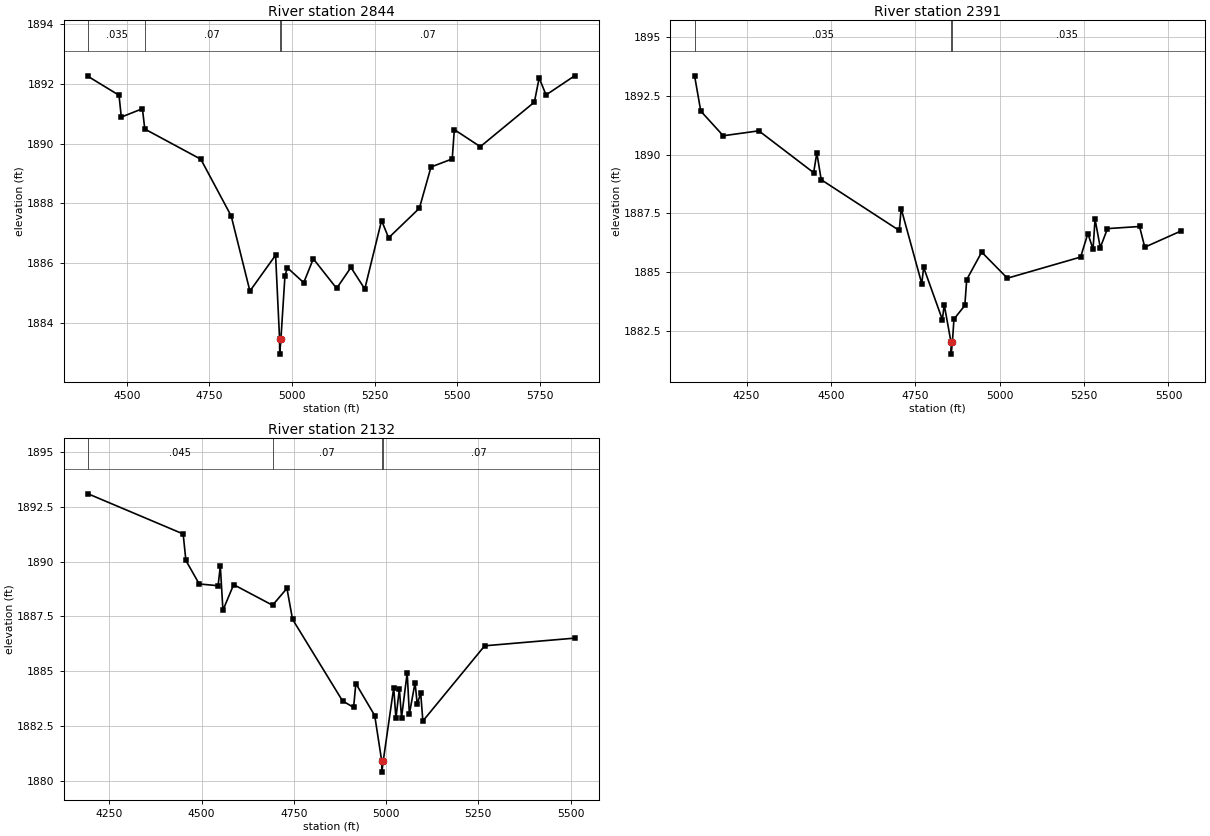
Type RM Length L Ch R = 1,2844,453,453,453
BEGIN DESCRIPTION:
Plum Creek Trib11 7.0
END DESCRIPTION:
XS GIS Cut Line= 3
      1416133.24      6937887.60      1416581.61      6938311.31
      1417254.75      6938838.97
#Sta/Elev= 30
  4383.1 1892.25  4476.6 1891.62  4483.5 1890.89  4547.4 1891.17  4554.6 1890.49
  4724.2 1889.48  4816.1 1887.58  4872.7 1885.07  4950.4 1886.27  4962.5 1883.46
  4962.8 1882.96  4966.5 1883.46  4978.7 1885.57  4986.0 1885.85  5035.6 1885.35
  5064.5 1886.15  5135.1 1885.16  5178.4 1885.86  5220.3 1885.14  5271.1 1887.43
  5292.4 1886.85  5385.5 1887.84  5420.7 1889.22  5484.9 1889.49  5491.3 1890.47
  5569.9 1889.90  5733.5 1891.39  5748.0 1892.20  5768.8 1891.63  5855.3 1892.27
#Mann=4,-1,0
  4383.1   0.035       0  4554.6    0.07       0  4962.5    0.07       0
  4966.5    0.07       0
Bank Sta=4962.5,4966.5
Exp/Cntr=0.3,0.1

Type RM Length L Ch R = 1,2391,259,259,259
BEGIN DESCRIPTION:
Plum Creek Trib11 6.0
END DESCRIPTION:
XS GIS Cut Line= 3
      1416042.98      6937884.16      1416455.25      6938688.57
      1416733.96      6939148.05
#Sta/Elev= 30
  4096.1 1893.35  4114.4 1891.85  4181.0 1890.80  4286.4 1891.01  4448.8 1889.23
  4458.3 1890.07  4471.2 1888.93  4702.5 1886.77  4708.1 1887.70  4769.1 1884.51
  4774.7 1885.20  4830.1 1882.98  4835.7 1883.61  4855.9 1882.01  4856.2 1881.51
  4859.9 1882.01  4864.5 1883.00  4896.7 1883.58  4902.3 1884.68  4946.7 1885.85
  5022.7 1884.74  5239.8 1885.64  5261.2 1886.64  5276.6 1885.98  5282.5 1887.25
  5298.0 1886.04  5319.3 1886.85  5414.3 1886.94  5429.8 1886.06  5537.4 1886.75
#Mann=3,-1,0
  4096.1   0.035       0  4855.9   0.035       0  4859.9   0.035       0
Bank Sta=4855.9,4859.9
Exp/Cntr=0.3,0.1

Type RM Length L Ch R = 1,2132,0,0,0
BEGIN DESCRIPTION:
Plum Creek Trib11 5.0
END DESCRIPTION:
XS GIS Cut Line= 3
      1415803.36      6938022.98      1416248.00      6938697.15
      1416518.63      6939130.60
#Sta/Elev= 30
  4192.4 1893.09  4450.0 1891.26  4457.4 1890.05  4493.5 1888.98  4544.7 1888.90
  4550.7 1889.80  4557.8 1887.78  4586.8 1888.95  4692.3 1888.01  4731.3 1888.78
  4746.4 1887.37  4881.9 1883.65  4912.0 1883.35  4918.0 1884.44  4969.2 1882.98
  4988.2 1880.90  4988.5 1880.40  4992.2 1880.90  5020.7 1884.25  5026.6 1882.85
  5036.0 1884.20  5041.9 1882.89  5057.2 1884.93  5063.1 1883.05  5078.5 1884.48
  5084.4 1883.50  5093.8 1884.00  5099.7 1882.73  5267.2 1886.16  5511.0 1886.51
#Mann=4,-1,0
  4192.4   0.045       0  4692.3    0.07       0  4988.2    0.07       0
  4992.2    0.07       0
Bank Sta=4988.2,4992.2
Exp/Cntr=0.3,0.1

Chan Stop Cuts=-1