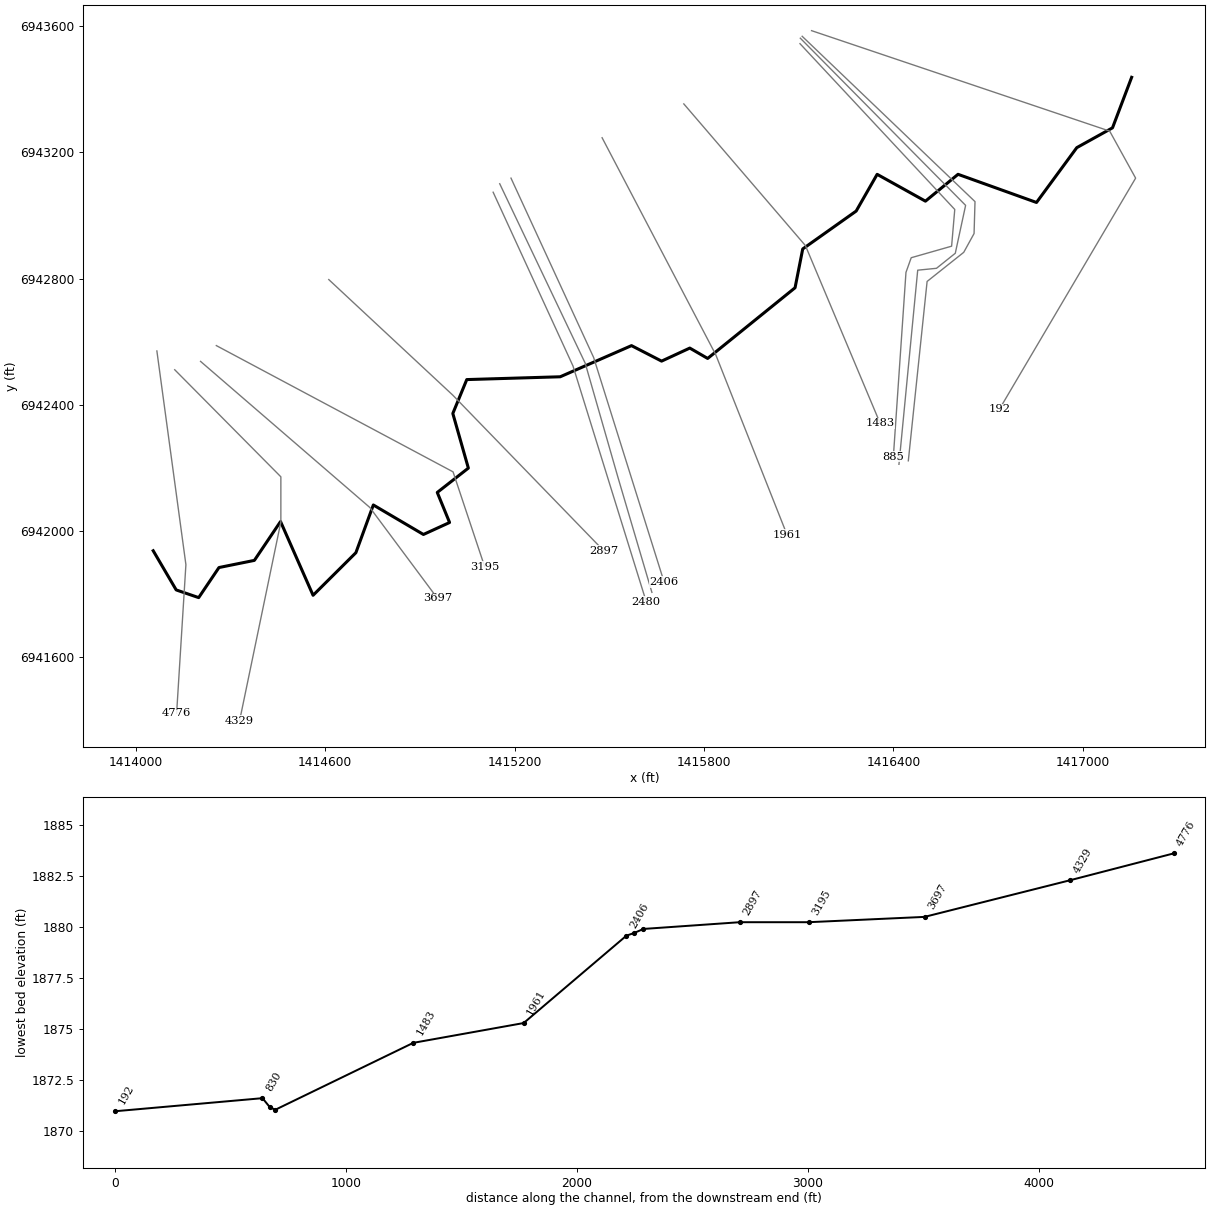
--- Plum Creek Trib12.prj (project) ---

Proj Title=Plum Creek Trib12 Base Level Engineering
Current Plan=p01
Default Exp/Contr=0.3,0.1
English Units
Geom File=g01
Flow File=f01
Plan File=p01
BEGIN DESCRIPTION:
Plum Creek Trib12
END DESCRIPTION:

--- Plum Creek Trib12.p01 (plan) ---

Plan Title=Multiple Run
Short Identifier=Multiple
Geom File=g01
Flow File=f01
Subcritical Flow
K Sum by GR= 0
Std Step Tol= 0.01
Critical Tol= 0.01
Num of Std Step Trials= 20
Max Error Tol= 0.3
Flow Tol Ratio= 0.001
Split Flow NTrial= 30
Split Flow Tol= 0.02
Split Flow Ratio= 0.02
Log Output Level= 0
Friction Slope Method= 1
Unsteady Friction Slope Method= 2
Unsteady Bridges Friction Slope Method= 1
Parabolic Critical Depth
Global Vel Dist=  1 , 1 , 1
Global Log Level= 0
CheckData=True
Encroach Param= -1, 0, 0, 0
BEGIN DESCRIPTION:
Multiple Run
END DESCRIPTION:

--- Plum Creek Trib12.f01 (steady flow) ---

Flow Title=Multiple
Number of Profiles=7
Profile Names=10-year,25-year,50-year,1pct_min,100-year,1pct_plu,500-year
River Rch & RM= Plum Creek Trib1,Reach-1,4776
     256     360     446     275     548    1094     840
River Rch & RM= Plum Creek Trib1,Reach-1,3697
     281     396     492     304     606    1209     932
Boundary for River Rch & Prof#=Plum Creek Trib1,Reach-1,1
Up Type=0
Dn Type=3
Dn Slope=0.005
Boundary for River Rch & Prof#=Plum Creek Trib1,Reach-1,2
Up Type=0
Dn Type=3
Dn Slope=0.005
Boundary for River Rch & Prof#=Plum Creek Trib1,Reach-1,3
Up Type=0
Dn Type=3
Dn Slope=0.005
Boundary for River Rch & Prof#=Plum Creek Trib1,Reach-1,4
Up Type=0
Dn Type=3
Dn Slope=0.005
Boundary for River Rch & Prof#=Plum Creek Trib1,Reach-1,5
Up Type=0
Dn Type=3
Dn Slope=0.005
Boundary for River Rch & Prof#=Plum Creek Trib1,Reach-1,6
Up Type=0
Dn Type=3
Dn Slope=0.005
Boundary for River Rch & Prof#=Plum Creek Trib1,Reach-1,7
Up Type=0
Dn Type=3
Dn Slope=0.005

--- Plum Creek Trib12.g01 (geometry) ---

Geom Title=Existing Conditions

River Reach=Plum Creek Trib1,Reach-1
Reach XY= 30
      1414055.00      6941938.00      1414127.84      6941813.87
      1414199.09      6941789.51      1414263.35      6941884.80
      1414375.52      6941907.48      1414458.44      6942030.61
      1414561.49      6941796.88      1414697.14      6941931.83
      1414752.43      6942083.05      1414911.13      6941989.59
      1414994.02      6942027.51      1414954.98      6942122.76
      1415053.47      6942199.88      1415004.27      6942372.96
      1415048.47      6942480.33      1415344.50      6942489.22
      1415570.40      6942587.90      1415665.70      6942538.83
      1415755.09      6942580.16      1415811.67      6942547.30
      1416088.56      6942771.21      1416112.86      6942894.19
      1416282.14      6943014.17      1416348.67      6943130.65
      1416501.67      6943045.62      1416604.91      6943130.69
      1416853.52      6943041.45      1416981.17      6943215.14
      1417094.38      6943277.99      1417155.00      6943438.00

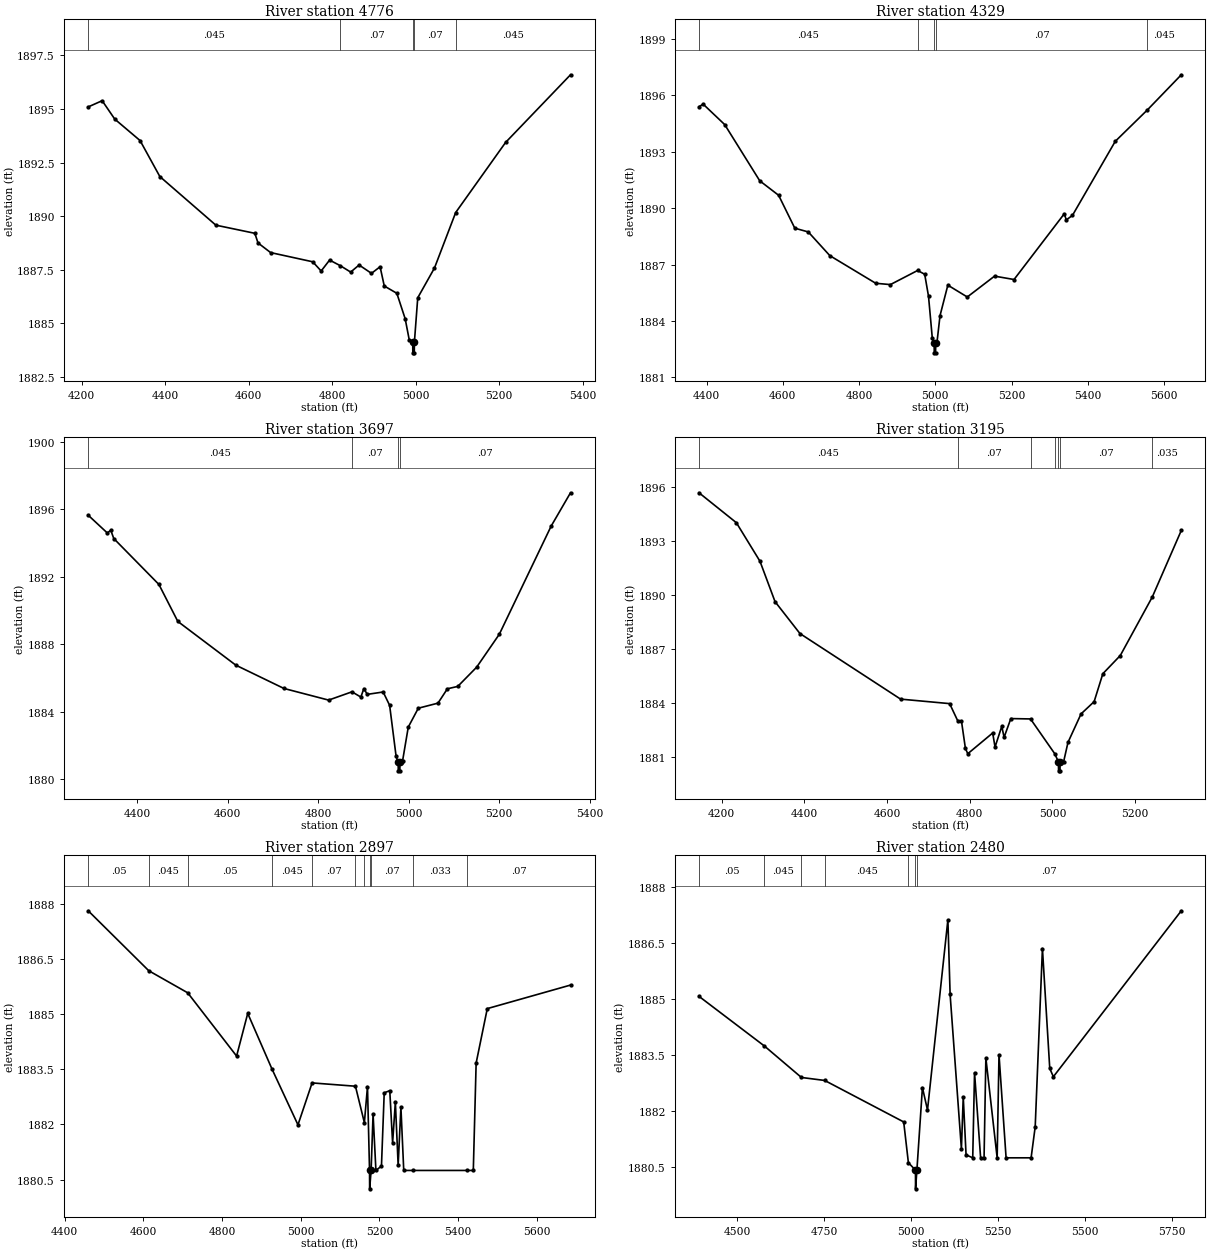
Type RM Length L Ch R = 1,4776,447,447,447
BEGIN DESCRIPTION:
Plum Creek Trib12 4.0
END DESCRIPTION:
XS GIS Cut Line= 3
      1414066.63      6942571.05      1414158.59      6941893.95
      1414129.15      6941422.69
#Sta/Elev= 30
  4215.6 1895.10  4249.0 1895.39  4279.2 1894.53  4339.8 1893.53  4387.2 1891.85
  4521.4 1889.58  4614.8 1889.20  4622.4 1888.75  4652.6 1888.30  4753.5 1887.87
  4773.7 1887.44  4793.9 1887.95  4819.4 1887.69  4844.4 1887.39  4864.6 1887.72
  4894.3 1887.33  4914.9 1887.64  4924.9 1886.74  4955.0 1886.40  4975.0 1885.21
  4985.0 1884.20  4993.1 1884.12  4993.3 1883.62  4996.8 1883.62  4997.1 1884.12
  5005.1 1886.19  5045.2 1887.58  5096.0 1890.17  5215.5 1893.44  5371.1 1896.60
#Mann=5,-1,0
  4215.6   0.045       0  4819.4    0.07       0  4993.1    0.07       0
  4997.1    0.07       0  5096.0   0.045       0
Bank Sta=4993.1,4997.1
Exp/Cntr=0.3,0.1

Type RM Length L Ch R = 1,4329,632,632,632
BEGIN DESCRIPTION:
Mapping XS 1784a56b
END DESCRIPTION:
XS GIS Cut Line= 4
      1414123.19      6942511.48      1414459.46      6942172.23
      1414459.46      6942029.38      1414328.51      6941398.44
#Sta/Elev= 30
  4380.3 1895.40  4391.1 1895.54  4447.7 1894.45  4539.6 1891.46  4589.1 1890.69
  4631.5 1888.94  4666.9 1888.74  4723.4 1887.48  4843.7 1886.01  4882.2 1885.94
  4953.6 1886.69  4972.2 1886.49  4982.2 1885.32  4992.2 1883.08  4997.0 1882.81
  4997.3 1882.31  5000.8 1882.31  5001.0 1882.81  5004.1 1882.81  5012.4 1884.29
  5032.9 1885.91  5083.9 1885.28  5155.4 1886.39  5206.5 1886.21  5338.4 1889.71
  5343.5 1889.38  5359.7 1889.62  5472.0 1893.56  5556.2 1895.23  5645.2 1897.10
#Mann=5,-1,0
  4380.3   0.045       0  4953.6    0.07       0  4997.0    0.07       0
  5001.0    0.07       0  5556.2   0.045       0
Bank Sta=4997,5001
Exp/Cntr=0.3,0.1

Type RM Length L Ch R = 1,3697,502,502,502
BEGIN DESCRIPTION:
Plum Creek Trib12 3.0
END DESCRIPTION:
XS GIS Cut Line= 3
      1414205.02      6942537.98      1414741.37      6942075.06
      1414954.98      6941788.02
#Sta/Elev= 30
  4291.5 1895.65  4333.7 1894.60  4341.4 1894.76  4348.0 1894.27  4447.8 1891.55
  4489.6 1889.36  4617.8 1886.77  4724.2 1885.39  4823.0 1884.70  4874.6 1885.19
  4894.3 1884.88  4900.9 1885.38  4908.5 1885.04  4943.6 1885.18  4957.9 1884.39
  4972.2 1881.37  4976.8 1881.01  4977.0 1880.51  4980.5 1880.51  4980.8 1881.01
  4986.4 1881.08  4999.1 1883.10  5021.3 1884.22  5064.8 1884.52  5085.6 1885.37
  5108.5 1885.51  5150.3 1886.65  5200.4 1888.60  5315.1 1895.01  5357.8 1896.98
#Mann=4,-1,0
  4291.5   0.045       0  4874.6    0.07       0  4976.8    0.07       0
  4980.8    0.07       0
Bank Sta=4976.8,4980.8
Exp/Cntr=0.3,0.1

Type RM Length L Ch R = 1,3195,298,298,298
BEGIN DESCRIPTION:
Plum Creek Trib12 2.0
END DESCRIPTION:
XS GIS Cut Line= 3
      1414254.98      6942588.01      1415005.00      6942188.00
      1415104.99      6941888.04
#Sta/Elev= 30
  4145.5 1895.68  4235.8 1894.02  4292.9 1891.88  4329.3 1889.64  4389.5 1887.87
  4632.9 1884.23  4751.5 1883.98  4770.8 1883.04  4780.2 1883.00  4789.7 1881.49
  4795.4 1881.20  4855.6 1882.35  4861.3 1881.57  4877.6 1882.72  4883.2 1882.11
  4899.5 1883.15  4947.1 1883.13  5005.4 1881.21  5014.6 1880.75  5014.9 1880.25
  5018.4 1880.25  5018.6 1880.75  5027.1 1880.75  5037.7 1881.83  5069.3 1883.41
  5100.9 1884.09  5122.0 1885.64  5164.2 1886.65  5241.6 1889.90  5311.7 1893.59
#Mann=7,-1,0
  4145.5   0.045       0  4770.8    0.07       0  4947.1   0.045       0
  5005.4    0.07       0  5014.6   0.045       0  5018.6    0.07       0
  5241.6   0.035       0
Bank Sta=5014.6,5018.6
Exp/Cntr=0.3,0.1

Type RM Length L Ch R = 1,2897,417,417,417
BEGIN DESCRIPTION:
Mapping XS e206ea70
END DESCRIPTION:
XS GIS Cut Line= 3
      1414611.26      6942797.16      1415004.06      6942431.14
      1415483.19      6941937.13
#Sta/Elev= 30
  4460.1 1887.81  4613.9 1886.18  4712.8 1885.58  4837.0 1883.86  4865.3 1885.02
  4926.8 1883.51  4992.9 1881.99  5028.8 1883.13  5138.9 1883.04  5161.6 1882.05
  5169.5 1883.03  5174.7 1880.75  5175.0 1880.25  5178.7 1880.75  5183.7 1882.28
  5190.9 1880.75  5205.0 1880.87  5212.0 1882.86  5226.1 1882.92  5233.3 1881.50
  5240.3 1882.61  5247.4 1880.89  5254.4 1882.47  5261.6 1880.75  5285.4 1880.75
  5422.5 1880.75  5438.3 1880.75  5445.5 1883.67  5473.8 1885.15  5685.2 1885.79
#Mann=11,-1,0
  4460.1    0.05       0  4613.9   0.045       0  4712.8    0.05       0
  4926.8   0.045       0  5028.8    0.07       0  5138.9   0.045       0
  5161.6    0.07       0  5174.7   0.045       0  5178.7    0.07       0
  5285.4   0.033       0  5422.5    0.07       0
Bank Sta=5174.7,5178.7
Exp/Cntr=0.3,0.1

Type RM Length L Ch R = 1,2480,41,41,41
BEGIN DESCRIPTION:
Mapping XS d5631a14
END DESCRIPTION:
XS GIS Cut Line= 3
      1415132.03      6943073.95      1415384.99      6942523.39
      1415617.11      6941776.42
#Sta/Elev= 30
  4389.6 1885.07  4578.0 1883.74  4684.3 1882.90  4751.3 1882.82  4978.7 1881.71
  4992.2 1880.62  5012.6 1880.42  5012.8 1879.92  5016.7 1880.42  5032.6 1882.63
  5047.2 1882.03  5105.9 1887.12  5112.3 1885.12  5144.8 1880.99  5150.1 1882.38
  5158.2 1880.83  5177.4 1880.75  5182.6 1883.03  5200.1 1880.75  5210.0 1880.75
  5215.2 1883.42  5247.7 1880.75  5253.0 1883.51  5273.4 1880.75  5345.4 1880.75
  5357.2 1881.58  5378.0 1886.35  5399.1 1883.14  5409.5 1882.92  5777.7 1887.36
#Mann=7,-1,0
  4389.6    0.05       0  4578.0   0.045       0  4684.3    0.05       0
  4751.3   0.045       0  4992.2    0.07       0  5012.6    0.07       0
  5016.7    0.07       0
Bank Sta=5012.6,5016.7
Exp/Cntr=0.3,0.1

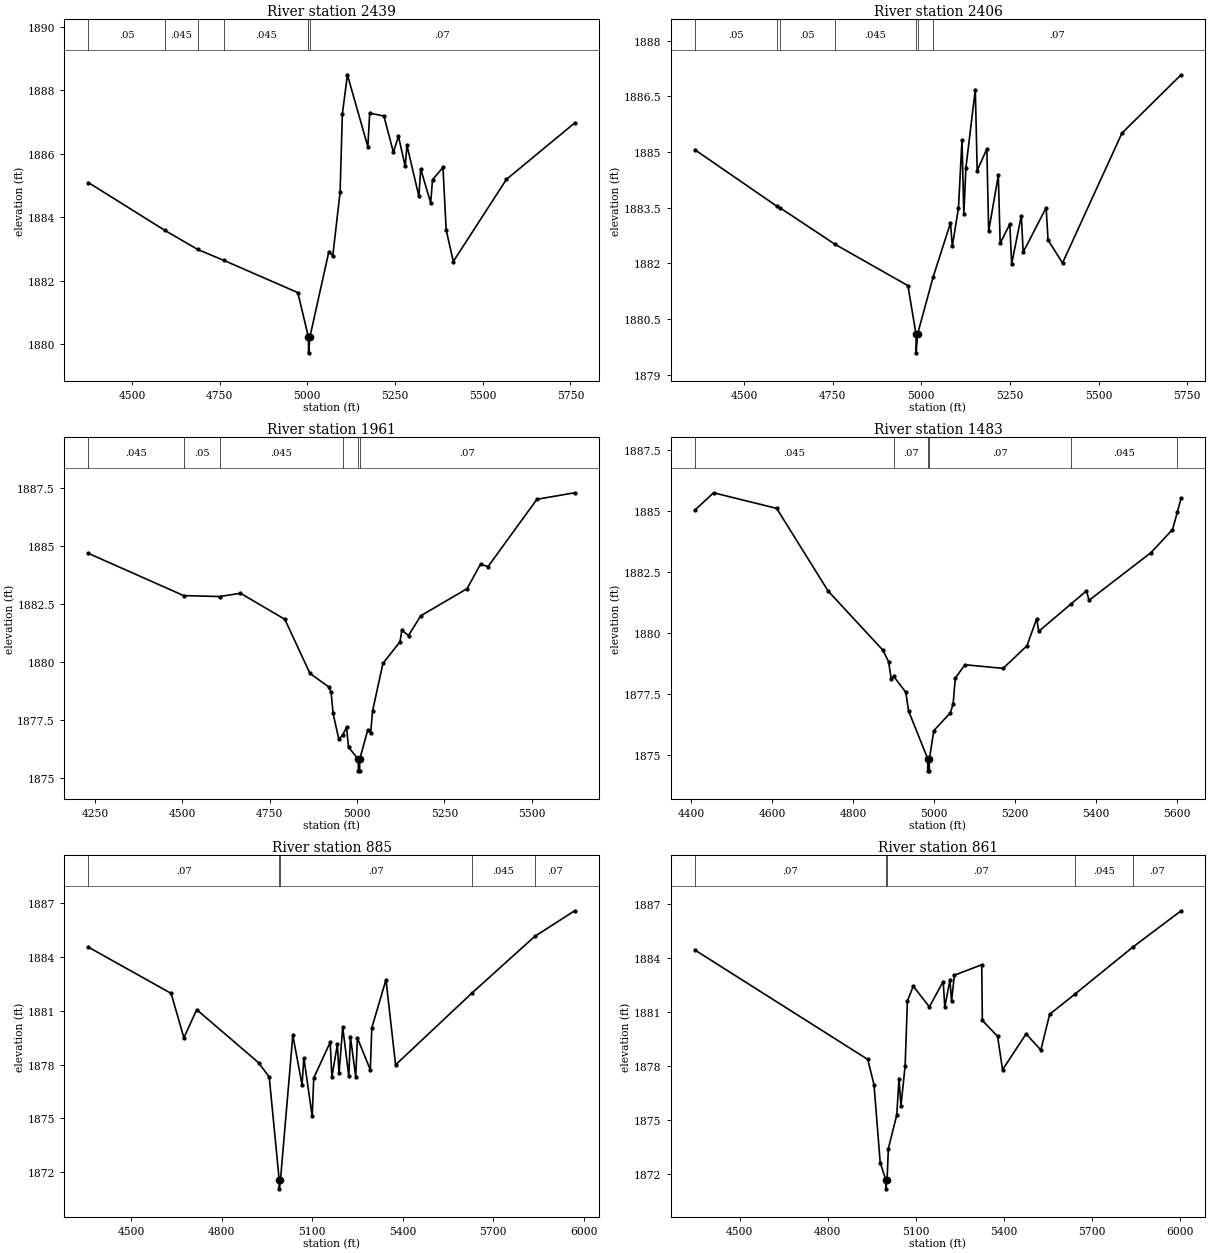
Type RM Length L Ch R = 1,2439,33,33,33
BEGIN DESCRIPTION:
Mapping XS f6e388a0
END DESCRIPTION:
XS GIS Cut Line= 4
      1415152.85      6943100.75      1415423.67      6942532.32
      1415527.83      6942169.25      1415634.97      6941806.20
#Sta/Elev= 30
  4376.0 1885.09  4594.2 1883.58  4687.5 1882.98  4761.2 1882.64  4972.8 1881.62
  5001.8 1880.28  5003.2 1880.22  5003.5 1879.72  5007.3 1880.22  5060.9 1882.89
  5072.6 1882.79  5093.4 1884.79  5099.8 1887.25  5114.2 1888.49  5172.5 1886.22
  5177.7 1887.28  5218.2 1887.19  5245.2 1886.05  5259.8 1886.55  5278.9 1885.60
  5284.1 1886.26  5317.9 1884.66  5323.1 1885.52  5351.6 1884.45  5356.8 1885.18
  5386.6 1885.57  5395.7 1883.60  5416.0 1882.60  5567.4 1885.19  5761.9 1886.97
#Mann=7,-1,0
  4376.0    0.05       0  4594.2   0.045       0  4687.5    0.05       0
  4761.2   0.045       0  5001.8    0.07       0  5003.2   0.045       0
  5007.3    0.07       0
Bank Sta=5003.2,5007.3
Exp/Cntr=0.3,0.1

Type RM Length L Ch R = 1,2406,445,445,445
BEGIN DESCRIPTION:
Mapping XS 622ca48a
END DESCRIPTION:
XS GIS Cut Line= 3
      1415188.57      6943118.60      1415450.46      6942550.18
      1415673.66      6941838.92
#Sta/Elev= 30
  4361.4 1885.06  4592.5 1883.54  4601.0 1883.50  4755.6 1882.52  4962.2 1881.40
  4985.2 1880.09  4985.4 1879.59  4989.3 1880.09  5033.3 1881.63  5082.3 1883.09
  5087.5 1882.46  5104.8 1883.49  5114.7 1885.32  5119.9 1883.33  5125.8 1884.58
  5152.3 1886.68  5157.6 1884.50  5184.8 1885.08  5190.0 1882.87  5217.2 1884.37
  5222.4 1882.54  5249.6 1883.06  5254.8 1881.99  5282.0 1883.28  5287.3 1882.30
  5352.1 1883.50  5357.4 1882.63  5398.3 1882.01  5566.0 1885.51  5732.7 1887.08
#Mann=7,-1,0
  4361.4    0.05       0  4592.5   0.045       0  4601.0    0.05       0
  4755.6   0.045       0  4985.2   0.045       0  4989.3   0.045       0
  5033.3    0.07       0
Bank Sta=4985.2,4989.3
Exp/Cntr=0.3,0.1

Type RM Length L Ch R = 1,1961,478,478,478
BEGIN DESCRIPTION:
Mapping XS f73d017a
END DESCRIPTION:
XS GIS Cut Line= 3
      1415477.26      6943246.51      1415837.33      6942559.10
      1416063.50      6941987.74
#Sta/Elev= 30
  4231.7 1884.68  4504.0 1882.86  4607.0 1882.82  4666.6 1882.96  4793.4 1881.84
  4865.2 1879.51  4918.6 1878.93  4925.8 1878.69  4931.4 1877.79  4947.8 1876.67
  4958.4 1876.85  4969.9 1877.18  4975.5 1876.33  5003.4 1875.81  5003.7 1875.31
  5007.4 1875.31  5007.6 1875.81  5030.4 1877.06  5038.9 1876.94  5044.3 1877.89
  5074.0 1879.94  5122.7 1880.87  5128.1 1881.37  5147.1 1881.14  5182.2 1881.99
  5314.6 1883.16  5353.0 1884.21  5374.6 1884.11  5514.4 1887.01  5622.2 1887.29
#Mann=6,-1,0
  4231.7   0.045       0  4504.0    0.05       0  4607.0   0.045       0
  4958.4    0.07       0  5003.4    0.07       0  5007.6    0.07       0
Bank Sta=5003.4,5007.6
Exp/Cntr=0.3,0.1

Type RM Length L Ch R = 1,1483,598,598,598
BEGIN DESCRIPTION:
Mapping XS ec313977
END DESCRIPTION:
XS GIS Cut Line= 3
      1415736.14      6943353.71      1416121.44      6942904.79
      1416357.87      6942342.47
#Sta/Elev= 30
  4408.4 1885.03  4454.6 1885.74  4610.5 1885.10  4737.8 1881.71  4872.8 1879.29
  4887.0 1878.82  4893.6 1878.12  4899.8 1878.21  4929.8 1877.56  4936.4 1876.80
  4983.7 1874.84  4984.0 1874.34  4987.7 1874.34  4988.0 1874.84  4998.9 1875.99
  5039.9 1876.72  5046.6 1877.09  5052.0 1878.14  5075.8 1878.69  5170.1 1878.54
  5229.1 1879.47  5252.9 1880.57  5258.3 1880.06  5338.5 1881.19  5376.2 1881.72
  5382.4 1881.33  5535.8 1883.29  5588.7 1884.23  5600.6 1884.94  5610.0 1885.52
#Mann=6,-1,0
  4408.4   0.045       0  4899.8    0.07       0  4983.7    0.07       0
  4988.0    0.07       0  5338.5   0.045       0  5600.6    0.07       0
Bank Sta=4983.7,4988
Exp/Cntr=0.3,0.1

Type RM Length L Ch R = 1,885,24,24,24
BEGIN DESCRIPTION:
Mapping XS 04234304
END DESCRIPTION:
XS GIS Cut Line= 6
      1416104.18      6943544.60      1416594.55      6943019.33
      1416584.57      6942902.97      1416456.59      6942866.41
      1416439.96      6942819.87      1416400.07      6942236.48
#Sta/Elev= 30
  4358.1 1884.55  4632.1 1881.97  4674.5 1879.49  4717.0 1881.06  4922.0 1878.10
  4957.3 1877.30  4990.3 1871.56  4990.6 1871.06  4994.6 1871.56  5035.5 1879.63
  5066.1 1876.86  5072.0 1878.38  5099.7 1875.11  5104.8 1877.25  5159.4 1879.24
  5164.9 1877.30  5183.1 1879.12  5188.5 1877.50  5200.9 1880.07  5221.0 1877.35
  5226.5 1879.53  5244.0 1877.31  5249.5 1879.48  5292.3 1877.70  5297.3 1880.05
  5344.2 1882.73  5376.0 1877.98  5628.5 1881.98  5837.3 1885.15  5969.4 1886.58
#Mann=5,-1,0
  4358.1    0.07       0  4990.3    0.07       0  4994.6    0.07       0
  5628.5   0.045       0  5837.3    0.07       0
Bank Sta=4990.3,4994.6
Exp/Cntr=0.3,0.1

Type RM Length L Ch R = 1,861,31,31,31
BEGIN DESCRIPTION:
Mapping XS 717534cb
END DESCRIPTION:
XS GIS Cut Line= 6
      1416105.21      6943561.97      1416628.94      6943032.28
      1416596.21      6942880.51      1416536.69      6942832.89
      1416477.17      6942826.94      1416417.75      6942211.93
#Sta/Elev= 30
  4347.2 1884.47  4936.8 1878.39  4958.0 1876.99  4979.2 1872.65  4998.3 1871.70
  4998.6 1871.20  5002.6 1871.70  5007.0 1873.44  5035.6 1875.30  5043.4 1877.33
  5049.9 1875.80  5064.2 1878.04  5071.9 1881.64  5092.0 1882.46  5146.7 1881.31
  5194.0 1882.72  5199.5 1881.29  5217.0 1882.81  5222.5 1881.63  5232.1 1883.07
  5325.4 1883.65  5327.5 1880.56  5379.5 1879.67  5396.4 1877.82  5476.8 1879.81
  5527.0 1878.91  5557.1 1880.90  5641.8 1882.00  5840.5 1884.63  6005.3 1886.65
#Mann=5,-1,0
  4347.2    0.07       0  4998.3    0.07       0  5002.6    0.07       0
  5641.8   0.045       0  5840.5    0.07       0
Bank Sta=4998.3,5002.6
Exp/Cntr=0.3,0.1

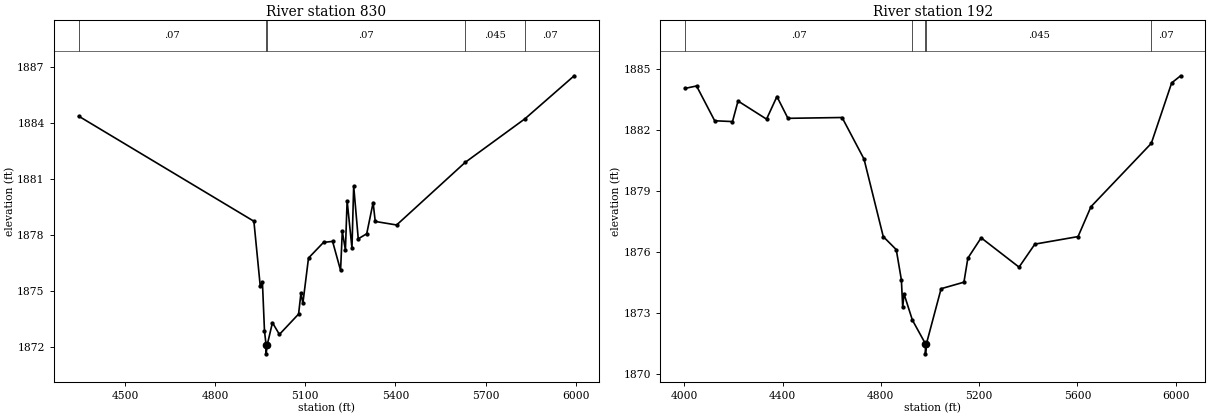
Type RM Length L Ch R = 1,830,638,638,638
BEGIN DESCRIPTION:
Mapping XS d2553727
END DESCRIPTION:
XS GIS Cut Line= 6
      1416111.11      6943567.97      1416658.70      6943044.19
      1416655.73      6942943.00      1416622.99      6942883.49
      1416506.93      6942791.23      1416447.42      6942222.95
#Sta/Elev= 30
  4345.9 1884.36  4929.0 1878.73  4950.0 1875.28  4957.4 1875.47  4964.2 1872.87
  4969.4 1872.13  4969.7 1871.63  4973.7 1872.13  4990.7 1873.30  5013.9 1872.67
  5077.7 1873.76  5085.5 1874.87  5092.0 1874.34  5110.7 1876.76  5160.8 1877.60
  5190.8 1877.65  5217.4 1876.10  5223.1 1878.19  5233.5 1877.19  5239.2 1879.83
  5255.3 1877.29  5261.0 1880.62  5276.2 1877.79  5304.4 1878.06  5325.7 1879.73
  5332.7 1878.72  5403.9 1878.53  5631.8 1881.88  5831.1 1884.22  5994.6 1886.52
#Mann=5,-1,0
  4345.9    0.07       0  4969.4    0.07       0  4973.7    0.07       0
  5631.8   0.045       0  5831.1    0.07       0
Bank Sta=4969.4,4973.7
Exp/Cntr=0.3,0.1

Type RM Length L Ch R = 1,192,0,0,0
BEGIN DESCRIPTION:
Plum Creek Trib12 1.0
END DESCRIPTION:
XS GIS Cut Line= 4
      1416140.87      6943585.82      1417085.38      6943267.52
      1417167.59      6943118.59      1416736.09      6942386.52
#Sta/Elev= 30
  4003.3 1884.03  4049.9 1884.15  4123.7 1882.44  4196.2 1882.40  4218.7 1883.41
  4334.8 1882.52  4377.0 1883.63  4421.8 1882.56  4642.2 1882.60  4731.4 1880.56
  4809.7 1876.75  4862.6 1876.11  4883.5 1874.62  4888.9 1873.27  4894.1 1873.94
  4928.2 1872.65  4981.1 1871.49  4981.4 1870.99  4985.5 1871.49  5045.1 1874.19
  5138.0 1874.51  5154.0 1875.69  5208.1 1876.69  5362.3 1875.25  5426.7 1876.38
  5602.4 1876.75  5655.1 1878.22  5900.5 1881.33  5983.4 1884.30  6019.9 1884.65
#Mann=5,-1,0
  4003.3    0.07       0  4928.2   0.045       0  4981.1   0.045       0
  4985.5   0.045       0  5900.5    0.07       0
Bank Sta=4981.1,4985.5
Exp/Cntr=0.3,0.1

Chan Stop Cuts=-1