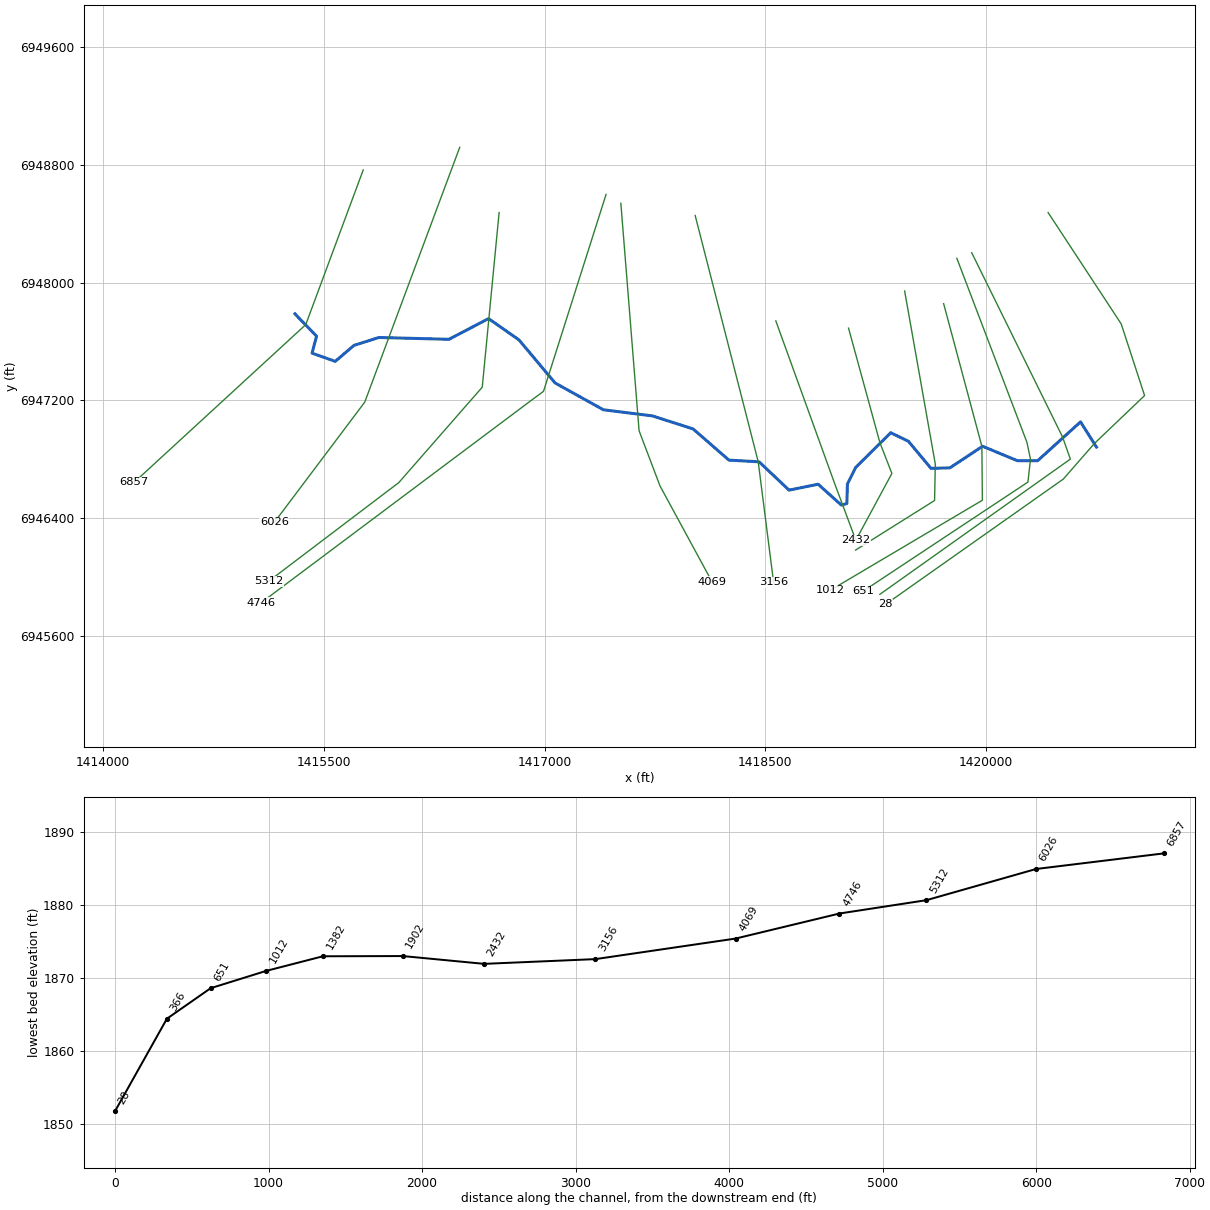
--- Plum Creek Trib13.prj (project) ---

Proj Title=Plum Creek Trib13 Base Level Engineering
Current Plan=p01
Default Exp/Contr=0.3,0.1
English Units
Geom File=g01
Flow File=f01
Plan File=p01
Y Axis Title=Elevation
X Axis Title(PF)=Main Channel Distance
X Axis Title(XS)=Station
BEGIN DESCRIPTION:
Plum Creek Trib13
END DESCRIPTION:
DSS Export Rating Curves= 0
DSS Export Rating Curve Sorted= 0
DSS Export Volume Flow Curves= 0
DXF OffsetX= 0
DXF OffsetY= 0
DXF ScaleX= 1
DXF ScaleY= 10

--- Plum Creek Trib13.p01 (plan) ---

Plan Title=Multiple Run
Short Identifier=Multiple
Geom File=g01
Flow File=f01
Subcritical Flow
K Sum by GR= 0
Std Step Tol= 0.01
Critical Tol= 0.01
Num of Std Step Trials= 20
Max Error Tol= 0.3
Flow Tol Ratio= 0.001
Split Flow NTrial= 30
Split Flow Tol= 0.02
Split Flow Ratio= 0.02
Log Output Level= 0
Friction Slope Method= 1
Unsteady Friction Slope Method= 2
Unsteady Bridges Friction Slope Method= 1
Parabolic Critical Depth
Global Vel Dist=  1 , 1 , 1
Global Log Level= 0
CheckData=True
Encroach Param= -1, 0, 0, 0
BEGIN DESCRIPTION:
Multiple Run
END DESCRIPTION:

--- Plum Creek Trib13.f01 (steady flow) ---

Flow Title=Multiple
Program Version=4.10
Number of Profiles= 7
Profile Names=10-year,25-year,50-year,1pct_min,100-year,1pct_plu,500-year
River Rch & RM=Plum Creek Trib1,Reach-1         ,6857
     273     386     481     298     595    1188     922
River Rch & RM=Plum Creek Trib1,Reach-1         ,6026
     359     513     643     401     799    1595    1251
River Rch & RM=Plum Creek Trib1,Reach-1         ,4069
     378     540     677     422     842    1679    1317
River Rch & RM=Plum Creek Trib1,Reach-1         ,28
    3234    4934    6466    4182    8344   16648   14072
Boundary for River Rch & Prof#=Plum Creek Trib1,Reach-1         , 1
Up Type= 0
Dn Type= 3
Dn Slope=0.03735
Boundary for River Rch & Prof#=Plum Creek Trib1,Reach-1         , 2
Up Type= 0
Dn Type= 3
Dn Slope=0.03735
Boundary for River Rch & Prof#=Plum Creek Trib1,Reach-1         , 3
Up Type= 0
Dn Type= 3
Dn Slope=0.03735
Boundary for River Rch & Prof#=Plum Creek Trib1,Reach-1         , 4
Up Type= 0
Dn Type= 3
Dn Slope=0.03735
Boundary for River Rch & Prof#=Plum Creek Trib1,Reach-1         , 5
Up Type= 0
Dn Type= 3
Dn Slope=0.03735
Boundary for River Rch & Prof#=Plum Creek Trib1,Reach-1         , 6
Up Type= 0
Dn Type= 3
Dn Slope=0.03735
Boundary for River Rch & Prof#=Plum Creek Trib1,Reach-1         , 7
Up Type= 0
Dn Type= 3
Dn Slope=0.03735
DSS Import GetInterval= 0
DSS Import GetPeak= 0
DSS Import FillOption= 0

--- Plum Creek Trib13.g01 (geometry) ---

Geom Title=Existing Conditions
Program Version=4.10

River Reach=Plum Creek Trib1,Reach-1
Reach XY= 30
        1415305.        6947788.      1415451.85      6947636.35
      1415421.11      6947520.84       1415578.9      6947465.28
      1415705.66       6947573.7      1415875.26      6947627.48
      1416350.96      6947615.07      1416619.84      6947755.71
      1416826.67      6947610.93      1417071.76      6947318.44
      1417399.89      6947136.15      1417733.22      6947094.48
      1418009.26      6947005.94      1418252.55        6946794.
      1418457.45      6946782.54      1418660.86      6946590.05
      1418858.42       6946630.2      1419016.14      6946488.34
      1419053.36      6946499.14      1419057.25      6946632.06
      1419113.14      6946744.06      1419351.59      6946980.23
      1419472.05      6946921.52      1419624.99      6946737.93
      1419753.53      6946741.54      1419975.17       6946888.3
      1420210.94      6946790.25      1420349.14      6946790.05
       1420640.4      6947053.92      1420748.75      6946882.58

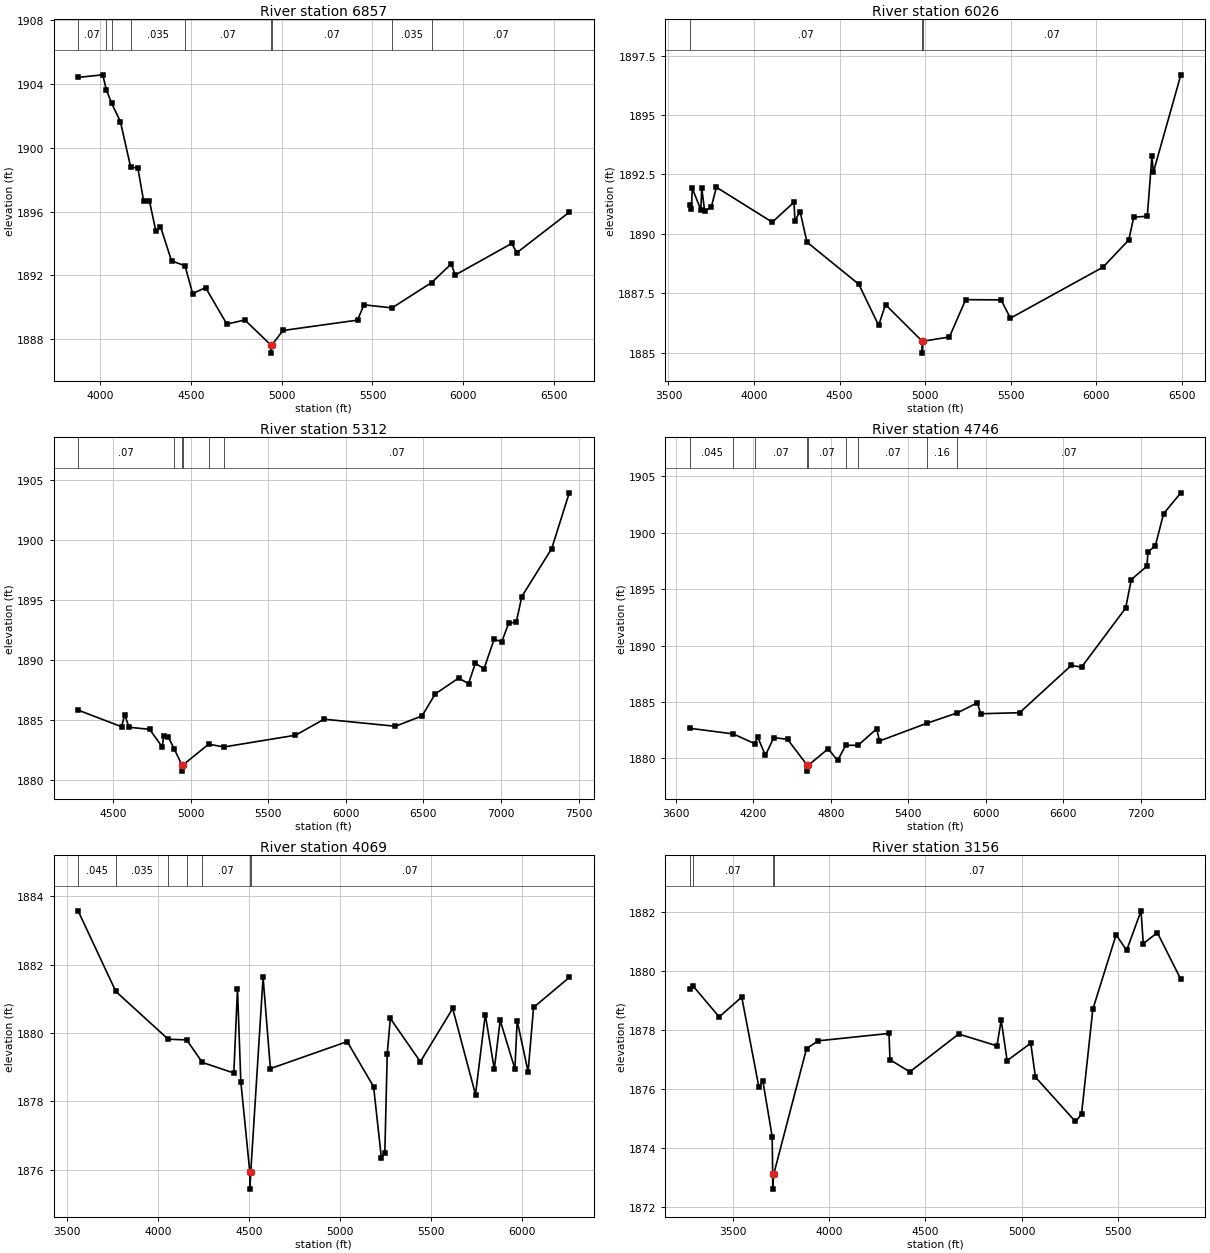
Type RM Length L Ch R = 1 ,6857    ,831,831,831
BEGIN DESCRIPTION:
Plum Creek Trib13 2.0
END DESCRIPTION:
XS GIS Cut Line= 3
      1415768.79      6948766.37       1415378.4      6947714.69
      1414212.41      6946642.23
#Sta/Elev= 30
  3878.2 1904.42  4014.1 1904.58  4033.3 1903.65  4062.7  1902.8  4111.1 1901.65
  4168.2 1898.77  4207.1 1898.75  4239.1 1896.68  4271.1 1896.67  4307.1 1894.76
  4332.1 1895.06  4392.9 1892.91  4467.2  1892.6    4509 1890.86  4580.5 1891.23
  4697.8 1888.94  4796.7  1889.2  4941.2 1887.62  4941.5 1887.12  4945.2 1887.62
    5007 1888.54  5417.6 1889.19    5453 1890.15    5608 1889.96  5826.2 1891.55
  5934.2 1892.72  5955.7 1892.02  6267.1    1894  6295.4 1893.42  6584.2 1895.96
#Mann= 9 ,-1 , 0
  3878.2     .07       0  4033.3    .035       0  4062.7     .07       0
  4168.2    .035       0  4467.2     .07       0  4941.2     .07       0
  4945.2     .07       0    5608    .035       0  5826.2     .07       0
Bank Sta=4941.2,4945.2
XS Rating Curve= 0 ,0
Exp/Cntr=0.3,0.1

Type RM Length L Ch R = 1 ,6026    ,714,714,714
BEGIN DESCRIPTION:
Mapping XS 625c6456
END DESCRIPTION:
XS GIS Cut Line= 3
      1416424.26      6948919.97      1415779.23      6947188.29
      1415165.57      6946371.81
#Sta/Elev= 30
  3623.8  1891.2  3633.6 1891.05    3639 1891.91    3689 1891.01  3694.3 1891.92
  3711.3 1890.96  3749.6 1891.12  3779.9 1891.96  4106.1 1890.49  4233.2 1891.33
  4238.6 1890.56  4268.9 1890.93  4308.9 1889.65  4611.5 1887.88  4727.5 1886.15
  4767.7 1887.02  4982.2 1885.48  4982.5 1884.98  4986.8 1885.48  5141.2 1885.66
  5236.1 1887.23  5443.1 1887.22  5497.1 1886.45  6038.8  1888.6  6188.8 1889.74
  6217.9  1890.7    6297 1890.74  6324.1 1893.27  6332.5 1892.59  6493.1 1896.69
#Mann= 3 ,-1 , 0
  3623.8     .07       0  4982.2     .07       0  4986.8     .07       0
Bank Sta=4982.2,4986.8
XS Rating Curve= 0 ,0
Exp/Cntr=0.3,0.1

Type RM Length L Ch R = 1 ,5312    ,566,566,566
BEGIN DESCRIPTION:
Mapping XS 5d0faed6
END DESCRIPTION:
XS GIS Cut Line= 4
      1416691.72      6948476.95      1416577.14       6947289.5
      1416010.22      6946641.11      1415124.82      6945969.25
#Sta/Elev= 30
  4273.9  1885.8  4554.1 1884.41  4574.2 1885.42  4601.8 1884.37    4735 1884.19
  4816.4 1882.72  4825.4 1883.61  4855.5 1883.55  4893.1 1882.56  4943.5  1881.2
  4943.9  1880.7  4948.4  1881.2  5115.1 1882.95  5213.7 1882.72    5675  1883.7
  5859.1 1885.04  6319.5 1884.45    6491 1885.32  6576.3 1887.16  6726.1 1888.47
  6790.6 1888.02  6834.2 1889.71  6890.4 1889.26  6954.9 1891.71  7004.8 1891.52
  7048.4 1893.04  7098.4 1893.18  7133.7 1895.29  7326.4  1899.3  7439.6 1903.96
#Mann= 6 ,-1 , 0
  4273.9     .07       0  4893.1    .035       0  4943.5     .07       0
  4948.4    .035       0  5115.1    .035       0  5213.7     .07       0
Bank Sta=4943.5,4948.4
XS Rating Curve= 0 ,0
Exp/Cntr=0.3,0.1

Type RM Length L Ch R = 1 ,4746    ,677,677,677
BEGIN DESCRIPTION:
Mapping XS 27f71c32
END DESCRIPTION:
XS GIS Cut Line= 4
      1417418.08       6948599.8      1416993.18      6947261.52
      1416916.23      6947204.64      1415072.78       6945822.9
#Sta/Elev= 30
  3707.2 1882.67  4044.6 1882.17  4209.2 1881.31  4234.3 1881.88  4293.5 1880.27
  4358.1 1881.84  4465.3 1881.69  4618.9 1879.37  4619.3 1878.87  4623.8 1879.37
  4779.3 1880.85  4852.5 1879.82  4915.9 1881.16  5010.8 1881.16  5155.9 1882.63
  5176.8 1881.54  5545.2 1883.12  5779.1 1884.03  5933.4 1884.92  5962.3 1883.96
  6262.3 1884.05  6662.4 1888.25  6741.6 1888.09  7083.3 1893.33    7127 1895.86
  7247.8 1897.04  7256.2 1898.33  7312.4 1898.82    7377  1901.7  7510.8 1903.55
#Mann= 9 ,-1 , 0
  3707.2    .045       0  4044.6    .035       0  4209.2     .07       0
  4618.9     .07       0  4623.8     .07       0  4915.9     .16       0
  5010.8     .07       0  5545.2     .16       0  5779.1     .07       0
Bank Sta=4618.9,4623.8
XS Rating Curve= 0 ,0
Exp/Cntr=0.3,0.1

Type RM Length L Ch R = 1 ,4069    ,913,913,913
BEGIN DESCRIPTION:
Mapping XS 519dee9e
END DESCRIPTION:
XS GIS Cut Line= 4
      1417518.47      6948539.59      1417642.26      6946993.86
      1417784.62      6946618.07       1418138.5      6945965.82
#Sta/Elev= 30
  3562.8 1883.58  3769.7 1881.22    4057 1879.82  4158.4  1879.8  4244.6 1879.14
  4417.1 1878.83  4437.2  1881.3  4455.5 1878.58  4504.8 1875.93  4505.2 1875.43
    4510 1875.93  4577.6 1881.63  4617.8 1878.96  5039.1 1879.75  5183.9 1878.43
  5226.7 1876.34  5245.5 1876.49  5258.8 1879.39  5275.6 1880.43  5440.5 1879.16
  5617.8 1880.72    5743  1878.2  5796.7 1880.54  5846.1 1878.94  5878.4 1880.37
  5959.1 1878.95  5971.6 1880.36  6031.5 1878.87  6061.5 1880.75  6257.4 1881.63
#Mann= 7 ,-1 , 0
  3562.8    .045       0  3769.7    .035       0    4057     .07       0
  4158.4    .035       0  4244.6     .07       0  4504.8     .07       0
    4510     .07       0
Bank Sta=4504.8,4510
XS Rating Curve= 0 ,0
Exp/Cntr=0.3,0.1

Type RM Length L Ch R = 1 ,3156    ,724,724,724
BEGIN DESCRIPTION:
Mapping XS e94797dc
END DESCRIPTION:
XS GIS Cut Line= 3
      1418023.24      6948456.46      1418451.27      6946783.52
      1418555.74      6945964.18
#Sta/Elev= 30
  3275.1 1879.39  3293.3 1879.48  3428.5 1878.44  3545.7 1879.11  3634.8 1876.06
  3655.4 1876.27  3703.8 1874.39  3706.4 1873.11  3706.8 1872.61  3711.6 1873.11
  3882.5 1877.37  3943.6 1877.63  4310.9 1877.88  4316.1 1876.99  4419.3 1876.58
  4673.1 1877.86    4872 1877.46  4894.1 1878.33    4925 1876.96  5047.8 1877.55
    5072  1876.4  5279.7  1874.9  5311.5 1875.14  5370.4  1878.7  5491.4 1881.22
  5546.1 1880.69  5620.9 1882.03  5632.5 1880.92  5705.8 1881.29  5827.9 1879.71
#Mann= 4 ,-1 , 0
  3275.1    .045       0  3293.3     .07       0  3706.4     .07       0
  3711.6     .07       0
Bank Sta=3706.4,3711.6
XS Rating Curve= 0 ,0
Exp/Cntr=0.3,0.1

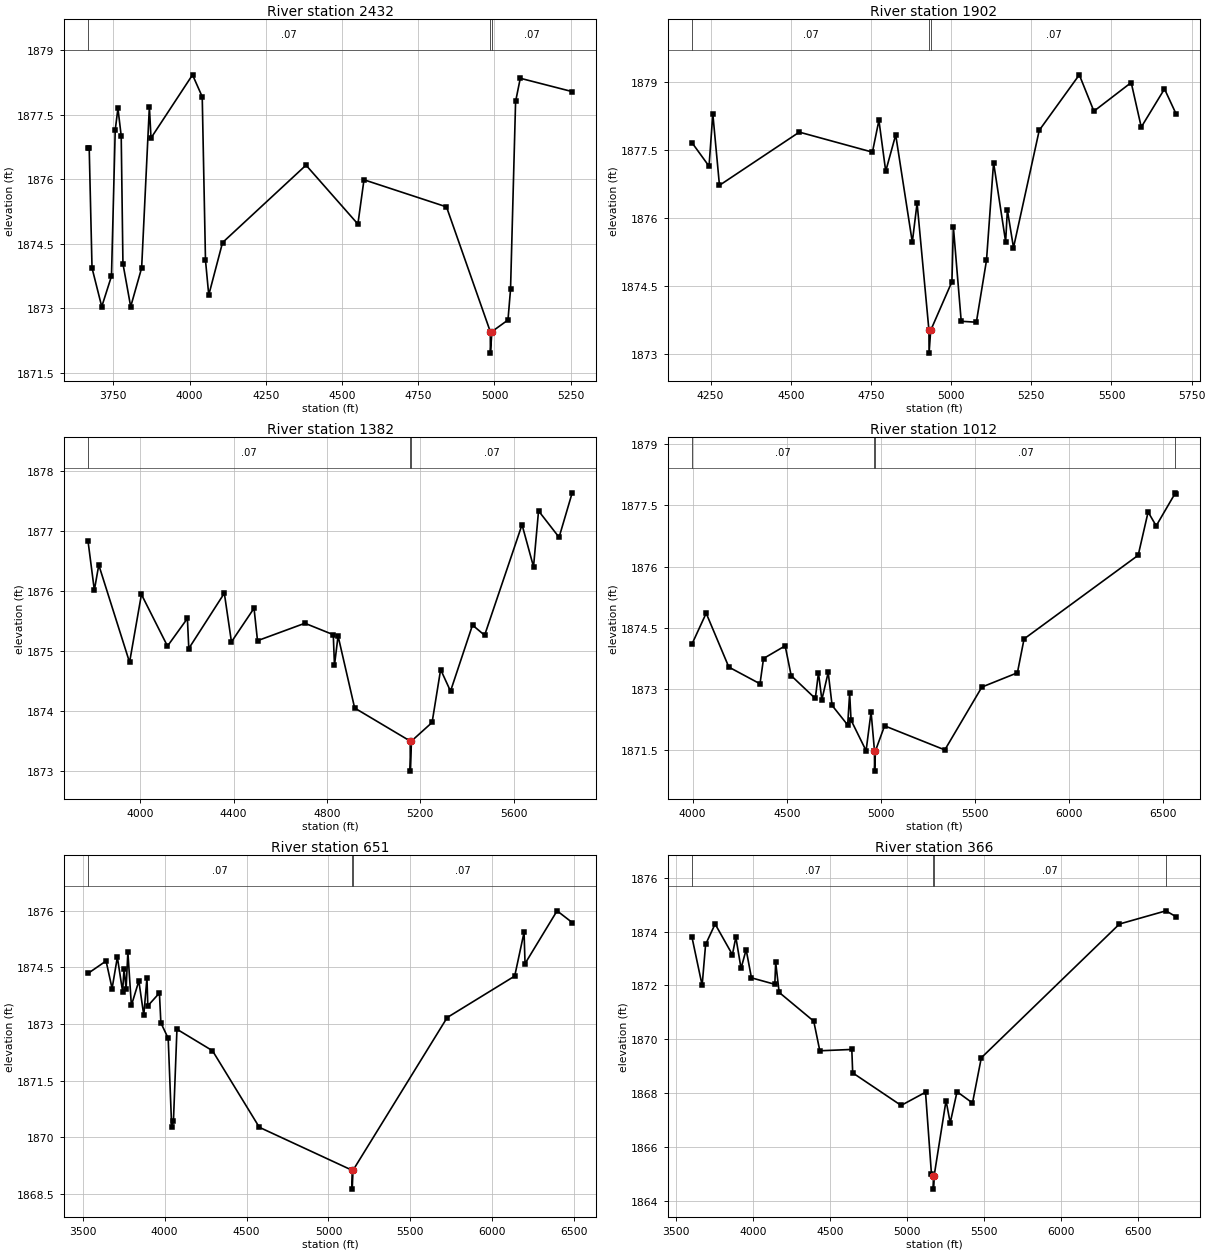
Type RM Length L Ch R = 1 ,2432    ,530,530,530
BEGIN DESCRIPTION:
Mapping XS 48eb71e5
END DESCRIPTION:
XS GIS Cut Line= 3
      1418570.89      6947740.39      1418968.93      6946639.31
      1419114.65      6946248.51
#Sta/Elev= 30
    3667 1876.74  3670.9 1876.74  3680.2 1873.94  3712.1 1873.04    3744 1873.75
  3756.3 1877.15  3765.2 1877.65  3775.9 1877.01  3781.6 1874.04    3807 1873.04
  3842.9 1873.94  3868.3 1877.69  3873.6 1876.96  4009.8 1878.43  4041.6 1877.92
  4052.3 1874.12    4063 1873.31  4108.2 1874.53    4382 1876.33  4552.1 1874.96
  4572.1 1875.99  4842.7 1875.36  4986.3 1872.46  4986.7 1871.96  4991.6 1872.46
  5044.3 1872.73  5052.7 1873.44  5069.3 1877.81  5084.7 1878.35  5254.9 1878.04
#Mann= 3 ,-1 , 0
    3667     .07       0  4986.3     .07       0  4991.6     .07       0
Bank Sta=4986.3,4991.6
XS Rating Curve= 0 ,0
Exp/Cntr=0.3,0.1

Type RM Length L Ch R = 1 ,1902    ,520,520,520
BEGIN DESCRIPTION:
Mapping XS 9b48051e
END DESCRIPTION:
XS GIS Cut Line= 4
      1419064.89      6947690.88      1419278.19      6946911.34
      1419359.23      6946703.56      1419132.17      6946282.39
#Sta/Elev= 30
  4191.8 1877.66  4245.2 1877.14    4257 1878.29  4277.7 1876.72  4526.6 1877.89
  4754.6 1877.45  4774.9 1878.15  4796.1 1877.03  4827.2 1877.83    4879 1875.47
  4893.9 1876.33  4930.9 1873.53  4931.3 1873.03  4936.3 1873.53  5002.5  1874.6
    5007 1875.81  5031.5 1873.73  5078.7 1873.71  5110.3 1875.07  5132.4 1877.22
    5170 1875.48  5175.4 1876.18  5194.5 1875.35  5274.8 1877.93  5399.7 1879.15
  5445.2 1878.35  5561.5 1878.98  5592.9    1878  5665.3 1878.84  5701.5 1878.29
#Mann= 3 ,-1 , 0
  4191.8     .07       0  4930.9     .07       0  4936.3     .07       0
Bank Sta=4930.9,4936.3
XS Rating Curve= 0 ,0
Exp/Cntr=0.3,0.1

Type RM Length L Ch R = 1 ,1382    ,370,370,370
BEGIN DESCRIPTION:
Mapping XS 1d7cb741
END DESCRIPTION:
XS GIS Cut Line= 4
       1419445.9      6947943.48      1419654.23      6946766.41
      1419649.16      6946519.53      1419112.88      6946182.84
#Sta/Elev= 30
  3775.7 1876.83  3802.9 1876.01  3821.9 1876.43  3953.9 1874.81  4004.7 1875.94
  4116.4 1875.08  4201.8 1875.54  4207.8 1875.04  4360.1 1875.96  4390.6 1875.15
  4487.4 1875.71  4502.3 1875.17  4705.4 1875.46  4827.1 1875.27  4832.2 1874.76
  4847.6 1875.25  4918.7 1874.05  5156.8  1873.5  5157.3    1873  5162.2  1873.5
  5250.7 1873.81  5287.3 1874.69  5329.7 1874.33  5423.9 1875.43  5475.8 1875.26
  5636.2  1877.1  5685.5  1876.4    5707 1877.33    5795 1876.89  5851.2 1877.63
#Mann= 3 ,-1 , 0
  3775.7     .07       0  5156.8     .07       0  5162.2     .07       0
Bank Sta=5156.8,5162.2
XS Rating Curve= 0 ,0
Exp/Cntr=0.3,0.1

Type RM Length L Ch R = 1 ,1012    ,361,361,361
BEGIN DESCRIPTION:
Mapping XS ee40eb9d
END DESCRIPTION:
XS GIS Cut Line= 4
      1419710.75      6947857.46      1419970.39      6946887.92
      1419973.81      6946521.27      1418939.57      6945908.71
#Sta/Elev= 30
  3996.3  1874.1  4072.1 1874.86  4192.4 1873.54  4358.1 1873.13  4376.8 1873.75
  4491.7 1874.06  4523.7 1873.33  4651.9 1872.77  4668.6  1873.4  4686.7 1872.74
  4720.4 1873.41  4741.1  1872.6  4823.9 1872.12  4834.3  1872.9  4841.7 1872.24
  4921.7 1871.49  4948.2 1872.44  4966.2 1871.49  4966.6 1870.99  4971.6 1871.49
  5019.9  1872.1  5339.9 1871.51  5536.8 1873.05  5725.6  1873.4    5761 1874.23
  6367.3 1876.28    6420 1877.34  6462.9    1877  6565.2 1877.81  6568.7 1877.79
#Mann= 4 ,-1 , 0
  3996.3     .07       0  4966.2     .07       0  4971.6     .07       0
  6565.2    .035       0
Bank Sta=4966.2,4971.6
XS Rating Curve= 0 ,0
Exp/Cntr=0.3,0.1

Type RM Length L Ch R = 1 ,651     ,285,285,285
BEGIN DESCRIPTION:
Mapping XS 71d325ce
END DESCRIPTION:
XS GIS Cut Line= 5
      1419800.54      6948165.53      1420276.24      6946915.54
      1420300.54      6946800.95      1420283.18       6946644.7
      1419162.68      6945902.33
#Sta/Elev= 30
  3531.9 1874.34  3642.2 1874.67    3679 1873.94  3711.1 1874.77  3743.2 1873.86
  3751.9 1874.46  3764.6 1873.93  3775.3 1874.91  3796.7 1873.49  3842.3 1874.14
  3872.4 1873.23  3891.8 1874.22  3897.1 1873.48  3967.9 1873.82  3976.8 1873.03
  4021.4 1872.62  4042.8 1870.26  4053.5 1870.42  4074.9 1872.86  4291.9 1872.29
  4577.8 1870.26  5144.4 1869.12  5144.8 1868.62  5149.8 1869.12  5724.7 1873.17
  6136.9 1874.27    6194 1875.43    6200  1874.6  6395.6    1876  6487.8 1875.69
#Mann= 3 ,-1 , 0
  3531.9     .07       0  5144.4    .035       0  5149.8     .07       0
Bank Sta=5144.4,5149.8
XS Rating Curve= 0 ,0
Exp/Cntr=0.3,0.1

Type RM Length L Ch R = 1 ,366     ,338,338,338
BEGIN DESCRIPTION:
Mapping XS 52bc1639
END DESCRIPTION:
XS GIS Cut Line= 4
      1419901.25      6948203.71      1420518.29      6946951.26
      1420571.38      6946800.95      1419277.81      6945881.93
#Sta/Elev= 30
  3603.8  1873.8  3670.2    1872  3692.6 1873.52  3754.4 1874.28  3866.6 1873.14
  3888.9 1873.79  3922.8 1872.63  3955.7 1873.33  3990.2 1872.28  4141.9 1872.04
  4147.4 1872.86  4169.9 1871.74  4394.5 1870.67  4433.9 1869.57  4641.6 1869.62
  4647.2 1868.75  4961.6 1867.54    5120 1868.03  5158.3    1865  5170.6 1864.93
    5171 1864.43    5176 1864.93  5253.1 1867.72  5280.2 1866.89  5324.5 1868.05
  5424.8 1867.63    5482 1869.31  6378.6 1874.28  6680.2 1874.77  6746.2 1874.55
#Mann= 4 ,-1 , 0
  3603.8     .07       0  5170.6     .07       0    5176     .07       0
  6680.2    .045       0
Bank Sta=5170.6,5176
XS Rating Curve= 0 ,0
Exp/Cntr=0.3,0.1

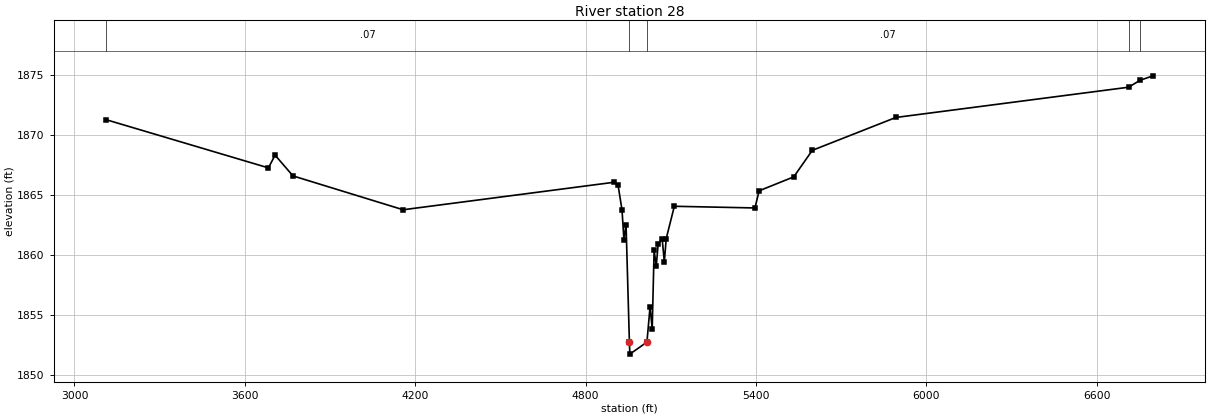
Type RM Length L Ch R = 1 ,28      ,0,0,0
BEGIN DESCRIPTION:
Mapping XS f6a6c02c
END DESCRIPTION:
XS GIS Cut Line= 6
      1420420.25      6948476.62      1420916.66      6947719.76
      1421075.51      6947232.79      1420734.65      6946907.07
      1420523.43      6946665.08       1419316.1      6945813.41
#Sta/Elev= 30
  3110.6 1871.27    3683 1867.25  3706.4 1868.31  3769.6 1866.58  4157.5 1863.76
    4900 1866.05  4914.2 1865.84  4928.4 1863.74  4935.1 1861.25  4942.6 1862.52
  4954.4 1852.73  4955.9 1851.73  5016.1 1852.73  5027.1 1855.66  5034.7 1853.85
  5041.4 1860.39    5049 1859.08  5055.6 1860.91  5069.8 1861.33  5077.4 1859.43
  5084.1 1861.36  5112.6 1864.05  5396.5 1863.91  5411.3 1865.34  5533.2  1866.5
  5598.5 1868.71  5892.8 1871.45  6712.3 1873.97  6753.1 1874.55  6798.7 1874.92
#Mann= 5 ,-1 , 0
  3110.6     .07       0  4954.4     .07       0  5016.1     .07       0
  6712.3    .045       0  6753.1     .07       0
Bank Sta=4954.4,5016.1
XS Rating Curve= 0 ,0
Exp/Cntr=0.3,0.1

Chan Stop Cuts=-1
Use User Specified Reach Order=0
Composite Channel Slope=5