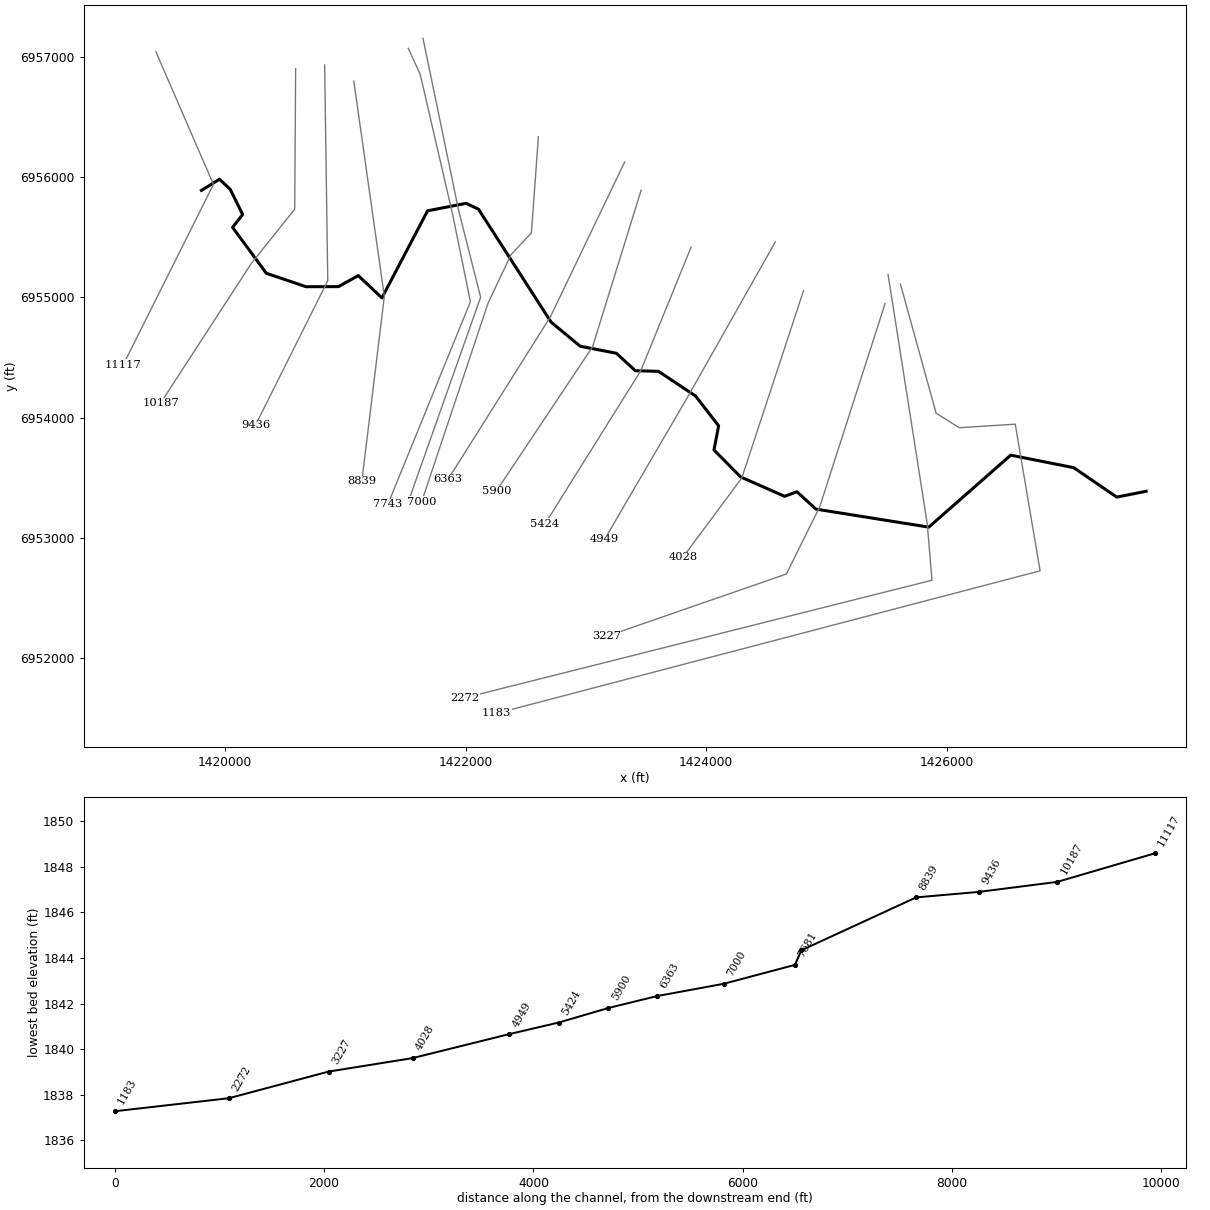
--- Plum Creek Trib15.prj (project) ---

Proj Title=Plum Creek Trib15 Base Level Engineering
Current Plan=p01
Default Exp/Contr=0.3,0.1
English Units
Geom File=g01
Flow File=f01
Plan File=p01
BEGIN DESCRIPTION:
Plum Creek Trib15
END DESCRIPTION:

--- Plum Creek Trib15.p01 (plan) ---

Plan Title=Multiple Run
Short Identifier=Multiple
Geom File=g01
Flow File=f01
Subcritical Flow
K Sum by GR= 0
Std Step Tol= 0.01
Critical Tol= 0.01
Num of Std Step Trials= 20
Max Error Tol= 0.3
Flow Tol Ratio= 0.001
Split Flow NTrial= 30
Split Flow Tol= 0.02
Split Flow Ratio= 0.02
Log Output Level= 0
Friction Slope Method= 1
Unsteady Friction Slope Method= 2
Unsteady Bridges Friction Slope Method= 1
Parabolic Critical Depth
Global Vel Dist=  1 , 1 , 1
Global Log Level= 0
CheckData=True
Encroach Param= -1, 0, 0, 0
BEGIN DESCRIPTION:
Multiple Run
END DESCRIPTION:

--- Plum Creek Trib15.f01 (steady flow) ---

Flow Title=Multiple
Number of Profiles=7
Profile Names=10-year,25-year,50-year,1pct_min,100-year,1pct_plu,500-year
River Rch & RM= Plum Creek Trib1,Reach-1,11117
     168     228     277     167     334     667     492
River Rch & RM= Plum Creek Trib1,Reach-1,10187
     280     391     483     296     592    1180     898
River Rch & RM= Plum Creek Trib1,Reach-1,5424
     345     486     604     373     743    1483    1140
River Rch & RM= Plum Creek Trib1,Reach-1,1183
     414     590     738     458     914    1825    1421
Boundary for River Rch & Prof#=Plum Creek Trib1,Reach-1,1
Up Type=0
Dn Type=3
Dn Slope=0.005
Boundary for River Rch & Prof#=Plum Creek Trib1,Reach-1,2
Up Type=0
Dn Type=3
Dn Slope=0.005
Boundary for River Rch & Prof#=Plum Creek Trib1,Reach-1,3
Up Type=0
Dn Type=3
Dn Slope=0.005
Boundary for River Rch & Prof#=Plum Creek Trib1,Reach-1,4
Up Type=0
Dn Type=3
Dn Slope=0.005
Boundary for River Rch & Prof#=Plum Creek Trib1,Reach-1,5
Up Type=0
Dn Type=3
Dn Slope=0.005
Boundary for River Rch & Prof#=Plum Creek Trib1,Reach-1,6
Up Type=0
Dn Type=3
Dn Slope=0.005
Boundary for River Rch & Prof#=Plum Creek Trib1,Reach-1,7
Up Type=0
Dn Type=3
Dn Slope=0.005

--- Plum Creek Trib15.g01 (geometry) ---

Geom Title=Existing Conditions

River Reach=Plum Creek Trib1,Reach-1
Reach XY= 30
      1419805.00      6955888.00      1419955.10      6955980.74
      1420044.24      6955897.73      1420147.69      6955687.91
      1420063.90      6955581.07      1420345.00      6955199.24
      1420675.20      6955087.78      1420944.30      6955088.80
      1421108.41      6955180.23      1421305.01      6954995.07
      1421684.52      6955718.83      1422004.92      6955780.70
      1422107.29      6955732.20      1422710.62      6954793.62
      1422952.57      6954593.52      1423253.53      6954534.46
      1423410.85      6954390.06      1423603.54      6954384.46
      1423911.06      6954179.86      1424102.77      6953932.07
      1424064.13      6953731.26      1424284.91      6953507.77
      1424651.60      6953345.83      1424753.29      6953384.64
      1424910.68      6953240.01      1425849.03      6953090.14
      1426529.91      6953688.21      1427053.45      6953584.25
      1427411.12      6953339.84      1427655.00      6953388.00

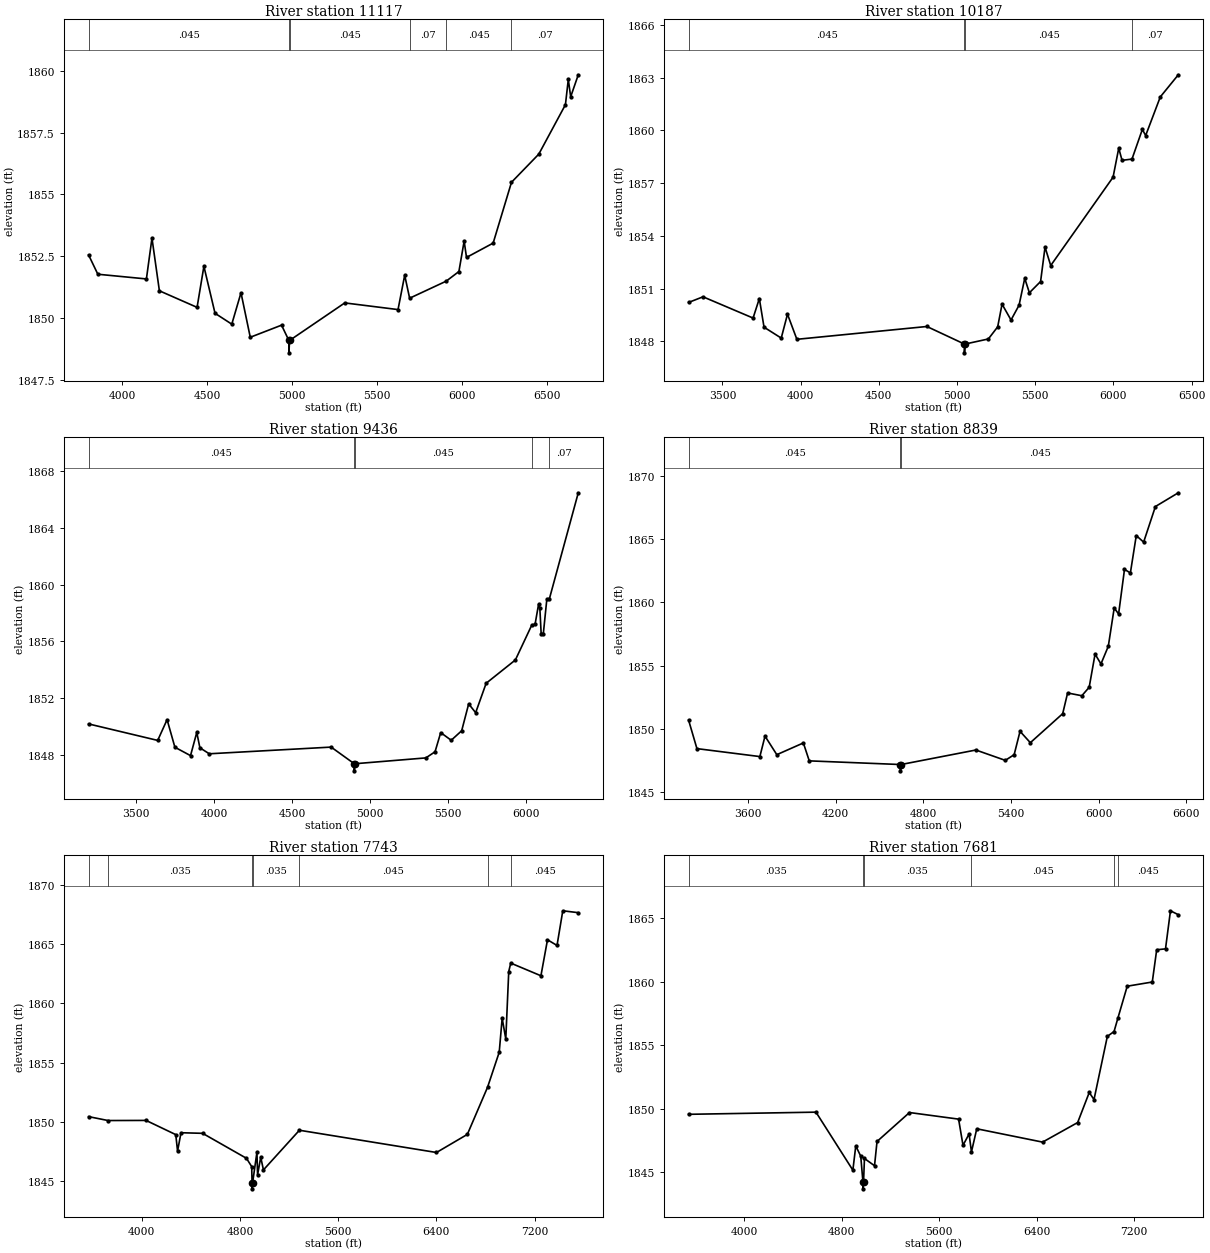
Type RM Length L Ch R = 1,11117,930,930,930
BEGIN DESCRIPTION:
Plum Creek Trib15 10.0
END DESCRIPTION:
XS GIS Cut Line= 3
      1419426.99      6957039.70      1419905.00      6955938.00
      1419154.99      6954437.99
#Sta/Elev= 30
  3803.7 1852.55  3858.1 1851.77  4143.5 1851.58  4176.2 1853.23  4219.8 1851.10
  4441.3 1850.43  4481.4 1852.09  4546.8 1850.19  4645.3 1849.75  4699.4 1851.02
  4753.9 1849.22  4937.8 1849.71  4980.8 1849.09  4981.1 1848.59  4984.8 1849.09
  5309.3 1850.61  5622.3 1850.34  5661.5 1851.73  5690.5 1850.80  5905.5 1851.49
  5980.1 1851.88  6010.9 1853.11  6024.8 1852.45  6181.4 1853.03  6289.1 1855.49
  6449.7 1856.63  6606.2 1858.63  6623.0 1859.65  6637.0 1858.95  6681.7 1859.84
#Mann=6,-1,0
  3803.7   0.045       0  4980.8   0.045       0  4984.8   0.045       0
  5690.5    0.07       0  5905.5   0.045       0  6289.1    0.07       0
Bank Sta=4980.8,4984.8
Exp/Cntr=0.3,0.1

Type RM Length L Ch R = 1,10187,751,751,751
BEGIN DESCRIPTION:
Mapping XS 23c2819c
END DESCRIPTION:
XS GIS Cut Line= 4
      1420588.01      6956900.12      1420580.48      6955732.12
      1420218.77      6955279.98      1419465.22      6954119.52
#Sta/Elev= 30
  3284.1 1850.21  3376.2 1850.53  3696.2 1849.32  3736.2 1850.43  3766.2 1848.80
  3876.2 1848.18  3916.2 1849.54  3976.2 1848.11  4807.3 1848.84  5047.3 1847.84
  5047.5 1847.34  5051.4 1847.84  5200.4 1848.13  5260.0 1848.82  5287.9 1850.11
  5345.3 1849.21  5396.6 1850.05  5432.9 1851.58  5462.7 1850.76  5534.3 1851.40
  5562.7 1853.36  5599.0 1852.31  5997.7 1857.34  6033.9 1858.99  6055.1 1858.30
  6118.6 1858.37  6184.9 1860.06  6206.0 1859.71  6299.6 1861.91  6414.8 1863.17
#Mann=4,-1,0
  3284.1   0.045       0  5047.3   0.045       0  5051.4   0.045       0
  6118.6    0.07       0
Bank Sta=5047.3,5051.4
Exp/Cntr=0.3,0.1

Type RM Length L Ch R = 1,9436,597,597,597
BEGIN DESCRIPTION:
Plum Creek Trib15 9.0
END DESCRIPTION:
XS GIS Cut Line= 3
      1420829.15      6956930.30      1420855.00      6955138.00
      1420255.01      6953938.02
#Sta/Elev= 30
  3197.7 1850.20  3640.0 1849.04  3700.1 1850.50  3750.1 1848.56  3850.1 1847.97
  3890.1 1849.60  3910.1 1848.52  3970.1 1848.10  4750.2 1848.57  4898.1 1847.40
  4898.4 1846.90  4902.3 1847.40  5356.3 1847.81  5415.0 1848.24  5451.4 1849.59
  5518.5 1849.05  5585.5 1849.72  5630.3 1851.61  5675.0 1850.99  5742.1 1853.06
  5929.3 1854.70  6034.9 1857.17  6055.1 1857.20  6077.5 1858.61  6085.9 1858.32
  6094.2 1856.55  6108.2 1856.56  6130.6 1858.98  6145.8 1858.96  6331.8 1866.46
#Mann=5,-1,0
  3197.7   0.045       0  4898.1   0.045       0  4902.3   0.045       0
  6034.9   0.035       0  6145.8    0.07       0
Bank Sta=4898.1,4902.3
Exp/Cntr=0.3,0.1

Type RM Length L Ch R = 1,8839,1096,1096,1096
BEGIN DESCRIPTION:
Plum Creek Trib15 8.0
END DESCRIPTION:
XS GIS Cut Line= 3
      1421071.52      6956795.81      1421325.04      6955007.19
      1421138.21      6953472.22
#Sta/Elev= 30
  3193.5 1850.67  3250.4 1848.42  3681.3 1847.79  3716.5 1849.41  3797.3 1847.94
  3979.1 1848.87  4019.5 1847.45  4643.6 1847.16  4643.9 1846.66  4647.8 1847.16
  5160.4 1848.31  5361.8 1847.49  5422.3 1847.94  5462.6 1849.79  5533.1 1848.89
  5754.7 1851.19  5788.3 1852.83  5885.7 1852.61  5936.0 1853.28  5976.3 1855.91
  6016.6 1855.13  6067.0 1856.53  6107.3 1859.56  6137.5 1859.09  6177.8 1862.62
  6218.1 1862.34  6258.4 1865.30  6308.8 1864.78  6389.4 1867.60  6546.3 1868.69
#Mann=3,-1,0
  3193.5   0.045       0  4643.6   0.045       0  4647.8   0.045       0
Bank Sta=4643.6,4647.8
Exp/Cntr=0.3,0.1

Type RM Length L Ch R = 1,7743,62,62,62
BEGIN DESCRIPTION:
Mapping XS 68d03f32
END DESCRIPTION:
XS GIS Cut Line= 5
      1421523.78      6957068.35      1421623.60      6956851.35
      1421892.70      6955688.16      1422040.27      6954963.33
      1421355.25      6953281.13
#Sta/Elev= 30
  3567.5 1850.44  3726.3 1850.11  4035.6 1850.12  4277.6 1848.92  4292.2 1847.53
  4320.3 1849.08  4496.3 1849.03  4853.4 1846.92  4896.1 1846.22  4899.1 1844.84
  4899.4 1844.34  4903.4 1844.84  4938.8 1847.44  4944.0 1845.52  4969.6 1847.01
  4991.8 1845.94  5284.7 1849.29  6401.3 1847.41  6652.7 1848.94  6817.2 1852.92
  6912.3 1855.88  6936.3 1858.75  6965.8 1857.00  6989.9 1862.70  7006.2 1863.41
  7252.0 1862.34  7305.5 1865.38  7383.1 1864.90  7430.1 1867.83  7556.3 1867.67
#Mann=7,-1,0
  3567.5   0.045       0  3726.3   0.035       0  4899.1   0.035       0
  4903.4   0.035       0  5284.7   0.045       0  6817.2    0.07       0
  7006.2   0.045       0
Bank Sta=4899.1,4903.4
Exp/Cntr=0.3,0.1

Type RM Length L Ch R = 1,7681,681,681,681
BEGIN DESCRIPTION:
Plum Creek Trib15 7.0
END DESCRIPTION:
XS GIS Cut Line= 4
      1421646.17      6957151.72      1421941.81      6955724.41
      1422125.34      6955000.66      1421519.72      6953288.79
#Sta/Elev= 30
  3542.4 1849.57  4587.8 1849.74  4890.8 1845.17  4914.6 1847.08  4955.5 1846.27
  4973.8 1844.20  4974.1 1843.70  4978.1 1844.20  4986.0 1846.09  5068.5 1845.52
  5089.1 1847.43  5355.5 1849.71  5758.7 1849.19  5794.9 1847.13  5844.9 1848.02
  5864.3 1846.61  5907.9 1848.43  6448.3 1847.38  6736.0 1848.92  6831.4 1851.29
  6870.3 1850.73  6979.9 1855.71  7034.9 1856.09  7066.0 1857.13  7143.1 1859.66
  7348.8 1859.99  7385.0 1862.53  7457.3 1862.60  7498.0 1865.60  7562.5 1865.29
#Mann=6,-1,0
  3542.4   0.035       0  4973.8   0.035       0  4978.1   0.035       0
  5864.3   0.045       0  7034.9    0.07       0  7066.0   0.045       0
Bank Sta=4973.8,4978.1
Exp/Cntr=0.3,0.1

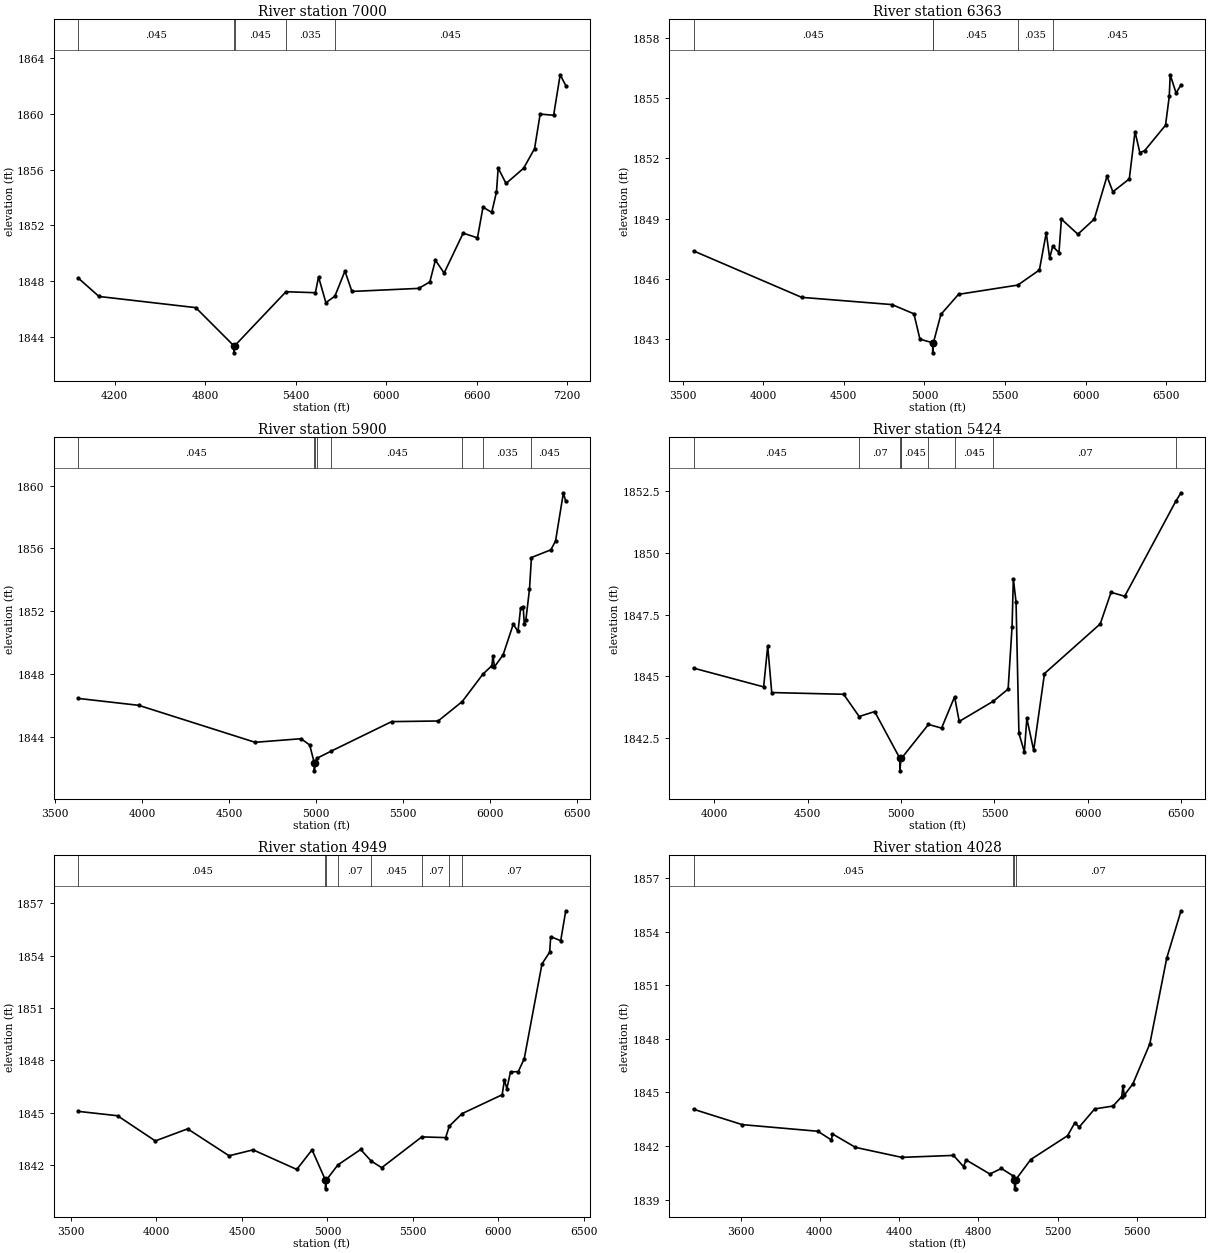
Type RM Length L Ch R = 1,7000,637,637,637
BEGIN DESCRIPTION:
Mapping XS 90117979
END DESCRIPTION:
XS GIS Cut Line= 5
      1422605.27      6956335.43      1422547.26      6955536.19
      1422377.41      6955353.27      1422187.84      6954953.79
      1421635.80      6953302.88
#Sta/Elev= 30
  3957.6 1848.23  4095.4 1846.91  4737.1 1846.11  4990.4 1843.37  4990.8 1842.87
  4994.9 1843.37  5335.7 1847.25  5530.7 1847.18  5551.7 1848.31  5600.4 1846.47
  5660.1 1846.93  5726.7 1848.73  5773.2 1847.27  6216.0 1847.49  6289.8 1847.95
  6326.8 1849.51  6384.7 1848.59  6511.0 1851.45  6605.8 1851.11  6642.6 1853.31
  6700.5 1852.94  6732.1 1854.40  6743.2 1856.12  6795.3 1855.01  6912.0 1856.10
  6984.8 1857.51  7021.6 1859.98  7111.1 1859.90  7154.5 1862.80  7191.5 1862.03
#Mann=5,-1,0
  3957.6   0.045       0  4990.4   0.045       0  4994.9   0.045       0
  5335.7   0.035       0  5660.1   0.045       0
Bank Sta=4990.4,4994.9
Exp/Cntr=0.3,0.1

Type RM Length L Ch R = 1,6363,463,463,463
BEGIN DESCRIPTION:
Plum Creek Trib15 6.0
END DESCRIPTION:
XS GIS Cut Line= 3
      1423321.93      6956123.94      1422705.00      6954838.00
      1421853.97      6953486.49
#Sta/Elev= 30
  3567.8 1847.40  4238.5 1845.09  4798.8 1844.73  4934.7 1844.27  4971.9 1843.01
  5050.9 1842.83  5051.2 1842.33  5055.4 1842.83  5101.8 1844.24  5211.3 1845.24
  5578.9 1845.70  5712.8 1846.45  5755.2 1848.30  5776.4 1847.04  5795.4 1847.63
  5834.1 1847.31  5849.4 1848.98  5951.3 1848.23  6053.1 1848.98  6132.0 1851.11
  6168.5 1850.34  6270.3 1850.98  6305.8 1853.33  6335.6 1852.29  6364.9 1852.38
  6494.9 1853.65  6518.1 1855.08  6524.0 1856.16  6560.5 1855.25  6591.2 1855.66
#Mann=5,-1,0
  3567.8   0.045       0  5050.9   0.045       0  5055.4   0.045       0
  5578.9   0.035       0  5795.4   0.045       0
Bank Sta=5050.9,5055.4
Exp/Cntr=0.3,0.1

Type RM Length L Ch R = 1,5900,476,476,476
BEGIN DESCRIPTION:
Plum Creek Trib15 5.0
END DESCRIPTION:
XS GIS Cut Line= 3
      1423459.06      6955890.35      1423055.00      6954588.00
      1422255.00      6953388.01
#Sta/Elev= 30
  3632.1 1846.43  3980.1 1845.99  4650.2 1843.63  4914.2 1843.86  4964.3 1843.46
  4990.7 1842.31  4991.0 1841.81  4995.5 1842.31  5005.6 1842.61  5088.4 1843.07
  5435.9 1844.95  5703.3 1844.99  5842.2 1846.23  5961.2 1847.98  6012.8 1848.52
  6018.8 1849.14  6027.8 1848.45  6077.4 1849.21  6135.9 1851.17  6163.0 1850.70
  6178.0 1852.18  6193.0 1852.29  6199.0 1851.21  6208.1 1851.41  6229.1 1853.38
  6240.5 1855.42  6352.3 1855.91  6379.3 1856.48  6424.4 1859.55  6437.9 1859.00
#Mann=8,-1,0
  3632.1   0.045       0  4990.7   0.045       0  4995.5   0.045       0
  5005.6    0.07       0  5088.4   0.045       0  5842.2    0.07       0
  5961.2   0.035       0  6240.5   0.045       0
Bank Sta=4990.7,4995.5
Exp/Cntr=0.3,0.1

Type RM Length L Ch R = 1,5424,475,475,475
BEGIN DESCRIPTION:
Plum Creek Trib15 4.0
END DESCRIPTION:
XS GIS Cut Line= 3
      1423873.53      6955415.63      1423455.00      6954388.00
      1422660.28      6953117.24
#Sta/Elev= 30
  3889.9 1845.33  4265.1 1844.57  4286.9 1846.23  4308.4 1844.34  4693.2 1844.27
  4776.0 1843.37  4859.1 1843.57  4994.3 1841.67  4994.6 1841.17  4999.3 1841.67
  5001.8 1841.67  5146.9 1843.05  5217.0 1842.90  5286.8 1844.17  5311.4 1843.17
  5494.0 1843.99  5573.1 1844.48  5594.3 1847.01  5601.0 1848.95  5615.6 1848.00
  5630.9 1842.69  5660.0 1841.94  5673.3 1843.29  5709.9 1842.00  5767.7 1845.11
  6066.0 1847.12  6123.8 1848.40  6196.9 1848.24  6470.4 1852.09  6498.3 1852.43
#Mann=9,-1,0
  3889.9   0.045       0  4776.0    0.07       0  4994.3    0.07       0
  4999.3    0.07       0  5001.8   0.045       0  5146.9    0.07       0
  5286.8   0.045       0  5494.0    0.07       0  6470.4   0.035       0
Bank Sta=4994.3,4999.3
Exp/Cntr=0.3,0.1

Type RM Length L Ch R = 1,4949,921,921,921
BEGIN DESCRIPTION:
Plum Creek Trib15 3.0
END DESCRIPTION:
XS GIS Cut Line= 3
      1424574.32      6955460.81      1423855.00      6954188.00
      1423154.98      6952987.96
#Sta/Elev= 30
  3542.6 1845.09  3772.4 1844.84  3993.3 1843.40  4182.4 1844.09  4424.9 1842.55
  4565.0 1842.89  4820.8 1841.77  4910.1 1842.89  4988.4 1841.16  4988.8 1840.66
  4993.4 1841.16  5061.3 1842.03  5194.4 1842.91  5255.9 1842.25  5317.6 1841.87
  5552.0 1843.63  5691.4 1843.59  5713.1 1844.25  5787.4 1844.96  6022.1 1846.04
  6035.0 1846.88  6049.4 1846.39  6070.9 1847.35  6116.0 1847.36  6151.1 1848.10
  6254.9 1853.52  6300.0 1854.20  6305.8 1855.08  6364.5 1854.85  6393.9 1856.56
#Mann=8,-1,0
  3542.6   0.045       0  4988.4   0.045       0  4993.4   0.045       0
  5061.3    0.07       0  5255.9   0.045       0  5552.0    0.07       0
  5713.1   0.045       0  5787.4    0.07       0
Bank Sta=4988.4,4993.4
Exp/Cntr=0.3,0.1

Type RM Length L Ch R = 1,4028,801,801,801
BEGIN DESCRIPTION:
Plum Creek Trib15 2.0
END DESCRIPTION:
XS GIS Cut Line= 3
      1424807.94      6955053.94      1424295.32      6953498.75
      1423805.00      6952838.00
#Sta/Elev= 30
  3362.5 1844.06  3608.6 1843.20  3989.8 1842.83  4058.6 1842.34  4063.8 1842.68
  4179.5 1841.93  4413.2 1841.37  4674.4 1841.48  4725.6 1840.85  4737.6 1841.23
  4858.0 1840.44  4916.2 1840.75  4977.0 1840.32  4982.2 1840.11  4982.7 1839.61
  4987.4 1839.61  4987.8 1840.11  5064.3 1841.25  5250.0 1842.58  5287.3 1843.31
  5308.5 1843.06  5387.0 1844.08  5479.6 1844.24  5523.4 1844.77  5529.7 1845.36
  5536.4 1844.85  5579.7 1845.48  5665.3 1847.72  5750.8 1852.52  5822.8 1855.16
#Mann=4,-1,0
  3362.5   0.045       0  4977.0    0.07       0  4982.2    0.07       0
  4987.8    0.07       0
Bank Sta=4982.2,4987.8
Exp/Cntr=0.3,0.1

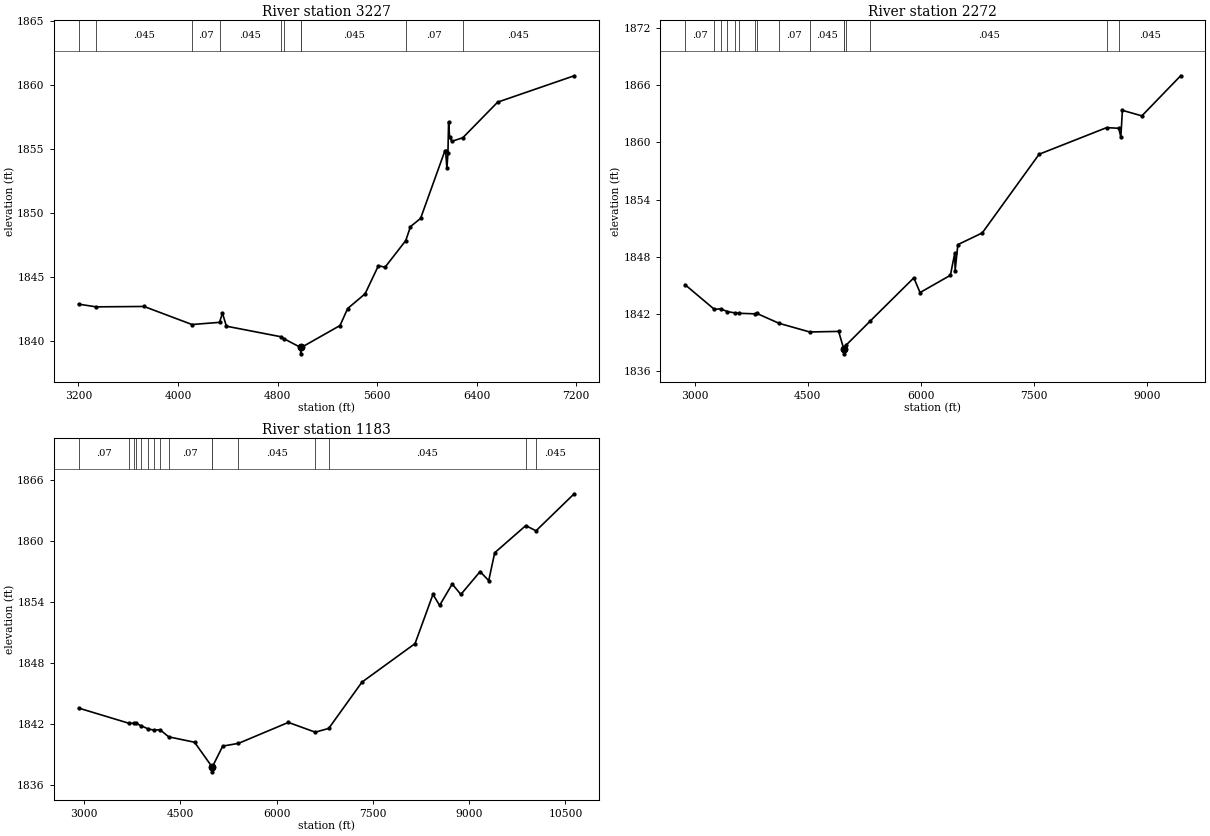
Type RM Length L Ch R = 1,3227,955,955,955
BEGIN DESCRIPTION:
Mapping XS 947a37f9
END DESCRIPTION:
XS GIS Cut Line= 4
      1425486.14      6954948.43      1424943.58      6953260.45
      1424665.56      6952700.50      1423168.73      6952181.67
#Sta/Elev= 30
  3201.5 1842.90  3342.5 1842.69  3727.1 1842.72  4112.8 1841.31  4333.7 1841.48
  4357.4 1842.20  4388.9 1841.18  4824.5 1840.36  4851.7 1840.20  4985.5 1839.52
  4986.0 1839.02  4991.3 1839.52  5302.0 1841.23  5363.7 1842.56  5503.7 1843.71
  5610.9 1845.91  5663.8 1845.78  5830.5 1847.87  5868.5 1848.96  5949.6 1849.60
  6143.5 1854.84  6150.6 1854.85  6161.2 1853.51  6169.4 1854.71  6174.7 1857.14
  6182.4 1855.98  6200.5 1855.62  6289.0 1855.90  6568.9 1858.68  7183.9 1860.74
#Mann=10,-1,0
  3201.5    0.07       0  3342.5   0.045       0  4112.8    0.07       0
  4333.7   0.045       0  4824.5    0.07       0  4851.7   0.045       0
  4985.5   0.045       0  4991.3   0.045       0  5830.5    0.07       0
  6289.0   0.045       0
Bank Sta=4985.5,4991.3
Exp/Cntr=0.3,0.1

Type RM Length L Ch R = 1,2272,1089,1089,1089
BEGIN DESCRIPTION:
Mapping XS 1ab3925c
END DESCRIPTION:
XS GIS Cut Line= 4
      1425510.98      6955187.95      1425836.49      6953117.67
      1425875.55      6952648.92      1421996.60      6951672.68
#Sta/Elev= 30
  2874.8 1845.09  3261.3 1842.52  3345.9 1842.56  3435.1 1842.28  3533.2 1842.14
  3588.9 1842.10  3797.2 1842.04  3823.2 1842.09  4119.2 1841.05  4526.2 1840.14
  4909.4 1840.20  4977.2 1838.35  4977.7 1837.85  4983.2 1838.35  5005.2 1838.74
  5329.4 1841.30  5905.5 1845.81  5988.0 1844.27  6390.1 1846.08  6447.7 1848.39
  6452.8 1846.58  6488.8 1849.29  6812.5 1850.52  7565.7 1858.76  8460.7 1861.55
  8620.8 1861.48  8648.4 1860.56  8669.1 1863.36  8926.9 1862.78  9440.8 1866.98
#Mann=16,-1,0
  2874.8    0.07       0  3261.3   0.045       0  3345.9    0.07       0
  3435.1   0.045       0  3533.2    0.07       0  3588.9   0.045       0
  3797.2    0.07       0  3823.2   0.045       0  4119.2    0.07       0
  4526.2   0.045       0  4977.2   0.045       0  4983.2   0.045       0
  5005.2    0.07       0  5329.4   0.045       0  8460.7   0.035       0
  8620.8   0.045       0
Bank Sta=4977.2,4983.2
Exp/Cntr=0.3,0.1

Type RM Length L Ch R = 1,1183,0,0,0
BEGIN DESCRIPTION:
Mapping XS ad81e290
END DESCRIPTION:
XS GIS Cut Line= 6
      1425613.45      6955109.32      1425910.42      6954036.02
      1426103.13      6953916.22      1426567.47      6953945.67
      1426773.99      6952727.05      1422257.42      6951542.59
#Sta/Elev= 30
  2916.8 1843.55  3702.9 1842.05  3784.0 1842.06  3806.1 1842.06  3894.6 1841.80
  4003.9 1841.49  4087.9 1841.39  4186.6 1841.41  4320.1 1840.72  4722.8 1840.19
  4993.8 1837.78  4994.3 1837.28  5000.9 1837.78  5161.1 1839.81  5407.0 1840.08
  6183.9 1842.14  6602.8 1841.18  6812.6 1841.55  7330.3 1846.10  8157.3 1849.89
  8436.5 1854.73  8539.9 1853.64  8736.3 1855.75  8870.7 1854.72  9170.5 1856.97
  9304.9 1856.08  9397.9 1858.82  9882.0 1861.49 10041.6 1860.98 10636.0 1864.62
#Mann=16,-1,0
  2916.8    0.07       0  3702.9   0.045       0  3784.0    0.07       0
  3806.1   0.045       0  3894.6    0.07       0  4003.9   0.045       0
  4087.9    0.07       0  4186.6   0.045       0  4320.1    0.07       0
  4993.8    0.07       0  5000.9    0.07       0  5407.0   0.045       0
  6602.8    0.07       0  6812.6   0.045       0  9882.0   0.035       0
 10041.6   0.045       0
Bank Sta=4993.8,5000.9
Exp/Cntr=0.3,0.1

Chan Stop Cuts=-1