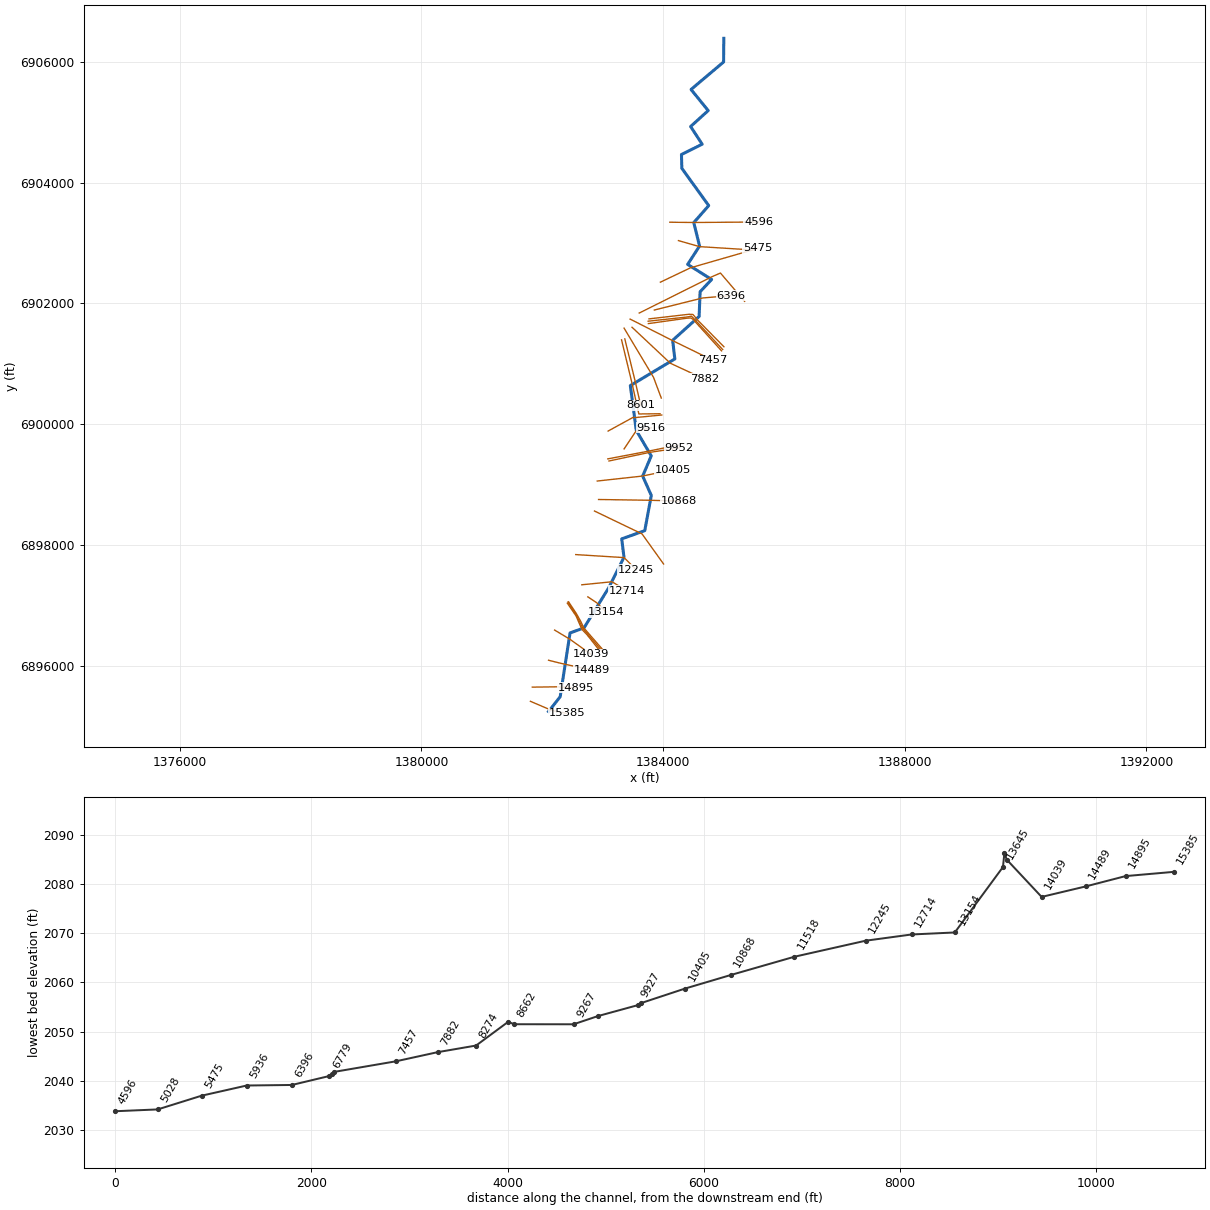
--- Plum Creek Trib2.prj (project) ---

Proj Title=Plum Creek Trib2 Base Level Engineering
Current Plan=p01
Default Exp/Contr=0.3,0.1
English Units
Geom File=g01
Flow File=f01
Plan File=p01
BEGIN DESCRIPTION:
Plum Creek Trib2
END DESCRIPTION:

--- Plum Creek Trib2.p01 (plan) ---

Plan Title=Multiple Run
Short Identifier=Multiple
Geom File=g01
Flow File=f01
Subcritical Flow
K Sum by GR= 0
Std Step Tol= 0.01
Critical Tol= 0.01
Num of Std Step Trials= 20
Max Error Tol= 0.3
Flow Tol Ratio= 0.001
Split Flow NTrial= 30
Split Flow Tol= 0.02
Split Flow Ratio= 0.02
Log Output Level= 0
Friction Slope Method= 1
Unsteady Friction Slope Method= 2
Unsteady Bridges Friction Slope Method= 1
Parabolic Critical Depth
Global Vel Dist=  1 , 1 , 1
Global Log Level= 0
CheckData=True
Encroach Param= -1, 0, 0, 0
BEGIN DESCRIPTION:
Multiple Run
END DESCRIPTION:

--- Plum Creek Trib2.f01 (steady flow) ---

Flow Title=Multiple
Number of Profiles=7
Profile Names=10-year,25-year,50-year,1pct_min,100-year,1pct_plu,500-year
River Rch & RM= Plum Creek Trib2,Reach-1,15385
     243     344     428     266     531    1059     824
River Rch & RM= Plum Creek Trib2,Reach-1,14895
     409     593     750     472     943    1881    1506
River Rch & RM= Plum Creek Trib2,Reach-1,13645
     413     598     757     476     949    1894    1514
River Rch & RM= Plum Creek Trib2,Reach-1,11518
     528     773     985     623    1244    2482    2010
River Rch & RM= Plum Creek Trib2,Reach-1,8662
     650     958    1228     780    1557    3106    2537
River Rch & RM= Plum Creek Trib2,Reach-1,4128
     683    1008    1292     821    1639    3270    2672
Boundary for River Rch & Prof#=Plum Creek Trib2,Reach-1,1
Up Type=0
Dn Type=3
Dn Slope=0.005
Boundary for River Rch & Prof#=Plum Creek Trib2,Reach-1,2
Up Type=0
Dn Type=3
Dn Slope=0.005
Boundary for River Rch & Prof#=Plum Creek Trib2,Reach-1,3
Up Type=0
Dn Type=3
Dn Slope=0.005
Boundary for River Rch & Prof#=Plum Creek Trib2,Reach-1,4
Up Type=0
Dn Type=3
Dn Slope=0.005
Boundary for River Rch & Prof#=Plum Creek Trib2,Reach-1,5
Up Type=0
Dn Type=3
Dn Slope=0.005
Boundary for River Rch & Prof#=Plum Creek Trib2,Reach-1,6
Up Type=0
Dn Type=3
Dn Slope=0.005
Boundary for River Rch & Prof#=Plum Creek Trib2,Reach-1,7
Up Type=0
Dn Type=3
Dn Slope=0.005

--- Plum Creek Trib2.g01 (geometry) ---

Geom Title=Existing Conditions

River Reach=Plum Creek Trib2,Reach-1
Reach XY= 30
      1382105.00      6895238.00      1382297.39      6895484.67
      1382460.52      6896540.46      1382691.74      6896624.21
      1383099.17      6897285.70      1383353.03      6897793.90
      1383315.59      6898098.05      1383697.21      6898234.57
      1383805.30      6898817.82      1383662.32      6899138.10
      1383804.50      6899472.78      1383556.66      6899894.05
      1383458.45      6900636.75      1384194.82      6901078.29
      1384158.53      6901386.56      1384596.86      6901781.91
      1384613.04      6902191.32      1384803.51      6902393.91
      1384407.14      6902643.97      1384603.95      6902948.43
      1384508.12      6903336.37      1384755.48      6903617.84
      1384310.34      6904235.26      1384304.59      6904463.44
      1384647.42      6904634.68      1384456.04      6904927.57
      1384747.02      6905191.33      1384462.98      6905541.33
      1385001.83      6905996.34      1385005.00      6906388.00

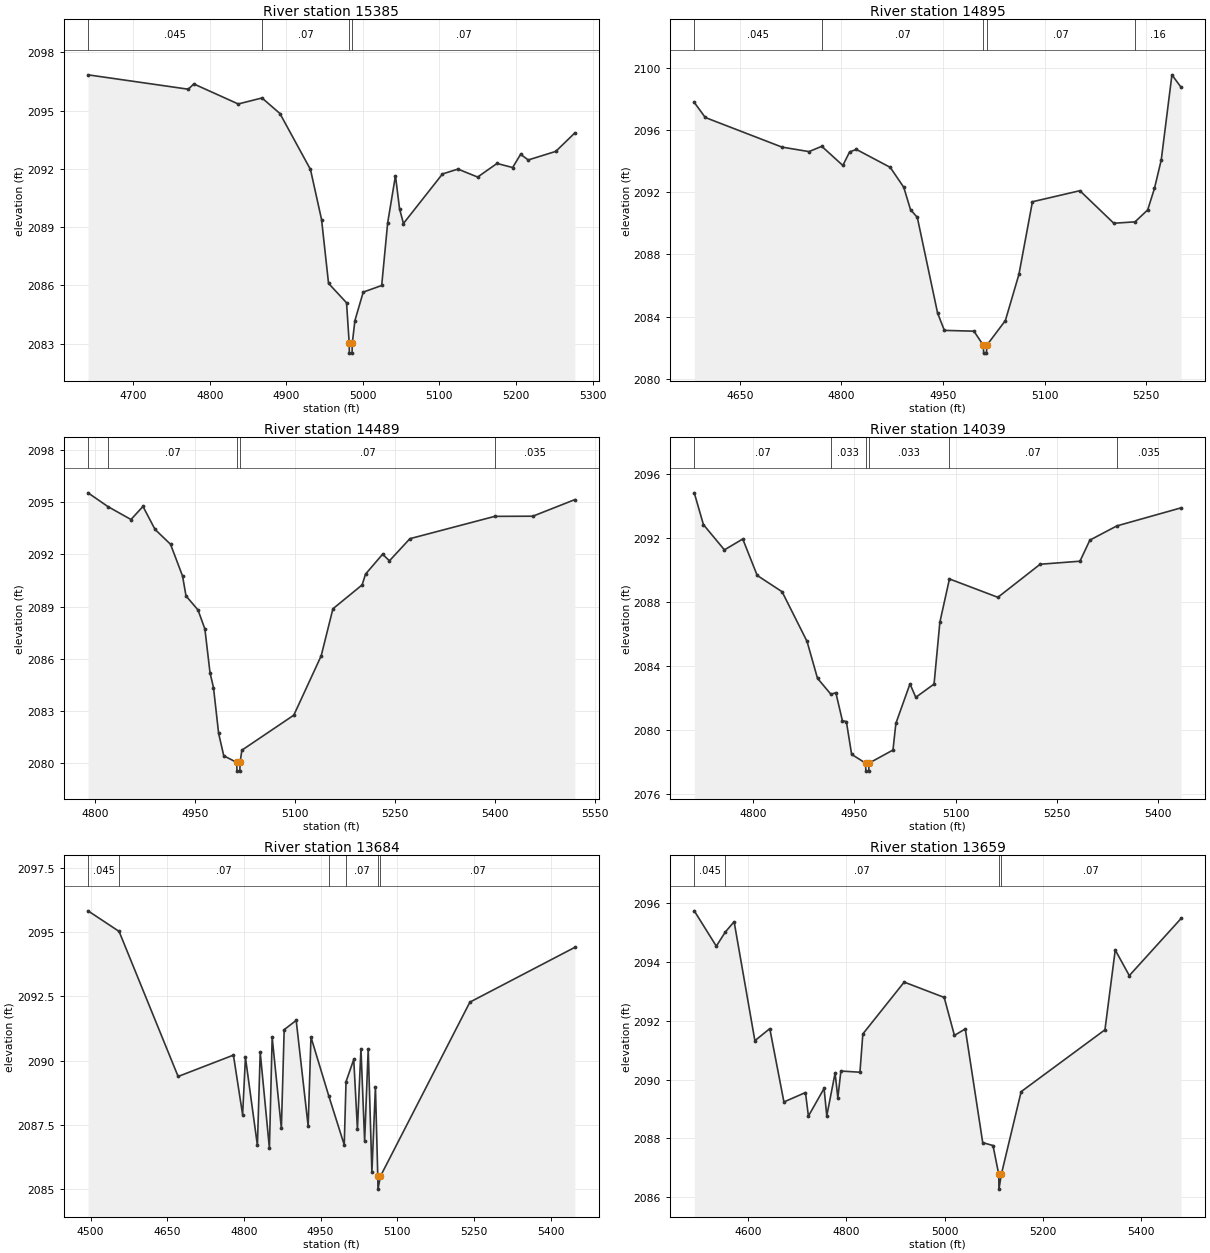
Type RM Length L Ch R = 1,15385,490,490,490
BEGIN DESCRIPTION:
Plum Creek Trib2 27.0
END DESCRIPTION:
XS GIS Cut Line= 3
      1381804.65      6895408.14      1382154.65      6895258.14
      1382404.61      6895208.15
#Sta/Elev= 30
  4641.1 2096.84  4772.0 2096.10  4779.3 2096.37  4837.3 2095.34  4868.3 2095.65
  4891.7 2094.85  4931.6 2091.97  4946.1 2089.39  4955.2 2086.11  4978.7 2085.11
  4982.2 2083.02  4982.4 2082.52  4985.9 2082.52  4986.2 2083.02  4989.6 2084.19
  5000.5 2085.66  5024.6 2086.00  5032.4 2089.22  5042.6 2091.65  5047.9 2089.95
  5053.0 2089.19  5104.0 2091.74  5124.2 2091.99  5149.9 2091.58  5175.2 2092.28
  5195.6 2092.07  5206.0 2092.75  5216.0 2092.46  5251.9 2092.90  5276.8 2093.85
#Mann=4,-1,0
  4641.1   0.045       0  4868.3    0.07       0  4982.2    0.07       0
  4986.2    0.07       0
Bank Sta=4982.2,4986.2
Exp/Cntr=0.3,0.1

Type RM Length L Ch R = 1,14895,406,406,406
BEGIN DESCRIPTION:
Mapping XS de3d0204
END DESCRIPTION:
XS GIS Cut Line= 3
      1381835.50      6895642.77      1382248.68      6895647.98
      1382554.27      6895632.35
#Sta/Elev= 30
  4582.5 2097.76  4598.8 2096.79  4712.0 2094.89  4752.0 2094.60  4770.9 2094.94
  4802.0 2093.71  4812.0 2094.58  4822.0 2094.74  4872.0 2093.59  4892.0 2092.31
  4902.0 2090.87  4912.0 2090.38  4942.0 2084.23  4952.0 2083.12  4995.7 2083.07
  5009.6 2082.16  5010.0 2081.66  5014.2 2081.66  5014.6 2082.16  5042.1 2083.75
  5062.1 2086.71  5082.1 2091.38  5152.2 2092.09  5202.3 2090.00  5233.7 2090.09
  5252.4 2090.86  5262.4 2092.24  5272.4 2094.06  5288.2 2099.53  5301.7 2098.73
#Mann=5,-1,0
  4582.5   0.045       0  4770.9    0.07       0  5009.6    0.07       0
  5014.6    0.07       0  5233.7    0.16       0
Bank Sta=5009.6,5014.6
Exp/Cntr=0.3,0.1

Type RM Length L Ch R = 1,14489,450,450,450
BEGIN DESCRIPTION:
Plum Creek Trib2 26.0
END DESCRIPTION:
XS GIS Cut Line= 3
      1382105.03      6896087.99      1382305.00      6896038.00
      1382816.40      6895925.75
#Sta/Elev= 30
  4789.7 2095.52  4819.6 2094.73  4854.1 2093.99  4872.1 2094.74  4890.2 2093.42
  4913.4 2092.57  4931.4 2090.75  4936.6 2089.61  4954.6 2088.80  4964.9 2087.71
  4972.6 2085.20  4977.8 2084.35  4985.5 2081.72  4993.2 2080.44  5012.6 2080.06
  5013.0 2079.56  5017.3 2079.56  5017.7 2080.06  5020.3 2080.76  5098.2 2082.77
  5139.2 2086.17  5156.8 2088.87  5200.6 2090.24  5205.7 2090.86  5231.3 2092.00
  5241.5 2091.62  5272.2 2092.89  5399.3 2094.17  5456.5 2094.18  5519.4 2095.13
#Mann=5,-1,0
  4789.7   0.045       0  4819.6    0.07       0  5012.6    0.07       0
  5017.7    0.07       0  5399.3   0.035       0
Bank Sta=5012.6,5017.7
Exp/Cntr=0.3,0.1

Type RM Length L Ch R = 1,14039,355,355,355
BEGIN DESCRIPTION:
Plum Creek Trib2 25.0
END DESCRIPTION:
XS GIS Cut Line= 3
      1382204.99      6896588.01      1382455.00      6896438.00
      1382805.02      6896187.99
#Sta/Elev= 30
  4712.7 2094.84  4726.3 2092.85  4757.4 2091.27  4784.6 2091.95  4806.0 2089.67
  4842.9 2088.65  4879.9 2085.54  4895.4 2083.23  4915.3 2082.23  4922.6 2082.33
  4932.3 2080.58  4938.2 2080.52  4946.0 2078.47  4966.7 2077.92  4967.1 2077.42
  4971.4 2077.42  4971.8 2077.92  5007.3 2078.74  5011.6 2080.41  5032.5 2082.88
  5041.1 2082.04  5068.2 2082.87  5076.8 2086.74  5091.0 2089.45  5162.8 2088.30
  5225.5 2090.37  5284.5 2090.56  5299.2 2091.88  5339.2 2092.77  5434.4 2093.90
#Mann=6,-1,0
  4712.7    0.07       0  4915.3   0.033       0  4966.7   0.033       0
  4971.8   0.033       0  5091.0    0.07       0  5339.2   0.035       0
Bank Sta=4966.7,4971.8
Exp/Cntr=0.3,0.1

Type RM Length L Ch R = 1,13684,25,25,25
BEGIN DESCRIPTION:
Mapping XS 4678089b
END DESCRIPTION:
XS GIS Cut Line= 5
      1382415.35      6897033.39      1382559.44      6896823.33
      1382656.67      6896599.37      1382741.74      6896510.83
      1382947.29      6896251.73
#Sta/Elev= 30
  4495.1 2095.82  4555.9 2095.02  4671.4 2089.38  4779.6 2090.21  4797.6 2087.89
  4803.1 2090.12  4826.5 2086.70  4832.0 2090.32  4850.0 2086.59  4855.4 2090.90
  4873.4 2087.36  4878.9 2091.20  4902.4 2091.56  4925.8 2087.45  4931.3 2090.91
  4965.9 2088.64  4996.4 2086.72  4999.9 2089.18  5015.0 2090.04  5022.2 2087.33
  5029.1 2090.46  5036.3 2086.86  5043.3 2090.46  5050.5 2085.66  5057.4 2088.98
  5062.0 2085.50  5062.4 2085.00  5067.2 2085.50  5242.2 2092.27  5447.5 2094.40
#Mann=6,-1,0
  4495.1   0.045       0  4555.9    0.07       0  4965.9   0.033       0
  4999.9    0.07       0  5062.0    0.07       0  5067.2    0.07       0
Bank Sta=5062,5067.2
Exp/Cntr=0.3,0.1

Type RM Length L Ch R = 1,13659,14,14,14
BEGIN DESCRIPTION:
Mapping XS 795d4e33
END DESCRIPTION:
XS GIS Cut Line= 5
      1382425.74      6897050.79      1382561.18      6896842.42
      1382667.08      6896627.15      1382710.49      6896571.59
      1382987.70      6896242.40
#Sta/Elev= 30
  4491.3 2095.73  4536.1 2094.53  4554.4 2095.01  4572.3 2095.36  4614.5 2091.32
  4644.8 2091.73  4673.5 2089.24  4717.3 2089.56  4723.3 2088.76  4755.1 2089.70
  4760.6 2088.77  4777.5 2090.22  4783.1 2089.38  4789.3 2090.29  4828.0 2090.25
  4833.9 2091.55  4917.9 2093.31  4999.2 2092.79  5020.0 2091.50  5042.1 2091.72
  5077.5 2087.86  5098.4 2087.76  5110.1 2086.78  5110.5 2086.28  5115.3 2086.78
  5155.6 2089.59  5325.9 2091.69  5346.8 2094.40  5375.4 2093.53  5480.6 2095.47
#Mann=4,-1,0
  4491.3   0.045       0  4554.4    0.07       0  5110.1    0.07       0
  5115.3    0.07       0
Bank Sta=5110.1,5115.3
Exp/Cntr=0.3,0.1

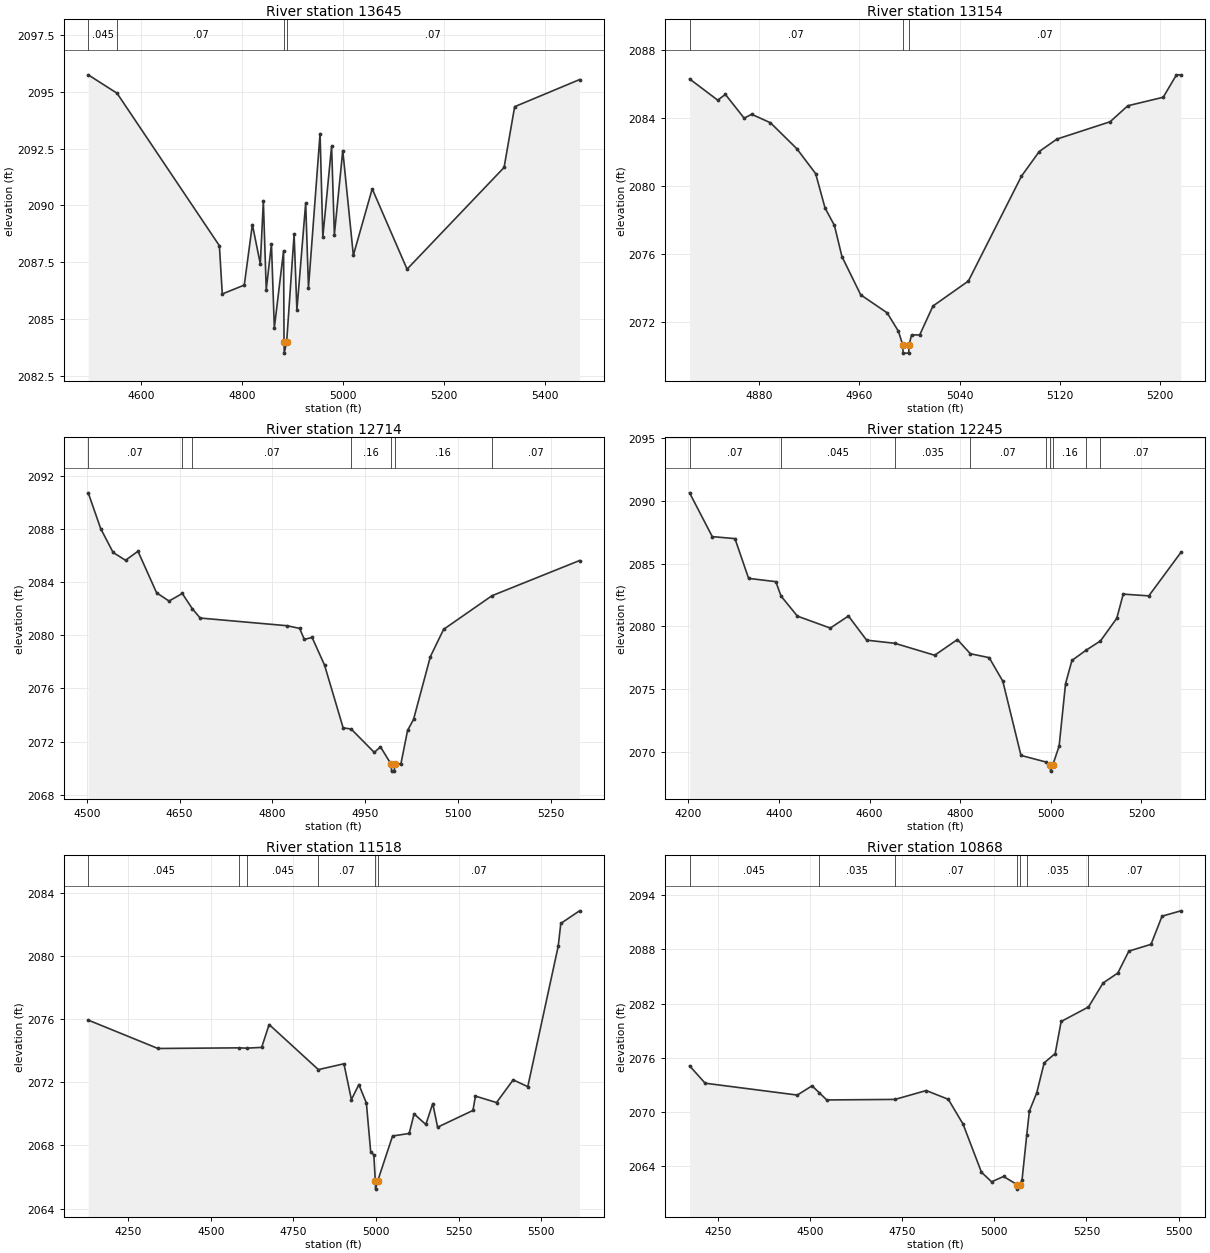
Type RM Length L Ch R = 1,13645,491,491,491
BEGIN DESCRIPTION:
Mapping XS 822e5754
END DESCRIPTION:
XS GIS Cut Line= 6
      1382436.17      6897055.99      1382569.86      6896852.84
      1382639.31      6896727.84      1382687.92      6896623.67
      1382727.85      6896578.53      1382996.96      6896269.49
#Sta/Elev= 30
  4496.3 2095.74  4553.3 2094.93  4755.6 2088.23  4761.3 2086.11  4804.8 2086.50
  4820.8 2089.16  4836.5 2087.43  4842.5 2090.19  4848.2 2086.30  4858.5 2088.30
  4864.2 2084.62  4882.5 2088.01  4883.4 2084.01  4883.8 2083.51  4888.6 2084.01
  4903.3 2088.73  4908.8 2085.40  4926.2 2090.11  4931.7 2086.38  4954.6 2093.16
  4960.1 2088.62  4977.4 2092.61  4982.9 2088.72  4999.5 2092.41  5020.4 2087.81
  5057.7 2090.73  5126.6 2087.20  5318.4 2091.67  5339.3 2094.34  5467.5 2095.53
#Mann=4,-1,0
  4496.3   0.045       0  4553.3    0.07       0  4883.4    0.07       0
  4888.6    0.07       0
Bank Sta=4883.4,4888.6
Exp/Cntr=0.3,0.1

Type RM Length L Ch R = 1,13154,440,440,440
BEGIN DESCRIPTION:
Plum Creek Trib2 23.0
END DESCRIPTION:
XS GIS Cut Line= 3
      1382754.99      6897138.01      1382905.00      6897038.00
      1383054.99      6896888.01
#Sta/Elev= 30
  4824.4 2086.31  4846.9 2085.06  4853.0 2085.40  4868.0 2084.00  4874.0 2084.23
  4889.0 2083.73  4910.0 2082.21  4925.1 2080.74  4932.6 2078.72  4940.1 2077.69
  4946.1 2075.86  4961.1 2073.61  4982.2 2072.55  4991.2 2071.47  4994.6 2070.68
  4995.0 2070.18  4999.4 2070.18  4999.8 2070.68  5001.7 2071.25  5008.2 2071.25
  5018.8 2072.95  5047.1 2074.42  5089.5 2080.59  5103.7 2082.04  5117.8 2082.77
  5160.3 2083.79  5174.4 2084.73  5202.7 2085.23  5213.3 2086.55  5216.8 2086.55
#Mann=3,-1,0
  4824.4    0.07       0  4994.6    0.07       0  4999.8    0.07       0
Bank Sta=4994.6,4999.8
Exp/Cntr=0.3,0.1

Type RM Length L Ch R = 1,12714,469,469,469
BEGIN DESCRIPTION:
Plum Creek Trib2 22.0
END DESCRIPTION:
XS GIS Cut Line= 3
      1382655.01      6897338.00      1383155.00      6897388.00
      1383404.98      6897238.01
#Sta/Elev= 30
  4502.4 2090.73  4522.5 2088.04  4542.6 2086.24  4562.7 2085.65  4582.8 2086.33
  4612.9 2083.20  4633.0 2082.58  4654.4 2083.15  4670.5 2082.01  4683.3 2081.30
  4824.0 2080.72  4844.1 2080.52  4851.6 2079.69  4864.2 2079.84  4884.3 2077.76
  4914.4 2073.03  4927.4 2072.94  4964.7 2071.18  4974.7 2071.60  4992.2 2070.27
  4992.6 2069.77  4997.1 2069.77  4997.5 2070.27  5007.8 2070.33  5018.5 2072.83
  5028.2 2073.67  5055.4 2078.40  5076.8 2080.45  5154.9 2082.98  5296.4 2085.63
#Mann=7,-1,0
  4502.4    0.07       0  4654.4   0.045       0  4670.5    0.07       0
  4927.4    0.16       0  4992.2    0.07       0  4997.5    0.16       0
  5154.9    0.07       0
Bank Sta=4992.2,4997.5
Exp/Cntr=0.3,0.1

Type RM Length L Ch R = 1,12245,727,727,727
BEGIN DESCRIPTION:
Plum Creek Trib2 21.0
END DESCRIPTION:
XS GIS Cut Line= 3
      1382554.97      6897838.00      1383355.00      6897788.00
      1383554.97      6897588.03
#Sta/Elev= 30
  4202.5 2090.62  4252.6 2087.14  4302.7 2086.98  4332.8 2083.82  4392.9 2083.56
  4404.3 2082.42  4440.5 2080.82  4513.1 2079.87  4553.2 2080.83  4593.3 2078.91
  4655.7 2078.66  4743.6 2077.71  4793.7 2078.96  4822.3 2077.83  4863.8 2077.52
  4893.9 2075.65  4934.0 2069.75  4988.5 2069.23  4998.9 2069.00  4999.3 2068.50
  5004.3 2069.00  5018.2 2070.49  5032.4 2075.45  5046.5 2077.30  5078.1 2078.12
  5109.5 2078.85  5145.5 2080.65  5159.7 2082.57  5216.2 2082.43  5286.9 2085.88
#Mann=9,-1,0
  4202.5    0.07       0  4404.3   0.045       0  4655.7   0.035       0
  4822.3    0.07       0  4988.5    0.16       0  4998.9    0.07       0
  5004.3    0.16       0  5078.1    0.16       0  5109.5    0.07       0
Bank Sta=4998.9,5004.3
Exp/Cntr=0.3,0.1

Type RM Length L Ch R = 1,11518,650,650,650
BEGIN DESCRIPTION:
Mapping XS 0062b8a0
END DESCRIPTION:
XS GIS Cut Line= 3
      1382865.00      6898559.44      1383651.46      6898180.97
      1384008.38      6897681.97
#Sta/Elev= 30
  4129.2 2075.95  4340.1 2074.15  4586.1 2074.19  4608.5 2074.17  4653.9 2074.22
  4676.5 2075.67  4825.5 2072.81  4902.8 2073.18  4925.4 2070.91  4948.0 2071.86
  4970.7 2070.69  4983.7 2067.61  4993.3 2067.40  4997.8 2065.73  4998.3 2065.23
  5004.6 2065.73  5049.9 2068.60  5100.2 2068.76  5115.0 2070.00  5150.6 2069.33
  5171.5 2070.66  5186.2 2069.16  5293.1 2070.22  5300.7 2071.13  5364.4 2070.72
  5414.8 2072.16  5459.0 2071.73  5551.1 2080.64  5558.9 2082.08  5615.5 2082.88
#Mann=6,-1,0
  4129.2   0.045       0  4586.1   0.035       0  4608.5   0.045       0
  4825.5    0.07       0  4997.8    0.07       0  5004.6    0.07       0
Bank Sta=4997.8,5004.6
Exp/Cntr=0.3,0.1

Type RM Length L Ch R = 1,10868,463,463,463
BEGIN DESCRIPTION:
Plum Creek Trib2 20.0
END DESCRIPTION:
XS GIS Cut Line= 3
      1382932.68      6898750.41      1383755.00      6898738.00
      1384266.00      6898724.37
#Sta/Elev= 30
  4172.6 2075.12  4214.9 2073.20  4465.0 2071.89  4505.0 2072.91  4524.4 2072.16
  4545.0 2071.35  4730.2 2071.41  4815.0 2072.39  4875.0 2071.42  4915.0 2068.68
  4965.0 2063.36  4992.5 2062.31  5025.0 2062.90  5061.6 2062.00  5062.1 2061.50
  5068.4 2062.00  5075.0 2062.47  5087.8 2067.45  5095.1 2070.13  5115.1 2072.15
  5135.1 2075.44  5165.1 2076.48  5181.3 2080.02  5255.5 2081.62  5295.1 2084.27
  5335.1 2085.37  5365.1 2087.79  5425.2 2088.54  5455.2 2091.65  5506.2 2092.24
#Mann=7,-1,0
  4172.6   0.045       0  4524.4   0.035       0  4730.2    0.07       0
  5061.6    0.07       0  5068.4    0.07       0  5087.8   0.035       0
  5255.5    0.07       0
Bank Sta=5061.6,5068.4
Exp/Cntr=0.3,0.1

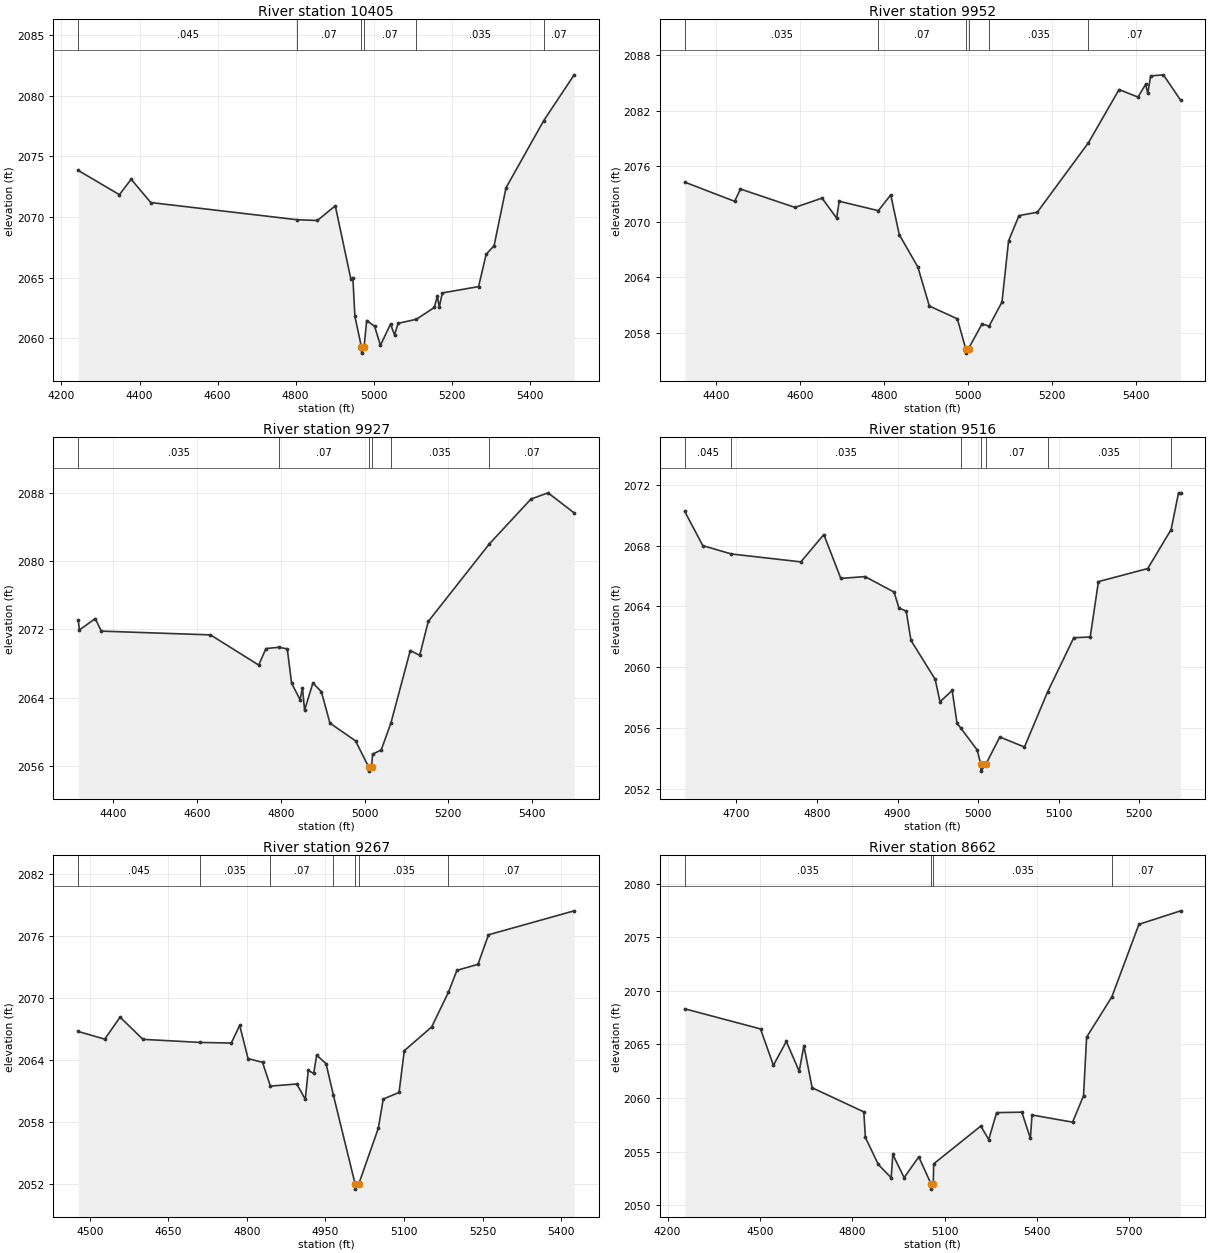
Type RM Length L Ch R = 1,10405,453,453,453
BEGIN DESCRIPTION:
Plum Creek Trib2 19.0
END DESCRIPTION:
XS GIS Cut Line= 3
      1382910.10      6899055.96      1383655.00      6899138.00
      1384165.97      6899243.24
#Sta/Elev= 30
  4242.9 2073.84  4348.4 2071.84  4378.6 2073.11  4428.9 2071.19  4803.9 2069.77
  4855.9 2069.71  4901.8 2070.92  4941.8 2064.86  4946.8 2065.00  4952.1 2061.80
  4968.8 2059.26  4969.3 2058.76  4975.6 2059.26  4982.2 2061.45  5002.5 2060.98
  5017.5 2059.41  5043.4 2061.16  5053.6 2060.26  5062.7 2061.22  5109.3 2061.55
  5155.7 2062.53  5163.3 2063.47  5168.4 2062.57  5176.1 2063.73  5269.0 2064.25
  5288.4 2066.91  5308.8 2067.63  5339.4 2072.41  5436.0 2077.95  5514.0 2081.73
#Mann=6,-1,0
  4242.9   0.045       0  4803.9    0.07       0  4968.8    0.07       0
  4975.6    0.07       0  5109.3   0.035       0  5436.0    0.07       0
Bank Sta=4968.8,4975.6
Exp/Cntr=0.3,0.1

Type RM Length L Ch R = 1,9952,25,25,25
BEGIN DESCRIPTION:
Plum Creek Trib2 18.0
END DESCRIPTION:
XS GIS Cut Line= 3
      1383105.04      6899388.01      1383765.90      6899528.37
      1384265.53      6899605.16
#Sta/Elev= 30
  4324.4 2074.28  4443.3 2072.20  4457.3 2073.53  4587.1 2071.54  4651.5 2072.55
  4686.3 2070.38  4692.4 2072.21  4785.6 2071.19  4815.1 2072.90  4835.5 2068.59
  4879.7 2065.09  4907.1 2060.87  4973.8 2059.48  4993.5 2056.27  4994.0 2055.77
  5000.5 2056.27  5032.5 2058.93  5049.3 2058.69  5080.0 2061.29  5095.8 2067.92
  5120.5 2070.65  5164.1 2071.02  5286.1 2078.55  5358.9 2084.30  5403.8 2083.48
  5422.2 2084.86  5427.3 2083.88  5434.1 2085.77  5464.5 2085.89  5505.5 2083.14
#Mann=6,-1,0
  4324.4   0.035       0  4785.6    0.07       0  4993.5    0.07       0
  5000.5    0.07       0  5049.3   0.035       0  5286.1    0.07       0
Bank Sta=4993.5,5000.5
Exp/Cntr=0.3,0.1

Type RM Length L Ch R = 1,9927,411,411,411
BEGIN DESCRIPTION:
Mapping XS 1d016d34
END DESCRIPTION:
XS GIS Cut Line= 3
      1383084.99      6899422.87      1383757.73      6899550.91
      1384246.01      6899650.73
#Sta/Elev= 30
  4316.9 2073.08  4319.8 2071.93  4357.6 2073.26  4372.0 2071.79  4632.5 2071.35
  4747.5 2067.82  4764.8 2069.75  4795.7 2069.90  4815.7 2069.71  4825.9 2065.70
  4846.2 2063.76  4851.9 2065.14  4857.0 2062.54  4876.8 2065.72  4897.1 2064.69
  4917.5 2061.02  4978.6 2058.94  5009.7 2055.90  5010.2 2055.40  5016.7 2055.90
  5019.3 2057.39  5039.8 2057.88  5063.1 2061.06  5109.1 2069.52  5131.6 2068.96
  5152.0 2072.92  5297.6 2081.99  5397.0 2087.25  5437.8 2087.98  5500.1 2085.63
#Mann=6,-1,0
  4316.9   0.035       0  4795.7    0.07       0  5009.7    0.07       0
  5016.7    0.07       0  5063.1   0.035       0  5297.6    0.07       0
Bank Sta=5009.7,5016.7
Exp/Cntr=0.3,0.1

Type RM Length L Ch R = 1,9516,249,249,249
BEGIN DESCRIPTION:
Plum Creek Trib2 17.0
END DESCRIPTION:
XS GIS Cut Line= 3
      1383355.02      6899588.04      1383555.00      6899888.00
      1383805.04      6899938.01
#Sta/Elev= 30
  4635.8 2070.27  4658.3 2068.01  4693.8 2067.46  4780.0 2066.94  4808.5 2068.74
  4829.6 2065.85  4859.6 2065.97  4895.7 2064.95  4901.7 2063.90  4910.7 2063.70
  4916.7 2061.76  4946.7 2059.20  4952.7 2057.72  4967.8 2058.47  4973.8 2056.30
  4978.3 2056.00  4998.9 2054.54  5003.0 2053.65  5003.5 2053.15  5010.0 2053.65
  5026.9 2055.40  5057.5 2054.74  5086.1 2058.36  5118.7 2061.94  5139.1 2061.99
  5149.3 2065.64  5210.5 2066.50  5239.5 2069.07  5248.7 2071.49  5251.3 2071.49
#Mann=7,-1,0
  4635.8   0.045       0  4693.8   0.035       0  4978.3    0.07       0
  5003.0    0.07       0  5010.0    0.07       0  5086.1   0.035       0
  5239.5    0.07       0
Bank Sta=5003,5010
Exp/Cntr=0.3,0.1

Type RM Length L Ch R = 1,9267,605,605,605
BEGIN DESCRIPTION:
Mapping XS 84d5e781
END DESCRIPTION:
XS GIS Cut Line= 4
      1383090.65      6899884.07      1383502.15      6900109.78
      1383550.76      6900108.05      1383977.85      6900149.72
#Sta/Elev= 30
  4477.8 2066.74  4528.4 2066.00  4557.8 2068.13  4601.4 2065.98  4711.1 2065.68
  4770.1 2065.62  4786.2 2067.34  4802.1 2064.12  4829.8 2063.75  4844.8 2061.45
  4895.3 2061.66  4911.4 2060.17  4917.1 2062.97  4927.5 2062.68  4933.2 2064.45
  4951.1 2063.63  4965.2 2060.56  5006.6 2051.98  5007.1 2051.48  5013.6 2051.98
  5051.0 2057.39  5060.3 2060.20  5090.5 2060.84  5100.5 2064.88  5152.8 2067.18
  5184.9 2070.55  5201.0 2072.66  5241.2 2073.24  5261.3 2076.10  5424.9 2078.42
#Mann=7,-1,0
  4477.8   0.045       0  4711.1   0.035       0  4844.8    0.07       0
  4965.2   0.035       0  5006.6   0.035       0  5013.6   0.035       0
  5184.9    0.07       0
Bank Sta=5006.6,5013.6
Exp/Cntr=0.3,0.1

Type RM Length L Ch R = 1,8662,61,61,61
BEGIN DESCRIPTION:
Mapping XS fffc5e6a
END DESCRIPTION:
XS GIS Cut Line= 4
      1383312.91      6901394.55      1383486.53      6900672.28
      1383599.38      6900167.08      1383950.45      6900170.75
#Sta/Elev= 30
  4255.5 2068.32  4501.9 2066.44  4543.8 2063.05  4585.8 2065.27  4627.7 2062.49
  4642.8 2064.88  4669.7 2060.95  4837.6 2058.70  4842.7 2056.32  4884.7 2053.79
  4926.6 2052.55  4931.8 2054.73  4968.6 2052.56  5016.2 2054.50  5055.9 2051.99
  5056.4 2051.49  5063.3 2051.99  5064.7 2053.85  5217.9 2057.38  5243.6 2056.11
  5269.1 2058.63  5351.1 2058.67  5379.0 2056.23  5384.1 2058.41  5516.0 2057.74
  5551.6 2060.20  5561.6 2065.67  5643.6 2069.43  5731.6 2076.20  5867.1 2077.46
#Mann=4,-1,0
  4255.5   0.035       0  5055.9   0.035       0  5063.3   0.035       0
  5643.6    0.07       0
Bank Sta=5055.9,5063.3
Exp/Cntr=0.3,0.1

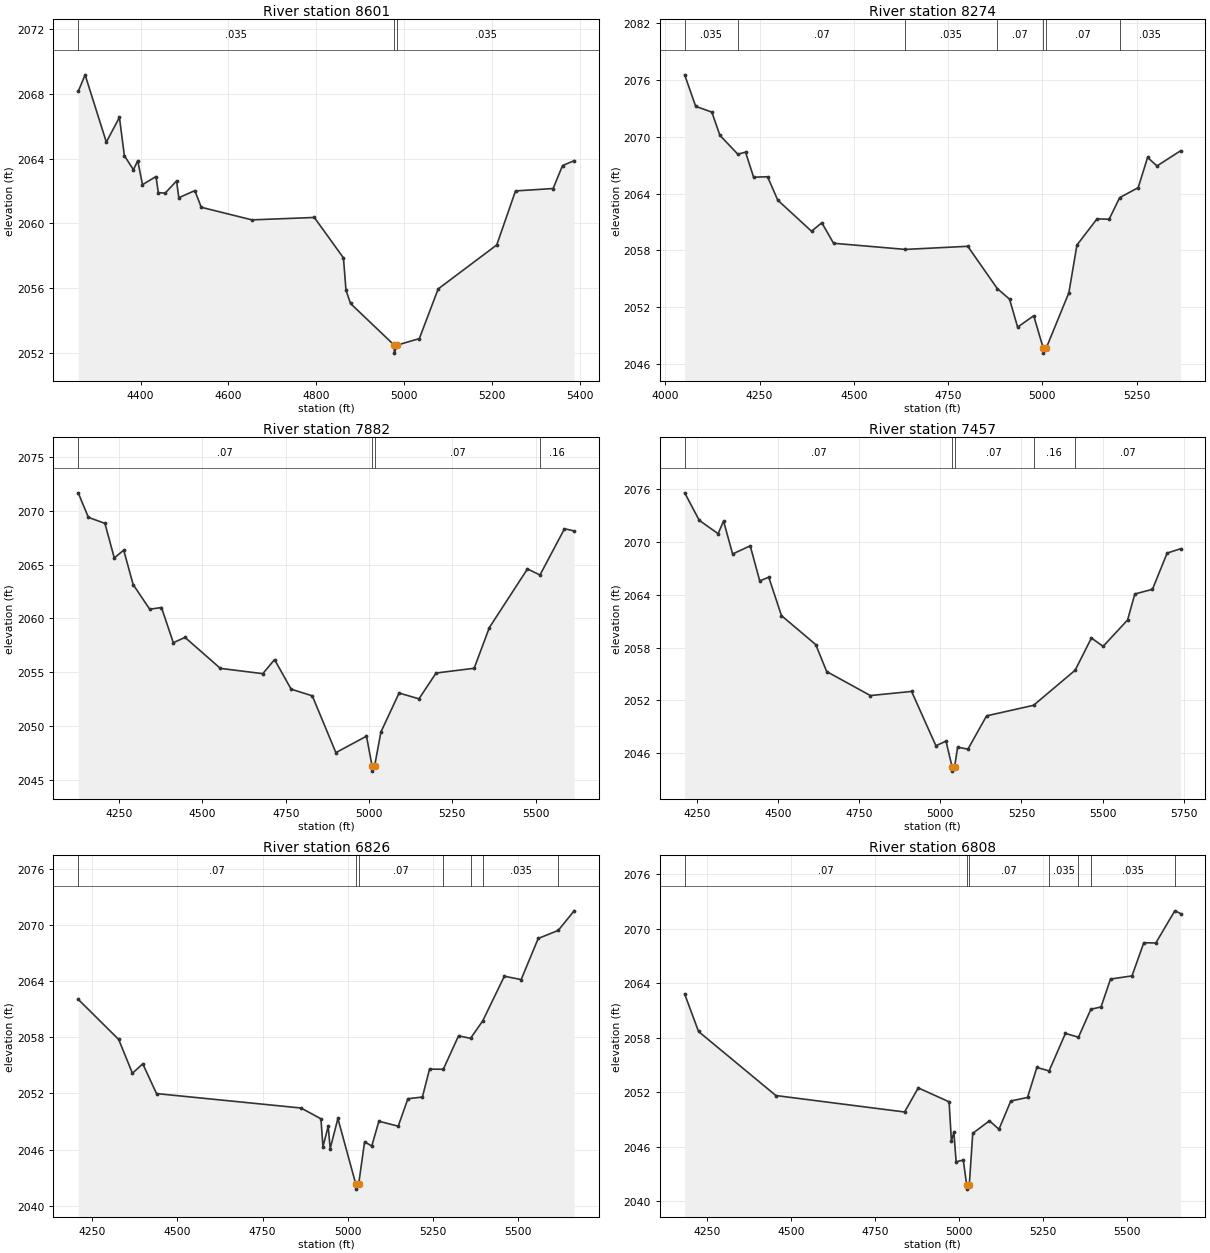
Type RM Length L Ch R = 1,8601,327,327,327
BEGIN DESCRIPTION:
Mapping XS 1948331a
END DESCRIPTION:
XS GIS Cut Line= 3
      1383366.74      6901410.13      1383540.35      6900700.06
      1383629.84      6900312.24
#Sta/Elev= 30
  4258.2 2068.16  4273.9 2069.19  4322.2 2065.03  4352.0 2066.56  4363.3 2064.19
  4383.9 2063.32  4393.7 2063.88  4404.5 2062.40  4435.3 2062.90  4440.5 2061.91
  4456.0 2061.87  4482.1 2062.63  4487.2 2061.59  4523.7 2062.03  4538.3 2061.00
  4653.8 2060.22  4795.7 2060.37  4862.0 2057.87  4867.8 2055.87  4878.1 2055.05
  4977.3 2052.48  4977.8 2051.98  4984.7 2052.48  5034.8 2052.88  5077.6 2055.95
  5211.0 2058.67  5253.7 2062.01  5339.3 2062.16  5360.8 2063.58  5387.2 2063.88
#Mann=3,-1,0
  4258.2   0.035       0  4977.3   0.035       0  4984.7   0.035       0
Bank Sta=4977.3,4984.7
Exp/Cntr=0.3,0.1

Type RM Length L Ch R = 1,8274,392,392,392
BEGIN DESCRIPTION:
Plum Creek Trib2 14.0
END DESCRIPTION:
XS GIS Cut Line= 3
      1383354.99      6901588.01      1383841.97      6900773.95
      1383970.47      6900430.39
#Sta/Elev= 30
  4051.4 2076.56  4080.6 2073.23  4123.4 2072.62  4144.8 2070.17  4192.4 2068.17
  4212.9 2068.39  4234.2 2065.74  4271.2 2065.79  4298.4 2063.31  4387.9 2060.03
  4415.1 2060.93  4446.3 2058.76  4636.9 2058.11  4802.2 2058.44  4880.6 2053.97
  4913.1 2052.85  4934.5 2049.90  4977.2 2051.10  5002.6 2047.65  5003.1 2047.15
  5010.0 2047.65  5070.4 2053.53  5091.8 2058.57  5145.1 2061.34  5177.2 2061.30
  5205.1 2063.58  5254.3 2064.64  5279.2 2067.83  5304.2 2066.93  5366.8 2068.54
#Mann=7,-1,0
  4051.4   0.035       0  4192.4    0.07       0  4636.9   0.035       0
  4880.6    0.07       0  5002.6    0.07       0  5010.0    0.07       0
  5205.1   0.035       0
Bank Sta=5002.6,5010
Exp/Cntr=0.3,0.1

Type RM Length L Ch R = 1,7882,425,425,425
BEGIN DESCRIPTION:
Mapping XS c7c4abd1
END DESCRIPTION:
XS GIS Cut Line= 3
      1383486.55      6901602.82      1384120.21      6901007.35
      1384681.32      6900745.85
#Sta/Elev= 30
  4127.2 2071.67  4157.8 2069.39  4207.4 2068.83  4235.4 2065.62  4263.8 2066.34
  4292.1 2063.14  4341.9 2060.85  4377.1 2061.01  4412.7 2057.74  4447.9 2058.23
  4553.9 2055.35  4681.3 2054.86  4716.5 2056.17  4766.3 2053.42  4829.8 2052.80
  4900.6 2047.52  4992.5 2049.05  5009.1 2046.30  5009.6 2045.80  5017.0 2046.30
  5035.7 2049.43  5090.3 2053.06  5150.0 2052.52  5201.3 2054.92  5315.6 2055.36
  5361.4 2059.15  5475.7 2064.60  5513.2 2064.03  5586.8 2068.33  5615.8 2068.13
#Mann=4,-1,0
  4127.2    0.07       0  5009.1    0.07       0  5017.0    0.07       0
  5513.2    0.16       0
Bank Sta=5009.1,5017
Exp/Cntr=0.3,0.1

Type RM Length L Ch R = 1,7457,631,631,631
BEGIN DESCRIPTION:
Plum Creek Trib2 13.0
END DESCRIPTION:
XS GIS Cut Line= 3
      1383454.98      6901738.01      1384157.06      6901382.17
      1384821.68      6901056.78
#Sta/Elev= 30
  4212.9 2075.61  4257.8 2072.48  4315.9 2070.96  4332.6 2072.40  4360.5 2068.65
  4414.7 2069.58  4444.0 2065.59  4471.8 2066.01  4510.8 2061.64  4616.5 2058.34
  4650.2 2055.27  4784.7 2052.54  4911.6 2053.01  4986.5 2046.83  5017.6 2047.35
  5036.2 2044.44  5036.7 2043.94  5044.1 2044.44  5053.4 2046.67  5085.1 2046.44
  5142.5 2050.23  5287.1 2051.43  5415.2 2055.42  5465.3 2059.09  5501.4 2058.14
  5576.7 2061.14  5599.0 2064.10  5653.3 2064.63  5698.4 2068.75  5740.0 2069.25
#Mann=5,-1,0
  4212.9    0.07       0  5036.2    0.07       0  5044.1    0.07       0
  5287.1    0.16       0  5415.2    0.07       0
Bank Sta=5036.2,5044.1
Exp/Cntr=0.3,0.1

Type RM Length L Ch R = 1,6826,18,18,18
BEGIN DESCRIPTION:
Mapping XS 2d884f5c
END DESCRIPTION:
XS GIS Cut Line= 6
      1383757.33      6901663.60      1384389.31      6901752.15
      1384458.75      6901757.35      1384500.42      6901731.31
      1384528.19      6901698.33      1384968.06      6901211.71
#Sta/Elev= 30
  4208.8 2062.04  4327.6 2057.76  4368.0 2054.15  4398.3 2055.16  4438.7 2051.98
  4863.0 2050.44  4921.4 2049.29  4927.3 2046.31  4942.7 2048.49  4948.6 2046.11
  4971.2 2049.32  5024.0 2042.28  5024.5 2041.78  5032.0 2042.28  5049.6 2046.84
  5070.6 2046.38  5091.5 2049.03  5148.3 2048.50  5176.7 2051.43  5219.3 2051.61
  5240.2 2054.59  5280.7 2054.58  5325.4 2058.14  5360.6 2057.88  5396.2 2059.73
  5459.9 2064.51  5509.2 2064.15  5559.3 2068.54  5618.1 2069.40  5664.8 2071.49
#Mann=7,-1,0
  4208.8    0.07       0  5024.0    0.07       0  5032.0    0.07       0
  5280.7   0.035       0  5360.6    0.07       0  5396.2   0.035       0
  5618.1    0.07       0
Bank Sta=5024,5032
Exp/Cntr=0.3,0.1

Type RM Length L Ch R = 1,6808,29,29,29
BEGIN DESCRIPTION:
Mapping XS 2d73046b
END DESCRIPTION:
XS GIS Cut Line= 5
      1383753.92      6901703.54      1384399.72      6901772.98
      1384469.17      6901786.87      1384500.42      6901755.62
      1384986.54      6901234.77
#Sta/Elev= 30
  4183.7 2062.80  4225.0 2058.68  4455.3 2051.63  4838.6 2049.82  4879.3 2052.47
  4971.2 2050.94  4978.1 2046.61  4985.4 2047.60  4992.2 2044.34  5013.4 2044.53
  5023.4 2041.83  5023.9 2041.33  5031.4 2041.83  5041.6 2047.47  5091.4 2048.85
  5119.7 2047.92  5154.9 2051.03  5204.7 2051.42  5232.6 2054.72  5269.1 2054.34
  5317.6 2058.47  5356.5 2058.05  5393.4 2061.13  5423.7 2061.38  5451.9 2064.45
  5515.9 2064.80  5551.1 2068.45  5586.8 2068.42  5643.4 2071.96  5660.7 2071.66
#Mann=7,-1,0
  4183.7    0.07       0  5023.4    0.07       0  5031.4    0.07       0
  5269.1   0.035       0  5356.5    0.07       0  5393.4   0.035       0
  5643.4    0.07       0
Bank Sta=5023.4,5031.4
Exp/Cntr=0.3,0.1

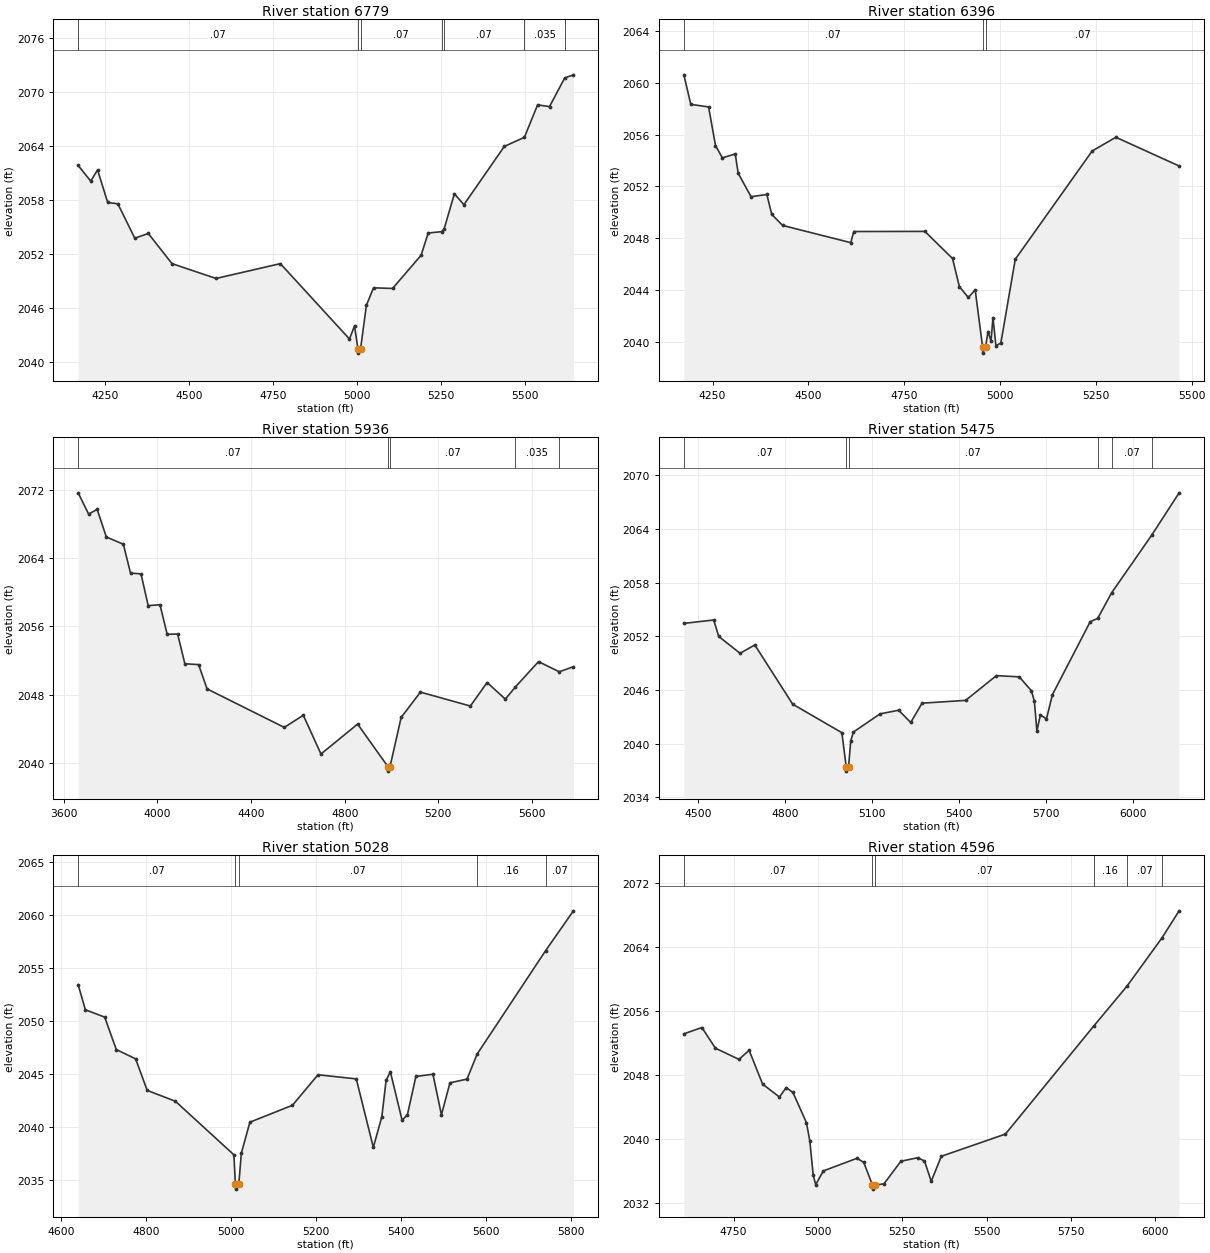
Type RM Length L Ch R = 1,6779,383,383,383
BEGIN DESCRIPTION:
Mapping XS 1842bd87
END DESCRIPTION:
XS GIS Cut Line= 6
      1383767.81      6901741.73      1384427.50      6901818.12
      1384493.47      6901814.65      1384528.19      6901776.45
      1384545.56      6901748.67      1385007.39      6901279.89
#Sta/Elev= 30
  4170.7 2061.81  4208.1 2060.08  4228.3 2061.32  4258.5 2057.70  4288.7 2057.55
  4339.0 2053.73  4379.3 2054.25  4449.7 2050.90  4580.6 2049.25  4771.9 2050.90
  4977.4 2042.52  4992.4 2043.98  5002.5 2041.45  5003.0 2040.95  5010.5 2041.45
  5027.8 2046.28  5049.0 2048.21  5105.5 2048.14  5190.4 2051.83  5211.5 2054.30
  5252.2 2054.46  5258.9 2054.76  5289.4 2058.67  5317.7 2057.45  5437.8 2063.93
  5497.5 2064.94  5536.8 2068.55  5572.3 2068.36  5617.4 2071.54  5643.3 2071.89
#Mann=7,-1,0
  4170.7    0.07       0  5002.5    0.07       0  5010.5    0.07       0
  5252.2   0.035       0  5258.9    0.07       0  5497.5   0.035       0
  5617.4    0.16       0
Bank Sta=5002.5,5010.5
Exp/Cntr=0.3,0.1

Type RM Length L Ch R = 1,6396,460,460,460
BEGIN DESCRIPTION:
Plum Creek Trib2 12.0
END DESCRIPTION:
XS GIS Cut Line= 3
      1383854.97      6901887.99      1384655.00      6902088.00
      1385121.01      6902127.07
#Sta/Elev= 30
  4175.0 2060.61  4193.1 2058.33  4239.5 2058.13  4257.5 2055.15  4275.5 2054.20
  4309.0 2054.50  4316.8 2053.01  4350.3 2051.20  4391.5 2051.37  4404.4 2049.83
  4432.7 2048.98  4610.5 2047.65  4618.3 2048.51  4803.8 2048.52  4876.0 2046.43
  4894.0 2044.25  4917.2 2043.42  4935.2 2044.00  4954.4 2039.62  4954.9 2039.12
  4962.4 2039.62  4968.7 2040.79  4976.5 2040.05  4981.6 2041.87  4989.3 2039.68
  5002.2 2039.91  5039.8 2046.37  5240.5 2054.73  5302.3 2055.79  5467.3 2053.57
#Mann=3,-1,0
  4175.0    0.07       0  4954.4    0.07       0  4962.4    0.07       0
Bank Sta=4954.4,4962.4
Exp/Cntr=0.3,0.1

Type RM Length L Ch R = 1,5936,461,461,461
BEGIN DESCRIPTION:
Plum Creek Trib2 11.0
END DESCRIPTION:
XS GIS Cut Line= 4
      1383605.00      6901838.00      1384805.00      6902438.00
      1384949.31      6902501.13      1385349.40      6902032.69
#Sta/Elev= 30
  3661.7 2071.67  3706.4 2069.17  3742.8 2069.73  3781.9 2066.49  3854.6 2065.64
  3885.3 2062.25  3930.0 2062.16  3960.8 2058.43  4011.1 2058.54  4041.8 2055.07
  4086.5 2055.10  4117.3 2051.61  4176.0 2051.51  4212.3 2048.66  4542.1 2044.14
  4623.2 2045.57  4698.7 2041.02  4855.2 2044.53  4985.4 2039.51  4985.9 2039.01
  4993.4 2039.51  5041.1 2045.31  5123.4 2048.28  5336.9 2046.65  5408.3 2049.41
  5486.2 2047.46  5529.1 2048.89  5627.8 2051.86  5716.4 2050.67  5776.9 2051.26
#Mann=5,-1,0
  3661.7    0.07       0  4985.4    0.07       0  4993.4    0.07       0
  5529.1   0.035       0  5716.4    0.07       0
Bank Sta=4985.4,4993.4
Exp/Cntr=0.3,0.1

Type RM Length L Ch R = 1,5475,447,447,447
BEGIN DESCRIPTION:
Plum Creek Trib2 10.0
END DESCRIPTION:
XS GIS Cut Line= 3
      1383955.24      6902349.35      1384455.00      6902588.00
      1385564.90      6902907.90
#Sta/Elev= 30
  4450.8 2053.45  4553.9 2053.83  4571.1 2051.99  4644.7 2050.11  4695.6 2051.04
  4826.2 2044.42  4996.0 2041.23  5010.9 2037.43  5011.4 2036.93  5019.1 2037.43
  5026.7 2040.33  5035.8 2041.30  5127.6 2043.33  5191.9 2043.74  5233.6 2042.37
  5272.7 2044.53  5423.0 2044.84  5529.2 2047.61  5608.2 2047.47  5649.9 2045.92
  5660.3 2044.74  5669.0 2041.42  5681.1 2043.24  5701.9 2042.76  5722.7 2045.49
  5853.0 2053.64  5878.8 2054.01  5926.6 2056.86  6066.3 2063.37  6159.7 2068.05
#Mann=6,-1,0
  4450.8    0.07       0  5010.9    0.07       0  5019.1    0.07       0
  5878.8    0.16       0  5926.6    0.07       0  6066.3   0.035       0
Bank Sta=5010.9,5019.1
Exp/Cntr=0.3,0.1

Type RM Length L Ch R = 1,5028,432,432,432
BEGIN DESCRIPTION:
Plum Creek Trib2 9.0
END DESCRIPTION:
XS GIS Cut Line= 3
      1384255.02      6903037.99      1384605.00      6902938.00
      1385404.96      6902888.00
#Sta/Elev= 30
  4639.9 2053.44  4656.8 2051.08  4702.3 2050.38  4729.6 2047.32  4775.1 2046.44
  4802.4 2043.46  4868.7 2042.44  5006.4 2037.38  5009.8 2034.64  5010.3 2034.14
  5018.0 2034.64  5023.9 2037.53  5044.0 2040.46  5144.2 2042.06  5204.3 2044.94
  5294.4 2044.55  5334.5 2038.08  5354.6 2040.99  5364.6 2044.43  5374.6 2045.22
  5402.2 2040.65  5414.7 2041.16  5434.7 2044.78  5474.8 2044.99  5494.8 2041.16
  5514.9 2044.18  5555.0 2044.53  5578.8 2046.89  5739.8 2056.65  5805.4 2060.42
#Mann=5,-1,0
  4639.9    0.07       0  5009.8    0.07       0  5018.0    0.07       0
  5578.8    0.16       0  5739.8    0.07       0
Bank Sta=5009.8,5018
Exp/Cntr=0.3,0.1

Type RM Length L Ch R = 1,4596,468,468,468
BEGIN DESCRIPTION:
Plum Creek Trib2 8.0
END DESCRIPTION:
XS GIS Cut Line= 3
      1384111.48      6903342.42      1384505.00      6903338.00
      1385580.13      6903345.89
#Sta/Elev= 30
  4602.5 2053.15  4656.0 2053.94  4696.0 2051.36  4766.0 2049.96  4796.0 2051.10
  4836.0 2046.88  4886.0 2045.26  4906.0 2046.45  4926.0 2045.83  4966.0 2042.07
  4976.0 2039.79  4986.0 2035.54  4993.5 2034.32  5016.0 2036.04  5116.0 2037.62
  5136.0 2037.11  5161.9 2034.27  5162.4 2033.77  5170.2 2034.27  5196.1 2034.44
  5246.1 2037.25  5296.1 2037.69  5316.1 2037.28  5336.1 2034.75  5366.1 2037.87
  5556.1 2040.64  5817.6 2054.10  5916.6 2059.10  6020.5 2065.13  6071.2 2068.50
#Mann=6,-1,0
  4602.5    0.07       0  5161.9    0.07       0  5170.2    0.07       0
  5817.6    0.16       0  5916.6    0.07       0  6020.5   0.035       0
Bank Sta=5161.9,5170.2
Exp/Cntr=0.3,0.1