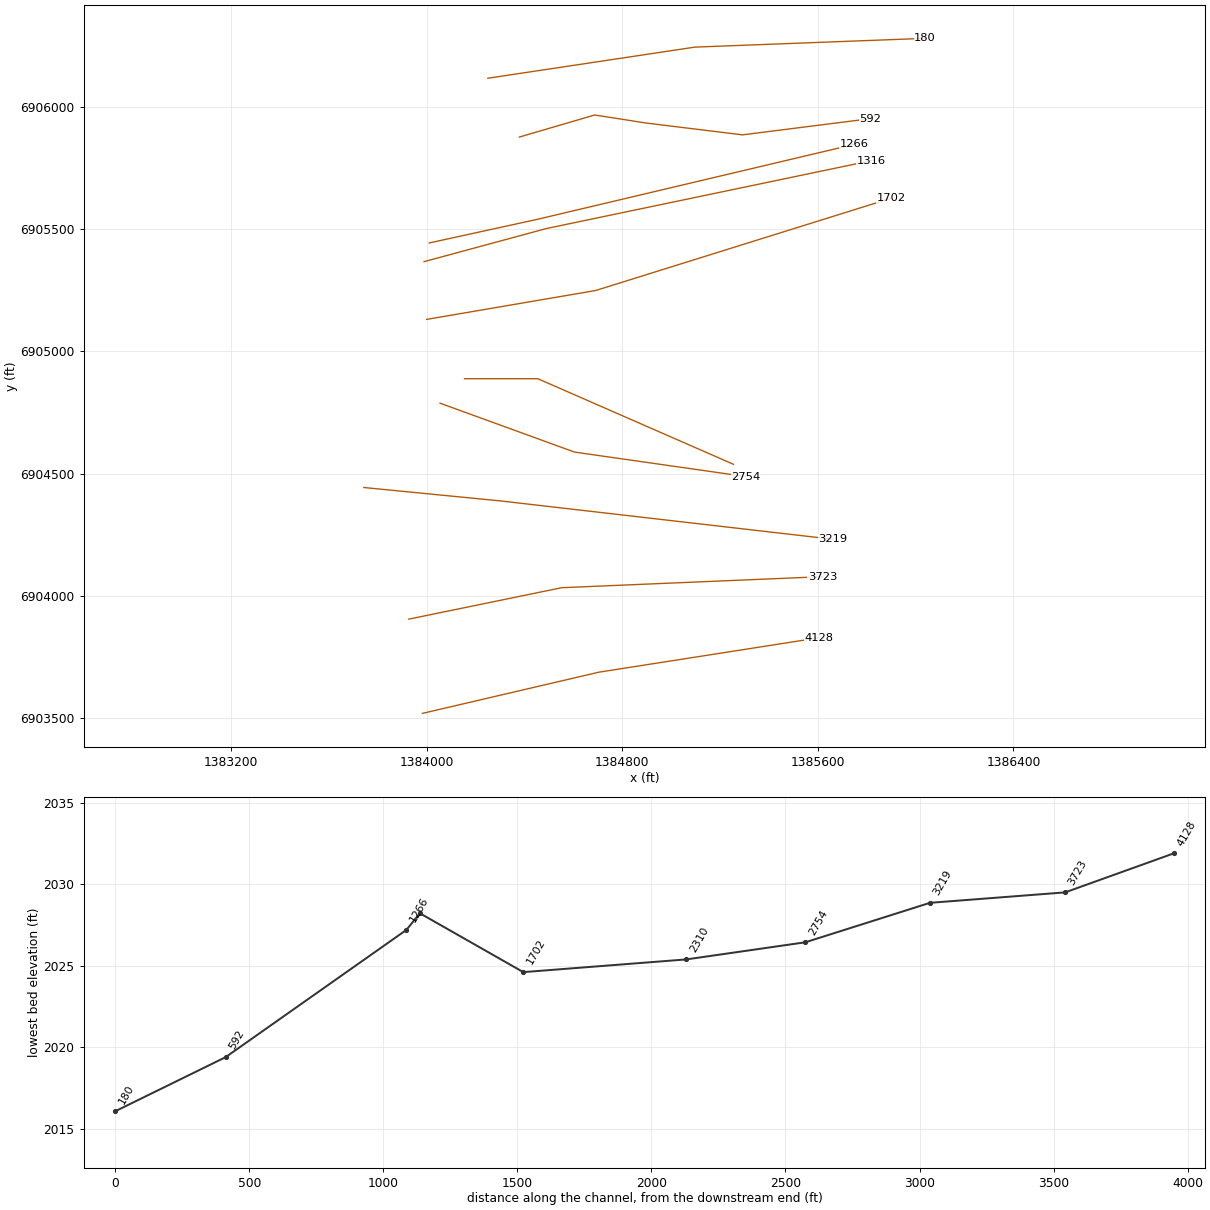
HEC-RAS study Plum Creek Trib2.prj: Plum Creek Trib2 Base Level Engineering

--- Plum Creek Trib2.g01 (geometry) --- (continued)

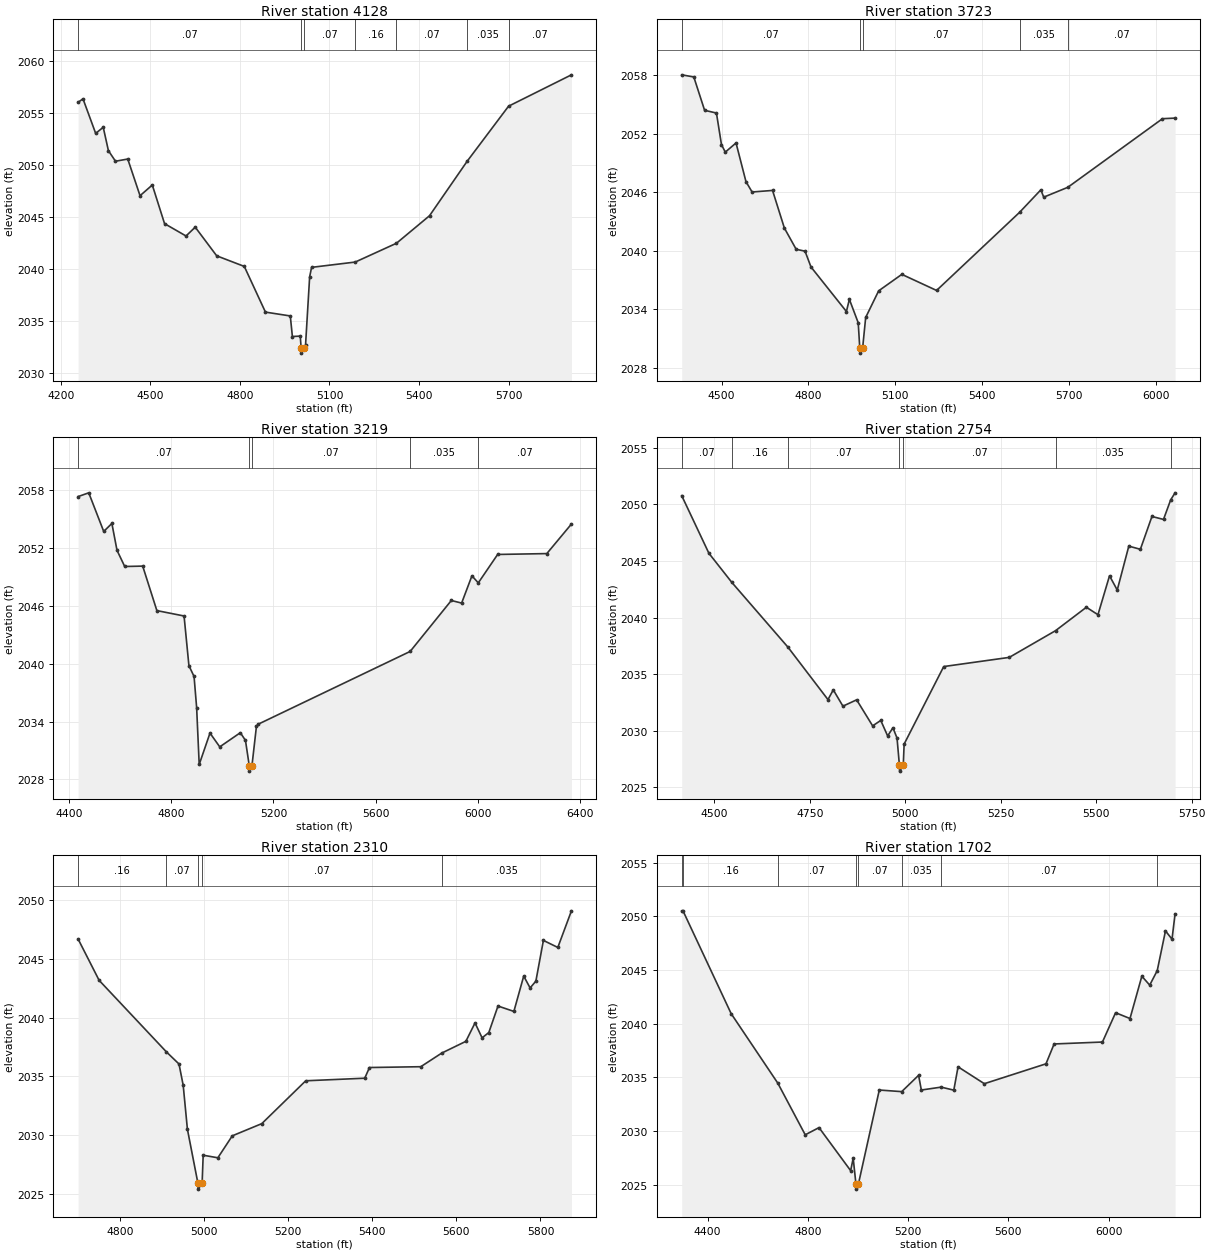
Type RM Length L Ch R = 1,4128,405,405,405
BEGIN DESCRIPTION:
Plum Creek Trib2 7.0
END DESCRIPTION:
XS GIS Cut Line= 3
      1383983.05      6903519.51      1384705.00      6903688.00
      1385604.54      6903828.53
#Sta/Elev= 30
  4258.3 2056.03  4274.7 2056.37  4317.2 2053.04  4342.5 2053.63  4359.8 2051.38
  4383.5 2050.36  4424.6 2050.57  4465.7 2047.04  4506.8 2048.07  4547.8 2044.35
  4619.7 2043.16  4650.5 2044.01  4722.4 2041.25  4814.8 2040.23  4885.6 2035.83
  4968.8 2035.46  4975.8 2033.48  5002.2 2033.52  5005.0 2032.38  5005.5 2031.88
  5014.6 2032.38  5019.9 2032.68  5033.6 2039.23  5040.1 2040.14  5186.2 2040.65
  5324.2 2042.46  5434.9 2045.11  5561.0 2050.36  5699.6 2055.66  5910.1 2058.68
#Mann=7,-1,0
  4258.3    0.07       0  5005.0    0.07       0  5014.6    0.07       0
  5186.2    0.16       0  5324.2    0.07       0  5561.0   0.035       0
  5699.6    0.07       0
Bank Sta=5005,5014.6
Exp/Cntr=0.3,0.1

Type RM Length L Ch R = 1,3723,504,504,504
BEGIN DESCRIPTION:
Mapping XS 8010deb3
END DESCRIPTION:
XS GIS Cut Line= 3
      1383927.48      6903904.92      1384552.50      6904033.40
      1385618.46      6904078.53
#Sta/Elev= 30
  4362.1 2058.04  4403.9 2057.82  4441.2 2054.40  4482.1 2054.12  4499.5 2050.88
  4512.7 2050.11  4549.8 2051.05  4584.2 2047.08  4605.3 2046.02  4676.0 2046.18
  4716.9 2042.32  4757.7 2040.14  4788.3 2039.95  4808.8 2038.33  4931.3 2033.76
  4941.5 2035.01  4972.1 2032.60  4977.5 2029.99  4978.0 2029.49  4987.2 2029.99
  4997.9 2033.15  5042.7 2035.88  5122.8 2037.57  5242.9 2035.92  5529.6 2043.93
  5603.2 2046.24  5613.2 2045.49  5696.4 2046.50  6023.6 2053.54  6067.1 2053.60
#Mann=5,-1,0
  4362.1    0.07       0  4977.5    0.07       0  4987.2    0.07       0
  5529.6   0.035       0  5696.4    0.07       0
Bank Sta=4977.5,4987.2
Exp/Cntr=0.3,0.1

Type RM Length L Ch R = 1,3219,465,465,465
BEGIN DESCRIPTION:
Plum Creek Trib2 6.0
END DESCRIPTION:
XS GIS Cut Line= 3
      1383743.45      6904443.12      1384305.00      6904388.00
      1385661.76      6904231.53
#Sta/Elev= 30
  4435.9 2057.36  4477.6 2057.75  4536.2 2053.74  4568.1 2054.57  4588.2 2051.78
  4618.3 2050.10  4688.7 2050.14  4744.1 2045.52  4850.5 2044.96  4869.5 2039.80
  4889.6 2038.68  4899.7 2035.44  4909.7 2029.54  4951.9 2032.80  4990.1 2031.37
  5070.6 2032.84  5090.7 2032.04  5105.9 2029.35  5106.4 2028.85  5115.8 2029.35
  5133.6 2033.50  5141.1 2033.73  5735.0 2041.28  5896.0 2046.57  5936.3 2046.30
  5976.6 2049.13  6001.5 2048.40  6077.2 2051.35  6269.6 2051.44  6365.9 2054.51
#Mann=5,-1,0
  4435.9    0.07       0  5105.9    0.07       0  5115.8    0.07       0
  5735.0   0.035       0  6001.5    0.07       0
Bank Sta=5105.9,5115.8
Exp/Cntr=0.3,0.1

Type RM Length L Ch R = 1,2754,444,444,444
BEGIN DESCRIPTION:
Plum Creek Trib2 5.0
END DESCRIPTION:
XS GIS Cut Line= 3
      1384054.99      6904788.00      1384605.00      6904588.00
      1385304.95      6904488.01
#Sta/Elev= 30
  4414.3 2050.77  4485.5 2045.68  4545.7 2043.10  4692.4 2037.39  4797.4 2032.75
  4811.3 2033.61  4836.6 2032.17  4872.5 2032.73  4914.4 2030.43  4935.7 2030.91
  4953.7 2029.54  4967.6 2030.26  4978.3 2029.35  4984.6 2026.93  4985.1 2026.43
  4994.6 2026.93  4996.9 2028.82  5100.6 2035.67  5272.3 2036.48  5393.5 2038.84
  5474.3 2040.91  5504.6 2040.25  5534.9 2043.69  5555.1 2042.43  5585.4 2046.31
  5615.7 2046.03  5646.0 2048.93  5676.3 2048.67  5695.1 2050.40  5706.6 2051.02
#Mann=7,-1,0
  4414.3    0.07       0  4545.7    0.16       0  4692.4    0.07       0
  4984.6    0.07       0  4994.6    0.07       0  5393.5   0.035       0
  5695.1    0.07       0
Bank Sta=4984.6,4994.6
Exp/Cntr=0.3,0.1

Type RM Length L Ch R = 1,2310,608,608,608
BEGIN DESCRIPTION:
Plum Creek Trib2 4.0
END DESCRIPTION:
XS GIS Cut Line= 3
      1384154.95      6904888.00      1384455.00      6904888.00
      1385255.04      6904537.98
#Sta/Elev= 30
  4700.4 2046.69  4750.4 2043.17  4910.5 2037.07  4940.4 2036.04  4950.4 2034.22
  4960.4 2030.48  4985.4 2025.88  4985.9 2025.38  4995.4 2025.88  4997.9 2028.27
  5032.8 2028.05  5067.1 2029.92  5137.3 2030.96  5241.8 2034.61  5382.1 2034.83
  5393.4 2035.74  5515.4 2035.81  5565.2 2036.97  5622.6 2037.97  5644.4 2039.54
  5661.2 2038.27  5677.2 2038.72  5699.0 2040.98  5736.8 2040.52  5760.2 2043.53
  5775.4 2042.52  5789.1 2043.10  5807.0 2046.57  5841.3 2045.97  5873.7 2049.09
#Mann=5,-1,0
  4700.4    0.16       0  4910.5    0.07       0  4985.4    0.07       0
  4995.4    0.07       0  5565.2   0.035       0
Bank Sta=4985.4,4995.4
Exp/Cntr=0.3,0.1

Type RM Length L Ch R = 1,1702,386,386,386
BEGIN DESCRIPTION:
Mapping XS 4be8e3ab
END DESCRIPTION:
XS GIS Cut Line= 3
      1384000.46      6905130.63      1384691.39      6905248.67
      1385901.60      6905626.65
#Sta/Elev= 30
  4296.5 2050.49  4301.6 2050.52  4493.9 2040.94  4680.0 2034.47  4789.4 2029.66
  4844.4 2030.33  4970.7 2026.32  4980.8 2027.48  4991.7 2025.10  4992.2 2024.60
  5001.8 2025.10  5085.0 2033.83  5174.4 2033.68  5241.8 2035.20  5252.7 2033.83
  5331.7 2034.10  5382.3 2033.82  5399.3 2035.99  5504.1 2034.42  5750.1 2036.27
  5782.6 2038.12  5975.5 2038.30  6027.9 2041.03  6085.4 2040.49  6132.7 2044.43
  6164.1 2043.60  6194.1 2044.95  6227.0 2048.65  6253.1 2047.88  6265.3 2050.24
#Mann=8,-1,0
  4296.5    0.07       0  4301.6    0.16       0  4680.0    0.07       0
  4991.7    0.07       0  5001.8    0.07       0  5174.4   0.035       0
  5331.7    0.07       0  6194.1   0.035       0
Bank Sta=4991.7,5001.8
Exp/Cntr=0.3,0.1

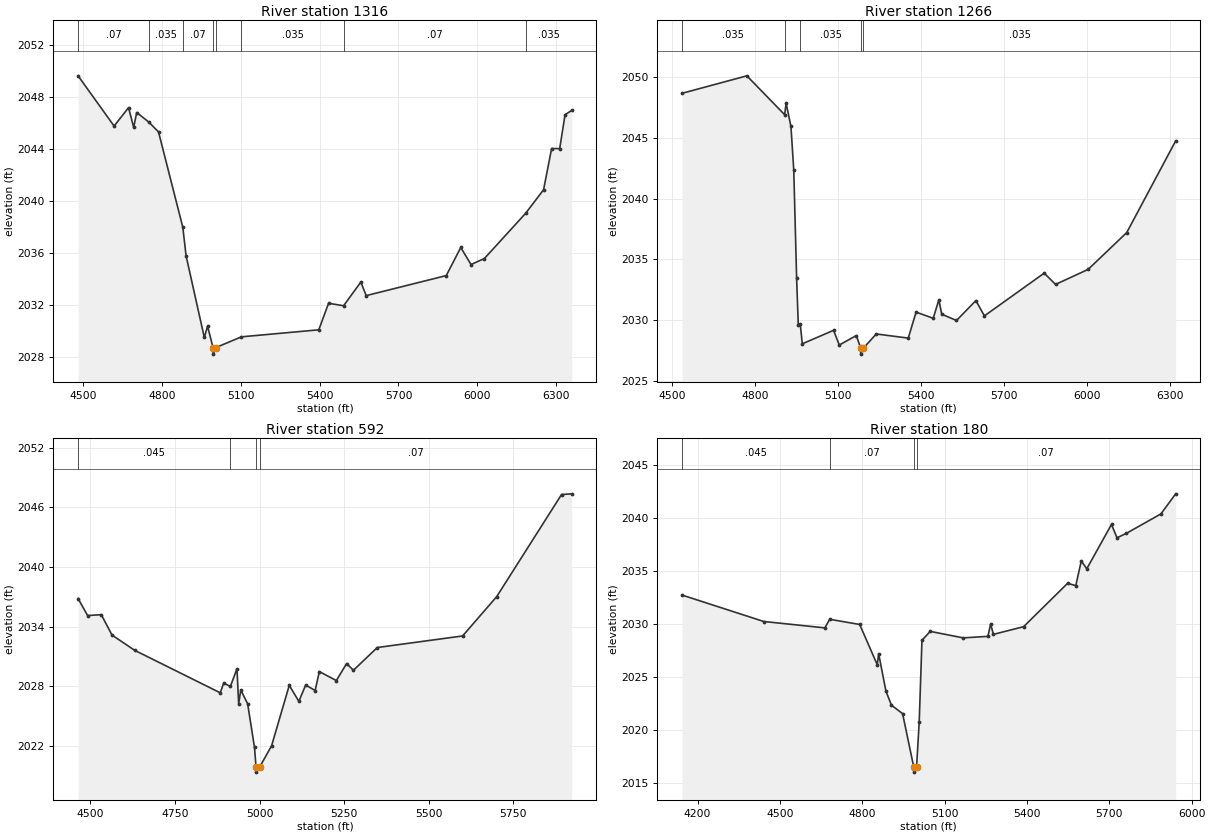
Type RM Length L Ch R = 1,1316,50,50,50
BEGIN DESCRIPTION:
Mapping XS 67868e05
END DESCRIPTION:
XS GIS Cut Line= 3
      1383989.95      6905366.72      1384490.00      6905502.15
      1385819.84      6905779.92
#Sta/Elev= 30
  4482.1 2049.61  4618.9 2045.75  4673.8 2047.16  4693.4 2045.65  4704.9 2046.79
  4750.5 2046.06  4787.8 2045.30  4880.2 2037.96  4892.6 2035.77  4961.9 2029.49
  4974.3 2030.36  4995.1 2028.71  4995.6 2028.21  5005.2 2028.71  5103.1 2029.54
  5397.1 2030.08  5434.3 2032.12  5491.4 2031.93  5556.9 2033.75  5577.4 2032.71
  5881.7 2034.25  5936.8 2036.41  5975.8 2035.10  6026.6 2035.56  6183.0 2039.03
  6251.6 2040.85  6282.2 2044.02  6312.9 2044.01  6333.3 2046.62  6358.7 2046.95
#Mann=8,-1,0
  4482.1    0.07       0  4750.5   0.035       0  4880.2    0.07       0
  4995.1    0.07       0  5005.2    0.07       0  5103.1   0.035       0
  5491.4    0.07       0  6183.0   0.035       0
Bank Sta=4995.1,5005.2
Exp/Cntr=0.3,0.1

Type RM Length L Ch R = 1,1266,674,674,674
BEGIN DESCRIPTION:
Mapping XS cc44353d
END DESCRIPTION:
XS GIS Cut Line= 3
      1384010.87      6905443.13      1384455.28      6905540.34
      1385746.92      6905845.89
#Sta/Elev= 30
  4536.8 2048.67  4770.8 2050.11  4907.2 2046.91  4912.6 2047.85  4930.0 2045.94
  4940.2 2042.34  4950.5 2033.44  4956.5 2029.61  4963.7 2029.64  4971.0 2028.04
  5083.9 2029.15  5104.5 2027.94  5166.1 2028.72  5181.6 2027.69  5182.1 2027.19
  5191.7 2027.69  5238.1 2028.85  5353.5 2028.51  5381.9 2030.65  5443.6 2030.14
  5464.1 2031.66  5474.4 2030.48  5527.7 2029.96  5597.7 2031.60  5628.5 2030.34
  5844.3 2033.86  5885.4 2032.93  6003.0 2034.17  6142.3 2037.20  6319.0 2044.75
#Mann=5,-1,0
  4536.8   0.035       0  4907.2    0.07       0  4963.7   0.035       0
  5181.6   0.035       0  5191.7   0.035       0
Bank Sta=5181.6,5191.7
Exp/Cntr=0.3,0.1

Type RM Length L Ch R = 1,592,412,412,412
BEGIN DESCRIPTION:
Mapping XS 91103eaa
END DESCRIPTION:
XS GIS Cut Line= 5
      1384379.24      6905876.22      1384687.44      6905966.43
      1384899.40      6905933.36      1385291.73      6905885.25
      1385814.85      6905951.40
#Sta/Elev= 30
  4464.1 2036.83  4492.2 2035.12  4532.6 2035.21  4564.3 2033.16  4631.1 2031.63
  4884.0 2027.36  4894.1 2028.33  4913.9 2028.00  4933.4 2029.77  4938.4 2026.26
  4944.7 2027.64  4964.9 2026.26  4985.2 2021.87  4989.8 2019.89  4990.3 2019.39
  5000.2 2019.89  5035.6 2022.03  5087.9 2028.11  5116.2 2026.50  5136.4 2028.14
  5164.3 2027.59  5176.7 2029.49  5227.0 2028.59  5257.3 2030.30  5277.4 2029.62
  5347.9 2031.91  5599.9 2033.07  5700.8 2037.03  5892.2 2047.28  5922.3 2047.35
#Mann=4,-1,0
  4464.1   0.045       0  4913.9    0.07       0  4989.8    0.07       0
  5000.2    0.07       0
Bank Sta=4989.8,5000.2
Exp/Cntr=0.3,0.1

Type RM Length L Ch R = 1,180,0,0,0
BEGIN DESCRIPTION:
Plum Creek Trib2 1.0
END DESCRIPTION:
XS GIS Cut Line= 3
      1384250.46      6906116.74      1385097.54      6906244.05
      1386038.66      6906279.93
#Sta/Elev= 30
  4143.4 2032.74  4441.3 2030.25  4663.7 2029.65  4681.3 2030.46  4790.6 2029.97
  4854.6 2026.18  4859.7 2027.22  4886.2 2023.70  4906.4 2022.37  4946.9 2021.58
  4987.4 2016.57  4987.9 2016.07  4997.9 2016.57  5007.5 2020.82  5017.5 2028.48
  5047.5 2029.32  5167.6 2028.71  5257.6 2028.85  5267.7 2030.02  5277.7 2029.04
  5387.7 2029.76  5547.9 2033.84  5577.9 2033.63  5597.9 2035.95  5617.9 2035.21
  5708.0 2039.39  5728.0 2038.13  5761.5 2038.54  5888.1 2040.38  5941.8 2042.27
#Mann=4,-1,0
  4143.4   0.045       0  4681.3    0.07       0  4987.4    0.07       0
  4997.9    0.07       0
Bank Sta=4987.4,4997.9
Exp/Cntr=0.3,0.1

Chan Stop Cuts=-1