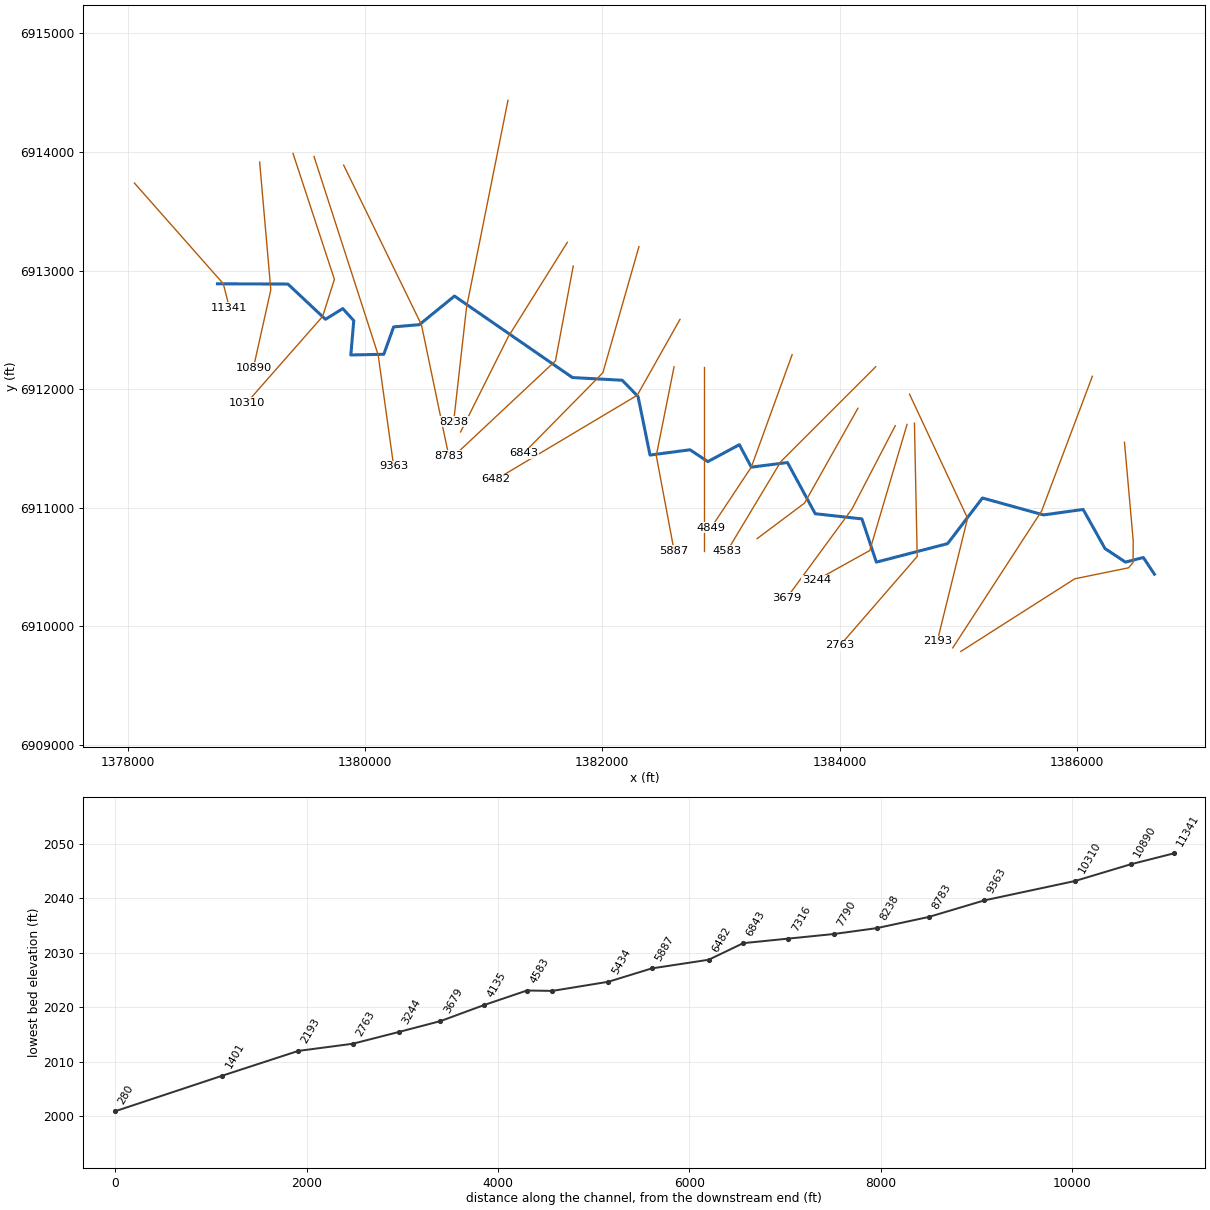
--- Plum Creek Trib3.prj (project) ---

Proj Title=Plum Creek Trib3 Base Level Engineering
Current Plan=p01
Default Exp/Contr=0.3,0.1
English Units
Geom File=g01
Flow File=f01
Plan File=p01
BEGIN DESCRIPTION:
Plum Creek Trib3
END DESCRIPTION:

--- Plum Creek Trib3.p01 (plan) ---

Plan Title=Multiple Run
Short Identifier=Multiple
Geom File=g01
Flow File=f01
Subcritical Flow
K Sum by GR= 0
Std Step Tol= 0.01
Critical Tol= 0.01
Num of Std Step Trials= 20
Max Error Tol= 0.3
Flow Tol Ratio= 0.001
Split Flow NTrial= 30
Split Flow Tol= 0.02
Split Flow Ratio= 0.02
Log Output Level= 0
Friction Slope Method= 1
Unsteady Friction Slope Method= 2
Unsteady Bridges Friction Slope Method= 1
Parabolic Critical Depth
Global Vel Dist=  1 , 1 , 1
Global Log Level= 0
CheckData=True
Encroach Param= -1, 0, 0, 0
BEGIN DESCRIPTION:
Multiple Run
END DESCRIPTION:

--- Plum Creek Trib3.f01 (steady flow) ---

Flow Title=Multiple
Number of Profiles=7
Profile Names=10-year,25-year,50-year,1pct_min,100-year,1pct_plu,500-year
River Rch & RM= Plum Creek Trib3,Reach-1,11341
     266     378     473     295     588    1174     920
River Rch & RM= Plum Creek Trib3,Reach-1,10310
     353     507     638     399     797    1590    1260
River Rch & RM= Plum Creek Trib3,Reach-1,8783
     517     757     965     611    1220    2434    1974
River Rch & RM= Plum Creek Trib3,Reach-1,6482
     611     897    1146     727    1450    2893    2351
River Rch & RM= Plum Creek Trib3,Reach-1,1401
     642     946    1211     769    1535    3063    2499
Boundary for River Rch & Prof#=Plum Creek Trib3,Reach-1,1
Up Type=0
Dn Type=3
Dn Slope=0.005
Boundary for River Rch & Prof#=Plum Creek Trib3,Reach-1,2
Up Type=0
Dn Type=3
Dn Slope=0.005
Boundary for River Rch & Prof#=Plum Creek Trib3,Reach-1,3
Up Type=0
Dn Type=3
Dn Slope=0.005
Boundary for River Rch & Prof#=Plum Creek Trib3,Reach-1,4
Up Type=0
Dn Type=3
Dn Slope=0.005
Boundary for River Rch & Prof#=Plum Creek Trib3,Reach-1,5
Up Type=0
Dn Type=3
Dn Slope=0.005
Boundary for River Rch & Prof#=Plum Creek Trib3,Reach-1,6
Up Type=0
Dn Type=3
Dn Slope=0.005
Boundary for River Rch & Prof#=Plum Creek Trib3,Reach-1,7
Up Type=0
Dn Type=3
Dn Slope=0.005

--- Plum Creek Trib3.g01 (geometry) ---

Geom Title=Existing Conditions

River Reach=Plum Creek Trib3,Reach-1
Reach XY= 30
      1378755.00      6912888.00      1379349.11      6912886.03
      1379665.70      6912588.70      1379811.69      6912679.04
      1379904.40      6912577.39      1379879.69      6912287.70
      1380157.47      6912293.45      1380240.87      6912524.64
      1380457.70      6912543.36      1380753.50      6912784.54
      1381748.26      6912097.13      1382168.22      6912074.38
      1382301.46      6911936.54      1382402.26      6911443.34
      1382739.78      6911487.75      1382889.64      6911387.90
      1383155.34      6911530.79      1383256.25      6911341.36
      1383561.21      6911380.20      1383795.17      6910948.47
      1384188.79      6910904.71      1384310.71      6910539.89
      1384911.34      6910696.02      1385204.98      6911080.92
      1385720.22      6910938.24      1386053.97      6910984.39
      1386238.33      6910654.65      1386410.90      6910539.98
      1386561.75      6910578.90      1386655.00      6910438.00

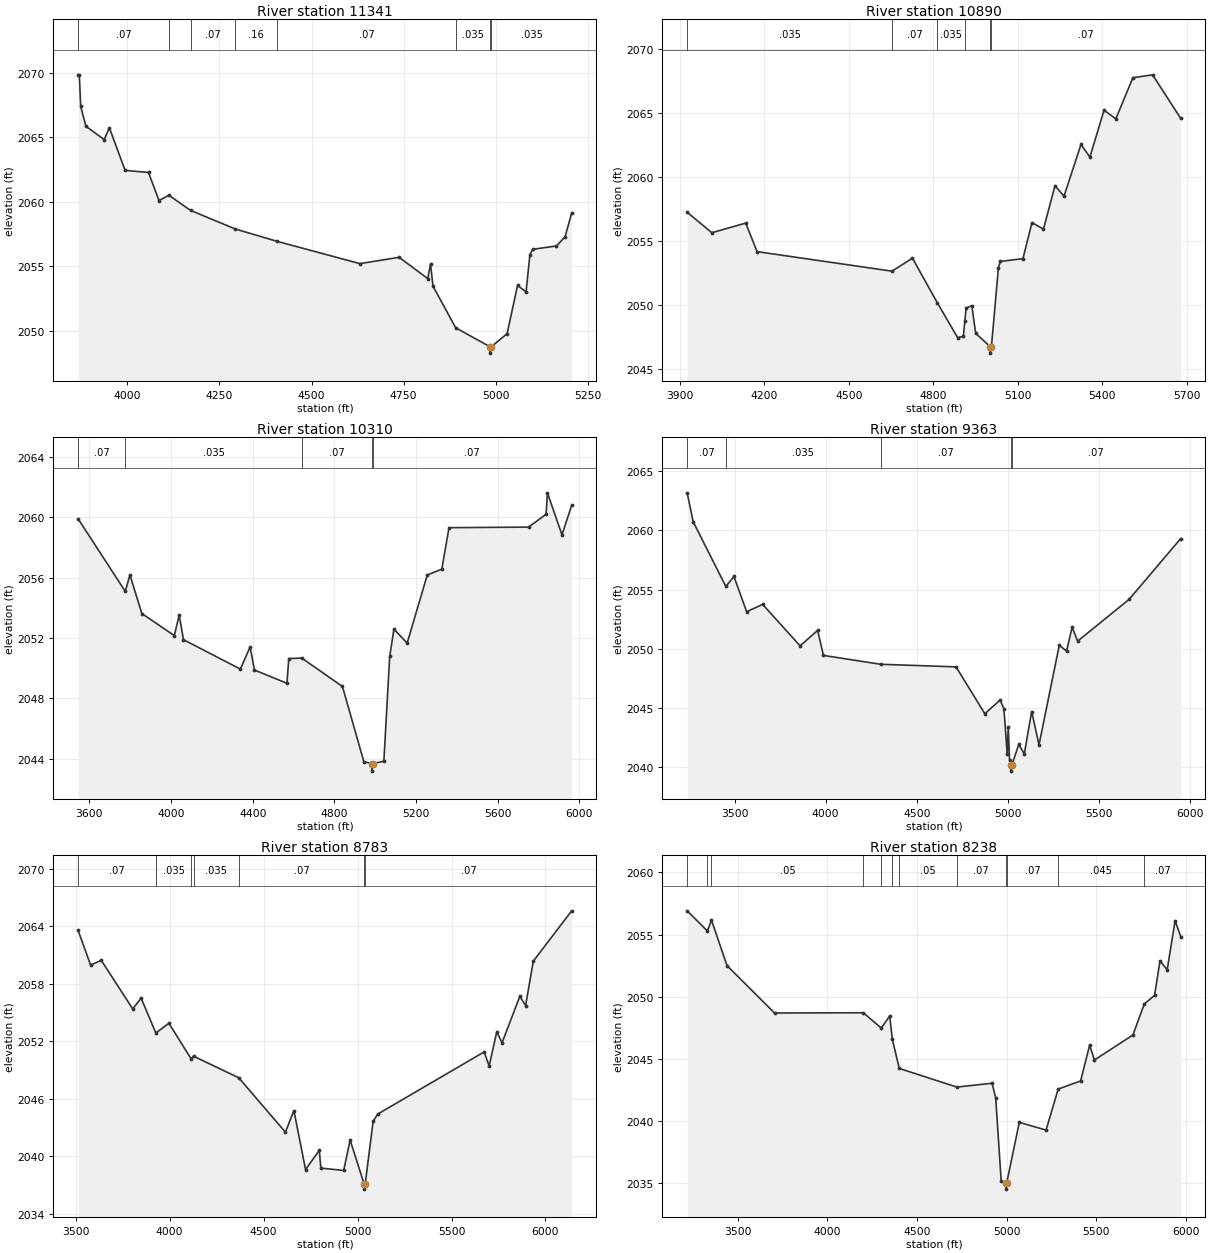
Type RM Length L Ch R = 1,11341,451,451,451
BEGIN DESCRIPTION:
Plum Creek Trib3 18.0
END DESCRIPTION:
XS GIS Cut Line= 3
      1378055.01      6913737.99      1378805.00      6912888.00
      1378855.00      6912688.02
#Sta/Elev= 30
  3866.4 2069.83  3869.7 2069.83  3873.5 2067.38  3887.7 2065.84  3937.1 2064.81
  3951.3 2065.72  3994.0 2062.42  4057.5 2062.26  4086.0 2060.08  4112.5 2060.50
  4171.5 2059.32  4292.7 2057.88  4407.5 2056.91  4631.4 2055.19  4737.7 2055.68
  4815.5 2054.03  4823.0 2055.18  4829.7 2053.44  4891.4 2050.21  4984.2 2048.75
  4984.4 2048.25  4988.2 2048.75  5030.9 2049.76  5059.2 2053.50  5082.4 2053.00
  5092.7 2055.88  5100.5 2056.30  5164.9 2056.56  5188.1 2057.26  5206.1 2059.11
#Mann=8,-1,0
  3866.4    0.07       0  4112.5    0.16       0  4171.5    0.07       0
  4292.7    0.16       0  4407.5    0.07       0  4891.4   0.035       0
  4984.2   0.035       0  4988.2   0.035       0
Bank Sta=4984.2,4988.2
Exp/Cntr=0.3,0.1

Type RM Length L Ch R = 1,10890,580,580,580
BEGIN DESCRIPTION:
Plum Creek Trib3 17.0
END DESCRIPTION:
XS GIS Cut Line= 3
      1379110.89      6913915.34      1379205.00      6912838.00
      1379059.05      6912181.98
#Sta/Elev= 30
  3926.0 2057.26  4013.7 2055.66  4134.1 2056.41  4174.3 2054.18  4654.0 2052.65
  4726.4 2053.67  4814.4 2050.19  4887.0 2047.45  4907.1 2047.56  4912.4 2048.73
  4917.1 2049.77  4937.2 2049.95  4951.1 2047.79  5002.9 2046.74  5003.2 2046.24
  5006.9 2046.74  5031.8 2052.92  5038.2 2053.41  5118.8 2053.63  5150.9 2056.45
  5191.8 2055.94  5232.8 2059.34  5264.7 2058.51  5325.0 2062.56  5356.8 2061.58
  5407.0 2065.24  5449.0 2064.57  5509.4 2067.78  5579.5 2068.01  5679.5 2064.60
#Mann=6,-1,0
  3926.0   0.035       0  4654.0    0.07       0  4814.4   0.035       0
  4912.4    0.07       0  5002.9    0.07       0  5006.9    0.07       0
Bank Sta=5002.9,5006.9
Exp/Cntr=0.3,0.1

Type RM Length L Ch R = 1,10310,947,947,947
BEGIN DESCRIPTION:
Mapping XS 93d546f0
END DESCRIPTION:
XS GIS Cut Line= 4
      1379392.15      6913988.21      1379741.10      6912925.71
      1379642.15      6912613.21      1379001.55      6911884.07
#Sta/Elev= 30
  3545.1 2059.90  3776.1 2055.09  3798.9 2056.18  3857.3 2053.62  4016.3 2052.16
  4040.0 2053.52  4061.1 2051.89  4339.7 2049.94  4387.4 2051.41  4408.6 2049.88
  4567.7 2049.00  4576.8 2050.64  4640.4 2050.67  4839.4 2048.79  4944.2 2043.81
  4984.1 2043.68  4984.3 2043.18  4988.1 2043.68  5042.3 2043.84  5070.8 2050.78
  5091.7 2052.59  5156.2 2051.66  5254.9 2056.18  5326.0 2056.56  5361.2 2059.31
  5751.1 2059.35  5836.5 2060.20  5843.2 2061.62  5914.3 2058.84  5961.8 2060.79
#Mann=5,-1,0
  3545.1    0.07       0  3776.1   0.035       0  4640.4    0.07       0
  4984.1    0.07       0  4988.1    0.07       0
Bank Sta=4984.1,4988.1
Exp/Cntr=0.3,0.1

Type RM Length L Ch R = 1,9363,580,580,580
BEGIN DESCRIPTION:
Plum Creek Trib3 16.0
END DESCRIPTION:
XS GIS Cut Line= 3
      1379569.21      6913962.21      1380110.20      6912287.52
      1380241.10      6911347.59
#Sta/Elev= 30
  3240.1 2063.19  3273.0 2060.75  3452.4 2055.26  3496.7 2056.11  3566.5 2053.12
  3654.4 2053.74  3860.0 2050.23  3956.1 2051.54  3988.1 2049.42  4301.7 2048.67
  4715.8 2048.45  4873.9 2044.48  4957.5 2045.64  4978.5 2044.91  4996.8 2041.03
  5002.3 2043.38  5009.6 2040.54  5017.4 2040.12  5017.7 2039.62  5022.0 2040.12
  5060.1 2041.89  5090.4 2041.08  5130.8 2044.67  5171.2 2041.85  5282.2 2050.27
  5322.6 2049.79  5352.9 2051.82  5383.2 2050.63  5665.9 2054.17  5949.0 2059.32
#Mann=5,-1,0
  3240.1    0.07       0  3452.4   0.035       0  4301.7    0.07       0
  5017.4    0.07       0  5022.0    0.07       0
Bank Sta=5017.4,5022
Exp/Cntr=0.3,0.1

Type RM Length L Ch R = 1,8783,545,545,545
BEGIN DESCRIPTION:
Plum Creek Trib3 15.0
END DESCRIPTION:
XS GIS Cut Line= 3
      1379819.23      6913889.25      1380475.26      6912541.95
      1380704.99      6911438.04
#Sta/Elev= 30
  3513.2 2063.57  3579.6 2059.95  3636.9 2060.43  3803.8 2055.37  3848.3 2056.50
  3927.0 2052.86  3996.5 2053.88  4114.3 2050.17  4127.7 2050.44  4368.1 2048.19
  4616.3 2042.52  4661.4 2044.77  4723.5 2038.62  4796.7 2040.63  4804.8 2038.77
  4926.4 2038.53  4960.5 2041.70  5035.8 2037.08  5036.2 2036.58  5040.5 2037.08
  5083.1 2043.66  5107.7 2044.41  5673.8 2050.89  5700.1 2049.42  5741.0 2053.00
  5768.9 2051.84  5863.6 2056.69  5894.2 2055.72  5935.1 2060.35  6139.3 2065.60
#Mann=7,-1,0
  3513.2    0.07       0  3927.0   0.035       0  4114.3    0.07       0
  4127.7   0.035       0  4368.1    0.07       0  5035.8    0.07       0
  5040.5    0.07       0
Bank Sta=5035.8,5040.5
Exp/Cntr=0.3,0.1

Type RM Length L Ch R = 1,8238,448,448,448
BEGIN DESCRIPTION:
Plum Creek Trib3 14.0
END DESCRIPTION:
XS GIS Cut Line= 3
      1381204.64      6914436.11      1380855.00      6912688.00
      1380746.34      6911722.83
#Sta/Elev= 30
  3217.3 2056.91  3330.3 2055.29  3353.0 2056.16  3439.7 2052.50  3704.9 2048.69
  4200.1 2048.71  4300.4 2047.48  4347.4 2048.45  4362.1 2046.58  4400.8 2044.23
  4722.1 2042.73  4918.5 2043.04  4938.8 2041.87  4969.4 2035.18  4994.8 2035.02
  4995.2 2034.52  5000.2 2035.02  5070.5 2039.89  5219.9 2039.27  5287.5 2042.57
  5412.6 2043.22  5462.9 2046.10  5489.9 2044.91  5704.5 2046.92  5767.7 2049.41
  5825.2 2050.11  5855.4 2052.88  5895.7 2052.17  5939.8 2056.11  5971.3 2054.84
#Mann=12,-1,0
  3217.3    0.05       0  3330.3   0.035       0  3353.0    0.05       0
  4200.1   0.035       0  4300.4    0.05       0  4362.1   0.035       0
  4400.8    0.05       0  4722.1    0.07       0  4994.8    0.07       0
  5000.2    0.07       0  5287.5   0.045       0  5767.7    0.07       0
Bank Sta=4994.8,5000.2
Exp/Cntr=0.3,0.1

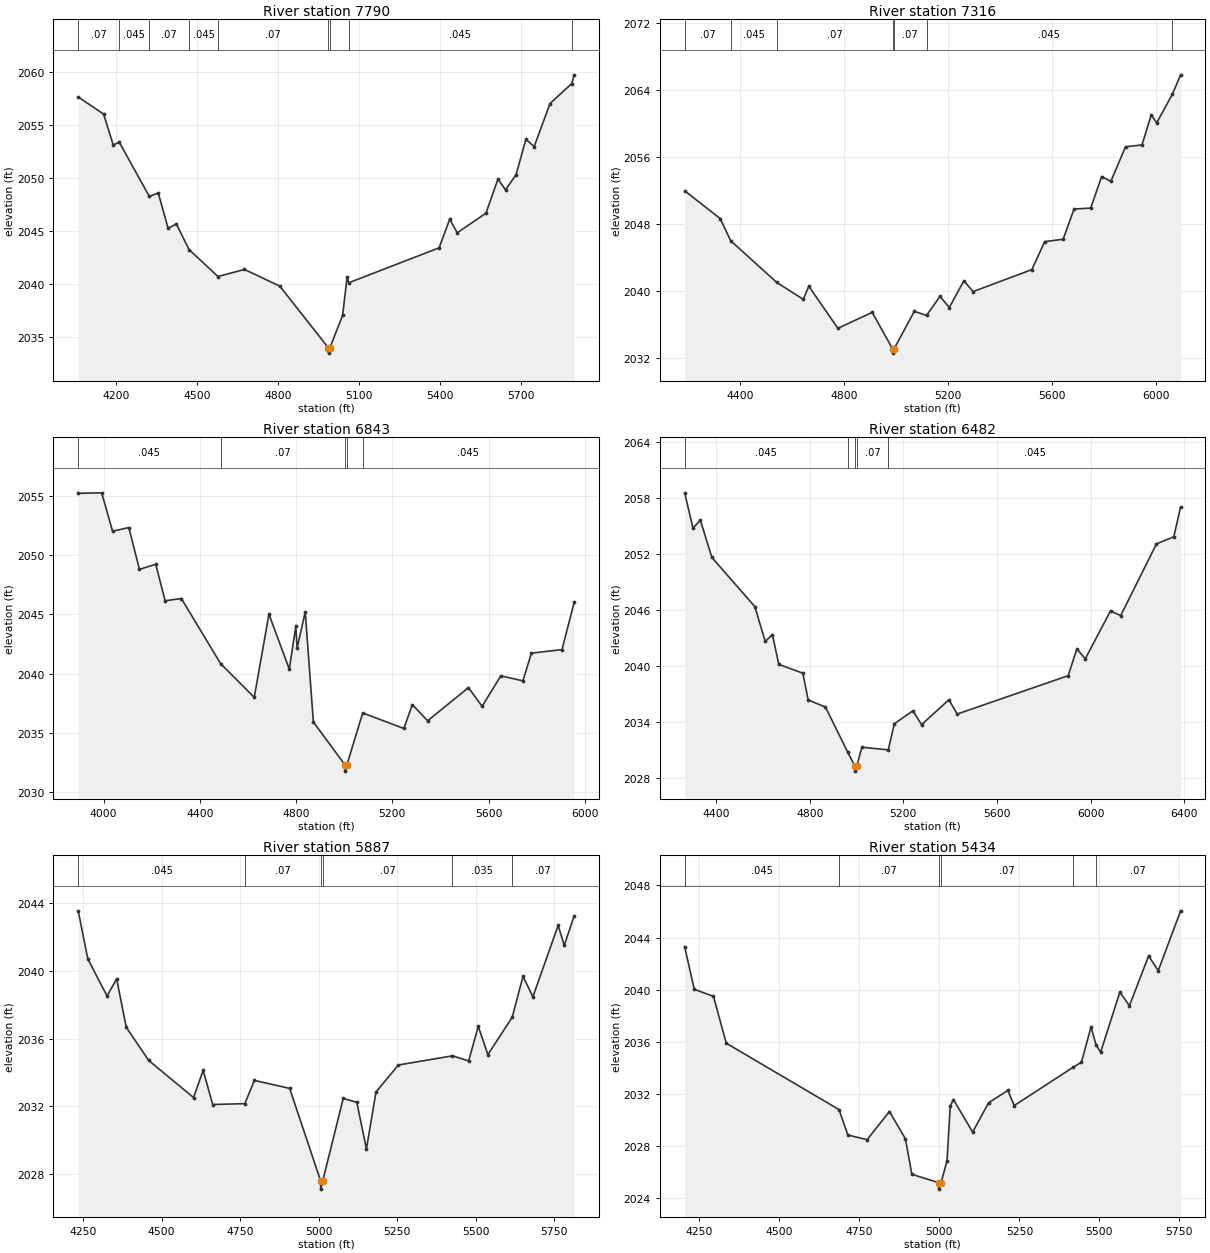
Type RM Length L Ch R = 1,7790,474,474,474
BEGIN DESCRIPTION:
Plum Creek Trib3 13.0
END DESCRIPTION:
XS GIS Cut Line= 3
      1381705.00      6913238.00      1381205.00      6912438.00
      1380805.01      6911638.02
#Sta/Elev= 30
  4060.8 2057.62  4155.1 2056.00  4190.5 2053.09  4213.2 2053.34  4324.3 2048.23
  4357.4 2048.56  4393.9 2045.23  4424.6 2045.63  4471.4 2043.22  4578.7 2040.67
  4677.0 2041.34  4807.9 2039.76  4987.9 2033.94  4988.3 2033.44  4993.4 2033.94
  5040.5 2037.00  5057.3 2040.63  5063.0 2040.08  5398.3 2043.38  5437.4 2046.08
  5465.4 2044.80  5571.6 2046.65  5616.3 2049.87  5644.3 2048.85  5683.4 2050.29
  5719.7 2053.62  5750.5 2052.94  5809.2 2057.00  5889.8 2058.89  5898.6 2059.71
#Mann=9,-1,0
  4060.8    0.07       0  4213.2   0.045       0  4324.3    0.07       0
  4471.4   0.045       0  4578.7    0.07       0  4987.9    0.07       0
  4993.4    0.07       0  5063.0   0.045       0  5889.8    0.07       0
Bank Sta=4987.9,4993.4
Exp/Cntr=0.3,0.1

Type RM Length L Ch R = 1,7316,473,473,473
BEGIN DESCRIPTION:
Plum Creek Trib3 12.0
END DESCRIPTION:
XS GIS Cut Line= 3
      1381755.01      6913038.04      1381605.00      6912238.00
      1380804.98      6911487.98
#Sta/Elev= 30
  4186.0 2051.96  4322.6 2048.65  4363.3 2046.00  4540.1 2041.05  4643.0 2039.01
  4664.2 2040.58  4776.2 2035.56  4908.4 2037.46  4987.1 2033.10  4987.5 2032.60
  4992.6 2033.10  5070.6 2037.58  5117.8 2037.10  5169.7 2039.37  5205.4 2038.04
  5261.6 2041.23  5297.2 2039.94  5523.4 2042.56  5573.2 2045.90  5644.0 2046.18
  5686.0 2049.78  5750.0 2049.90  5792.5 2053.66  5827.7 2053.08  5884.3 2057.21
  5947.8 2057.43  5983.5 2061.01  6004.5 2060.06  6064.6 2063.46  6096.6 2065.79
#Mann=7,-1,0
  4186.0    0.07       0  4363.3   0.045       0  4540.1    0.07       0
  4987.1    0.07       0  4992.6    0.07       0  5117.8   0.045       0
  6064.6    0.07       0
Bank Sta=4987.1,4992.6
Exp/Cntr=0.3,0.1

Type RM Length L Ch R = 1,6843,361,361,361
BEGIN DESCRIPTION:
Plum Creek Trib3 11.0
END DESCRIPTION:
XS GIS Cut Line= 3
      1382308.82      6913201.77      1382005.00      6912138.00
      1381334.83      6911456.94
#Sta/Elev= 30
  3894.1 2055.21  3991.6 2055.25  4036.9 2052.01  4104.5 2052.32  4148.8 2048.79
  4216.4 2049.22  4255.4 2046.14  4323.0 2046.33  4486.1 2040.83  4626.0 2037.99
  4687.0 2045.01  4771.6 2040.37  4798.9 2043.99  4804.1 2042.13  4837.9 2045.20
  4871.7 2035.91  5004.1 2032.26  5004.6 2031.76  5010.8 2032.26  5076.8 2036.67
  5247.9 2035.36  5283.2 2037.37  5346.9 2036.01  5516.6 2038.81  5573.2 2037.23
  5650.9 2039.80  5742.9 2039.38  5778.2 2041.72  5905.5 2042.02  5955.9 2046.01
#Mann=5,-1,0
  3894.1   0.045       0  4486.1    0.07       0  5004.1    0.07       0
  5010.8    0.07       0  5076.8   0.045       0
Bank Sta=5004.1,5010.8
Exp/Cntr=0.3,0.1

Type RM Length L Ch R = 1,6482,595,595,595
BEGIN DESCRIPTION:
Plum Creek Trib3 10.0
END DESCRIPTION:
XS GIS Cut Line= 3
      1382655.00      6912587.99      1382294.52      6911947.80
      1381105.00      6911238.00
#Sta/Elev= 30
  4265.3 2058.54  4300.7 2054.77  4332.5 2055.60  4381.6 2051.61  4565.1 2046.35
  4609.6 2042.61  4640.3 2043.35  4667.7 2040.15  4770.3 2039.21  4793.2 2036.34
  4867.2 2035.57  4962.2 2030.74  4993.6 2029.21  4994.1 2028.71  5000.5 2029.21
  5022.7 2031.27  5135.7 2030.99  5161.1 2033.78  5240.9 2035.18  5277.8 2033.69
  5394.6 2036.36  5430.3 2034.83  5904.5 2038.94  5941.5 2041.80  5977.6 2040.75
  6085.5 2045.88  6129.0 2045.38  6282.0 2053.07  6356.0 2053.83  6385.2 2057.03
#Mann=5,-1,0
  4265.3   0.045       0  4962.2    0.07       0  4993.6    0.07       0
  5000.5    0.07       0  5135.7   0.045       0
Bank Sta=4993.6,5000.5
Exp/Cntr=0.3,0.1

Type RM Length L Ch R = 1,5887,453,453,453
BEGIN DESCRIPTION:
Plum Creek Trib3 9.0
END DESCRIPTION:
XS GIS Cut Line= 3
      1382605.00      6912188.00      1382455.00      6911438.00
      1382605.00      6910637.99
#Sta/Elev= 30
  4234.7 2043.53  4265.3 2040.69  4326.5 2038.51  4357.1 2039.52  4387.7 2036.66
  4459.1 2034.71  4601.8 2032.52  4632.4 2034.12  4663.0 2032.11  4765.1 2032.16
  4795.6 2033.53  4907.8 2033.06  5006.2 2027.62  5006.7 2027.12  5013.3 2027.62
  5078.4 2032.47  5121.6 2032.24  5152.2 2029.49  5182.7 2032.85  5253.9 2034.44
  5426.2 2034.98  5477.7 2034.68  5508.3 2036.72  5538.8 2035.05  5616.2 2037.25
  5650.7 2039.67  5682.1 2038.46  5762.6 2042.67  5782.1 2041.49  5813.5 2043.24
#Mann=6,-1,0
  4234.7   0.045       0  4765.1    0.07       0  5006.2    0.07       0
  5013.3    0.07       0  5426.2   0.035       0  5616.2    0.07       0
Bank Sta=5006.2,5013.3
Exp/Cntr=0.3,0.1

Type RM Length L Ch R = 1,5434,585,585,585
BEGIN DESCRIPTION:
Plum Creek Trib3 8.0
END DESCRIPTION:
XS GIS Cut Line= 3
      1382855.00      6912188.04      1382855.00      6911388.00
      1382855.00      6910638.04
#Sta/Elev= 30
  4203.9 2043.28  4233.9 2040.02  4293.9 2039.48  4333.9 2035.88  4686.2 2030.78
  4713.9 2028.83  4773.9 2028.47  4843.9 2030.63  4893.9 2028.53  4913.9 2025.81
  4997.5 2025.17  4998.0 2024.67  5005.3 2025.17  5023.9 2026.86  5033.9 2031.06
  5043.9 2031.55  5103.9 2029.05  5153.9 2031.31  5213.9 2032.25  5233.9 2031.09
  5417.8 2034.03  5443.9 2034.42  5473.9 2037.13  5489.3 2035.77  5503.9 2035.19
  5563.9 2039.80  5593.9 2038.76  5653.9 2042.59  5683.9 2041.45  5753.9 2046.05
#Mann=6,-1,0
  4203.9   0.045       0  4686.2    0.07       0  4997.5    0.07       0
  5005.3    0.07       0  5417.8   0.035       0  5489.3    0.07       0
Bank Sta=4997.5,5005.3
Exp/Cntr=0.3,0.1

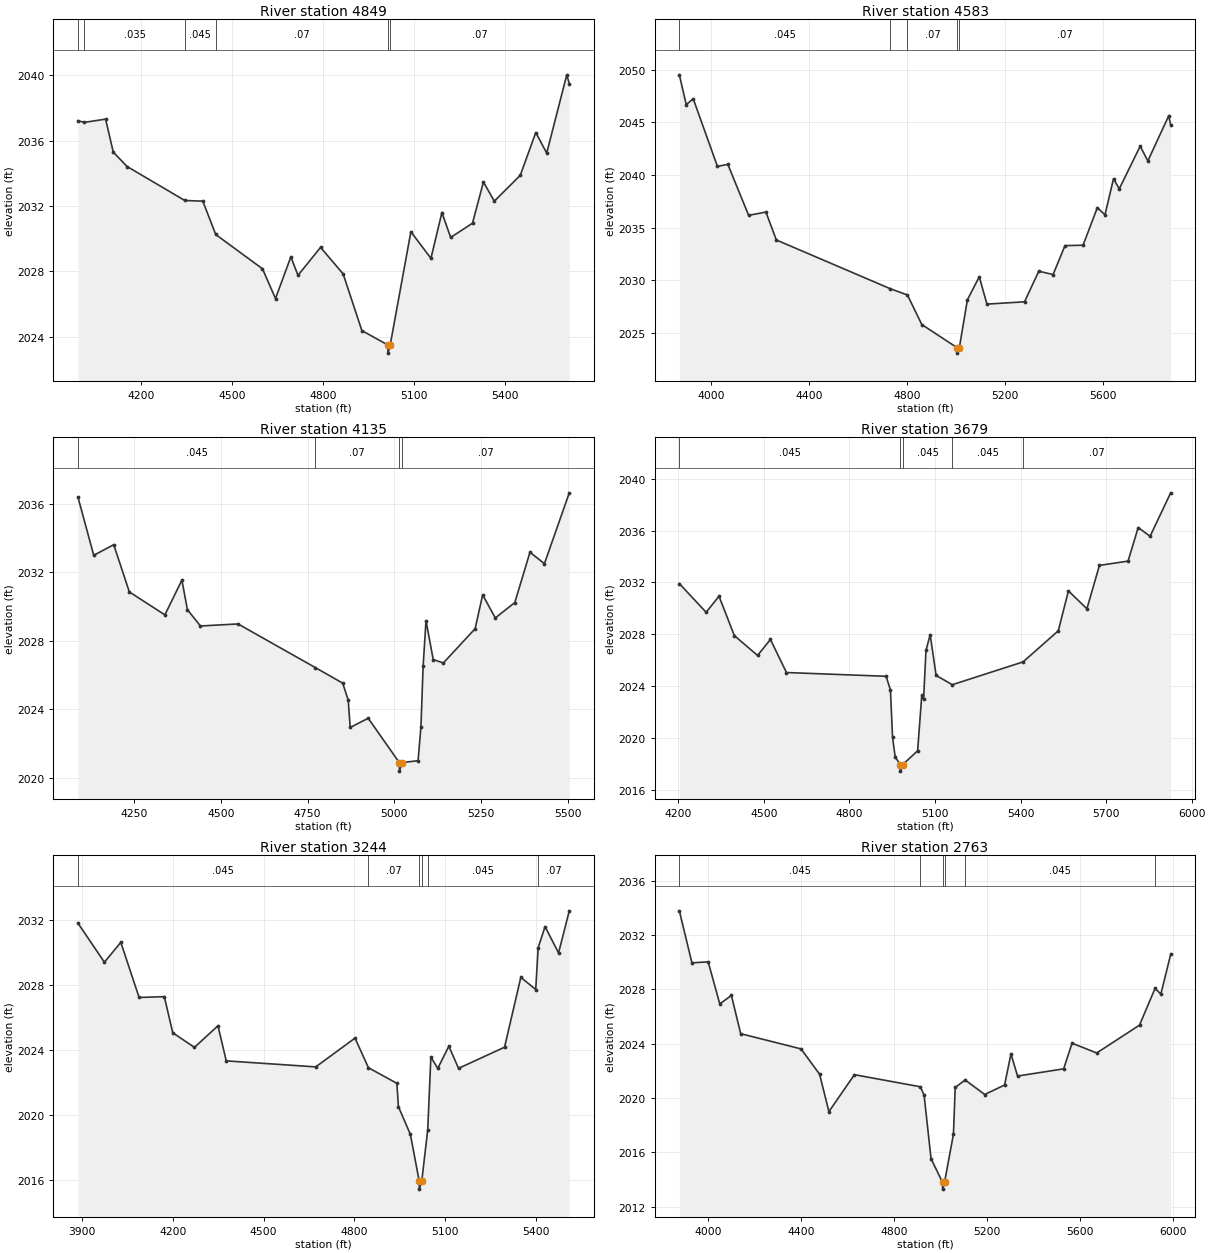
Type RM Length L Ch R = 1,4849,266,266,266
BEGIN DESCRIPTION:
Plum Creek Trib3 7.0
END DESCRIPTION:
XS GIS Cut Line= 3
      1383600.47      6912290.26      1383256.25      6911341.36
      1382918.17      6910831.94
#Sta/Elev= 30
  3990.6 2037.21  4012.0 2037.11  4081.7 2037.31  4107.0 2035.29  4152.6 2034.41
  4343.0 2032.33  4402.5 2032.29  4444.9 2030.25  4599.3 2028.15  4642.2 2026.33
  4692.8 2028.88  4716.4 2027.75  4790.8 2029.46  4865.3 2027.84  4927.1 2024.37
  5012.7 2023.49  5013.2 2022.99  5020.6 2023.49  5088.8 2030.42  5155.0 2028.79
  5191.1 2031.59  5220.1 2030.07  5292.1 2030.94  5328.1 2033.46  5364.1 2032.29
  5449.7 2033.87  5500.8 2036.49  5536.9 2035.23  5603.1 2040.02  5611.4 2039.48
#Mann=6,-1,0
  3990.6   0.045       0  4012.0   0.035       0  4343.0   0.045       0
  4444.9    0.07       0  5012.7    0.07       0  5020.6    0.07       0
Bank Sta=5012.7,5020.6
Exp/Cntr=0.3,0.1

Type RM Length L Ch R = 1,4583,448,448,448
BEGIN DESCRIPTION:
Plum Creek Trib3 6.0
END DESCRIPTION:
XS GIS Cut Line= 3
      1384304.97      6912187.97      1383505.00      6911388.00
      1383054.98      6910637.97
#Sta/Elev= 30
  3869.4 2049.52  3897.6 2046.68  3925.9 2047.25  4024.9 2040.81  4067.3 2041.01
  4152.2 2036.16  4222.9 2036.47  4265.3 2033.82  4729.9 2029.19  4800.6 2028.59
  4859.3 2025.78  5004.5 2023.56  5005.0 2023.06  5012.5 2023.56  5045.4 2028.13
  5094.0 2030.32  5125.1 2027.72  5278.7 2027.94  5337.0 2030.85  5395.3 2030.53
  5443.9 2033.28  5517.7 2033.32  5576.0 2036.89  5607.1 2036.21  5642.1 2039.64
  5665.5 2038.68  5751.0 2042.74  5782.1 2041.33  5867.6 2045.63  5875.4 2044.75
#Mann=5,-1,0
  3869.4   0.045       0  4729.9   0.035       0  4800.6    0.07       0
  5004.5    0.07       0  5012.5    0.07       0
Bank Sta=5004.5,5012.5
Exp/Cntr=0.3,0.1

Type RM Length L Ch R = 1,4135,456,456,456
BEGIN DESCRIPTION:
Plum Creek Trib3 5.0
END DESCRIPTION:
XS GIS Cut Line= 3
      1384154.98      6911837.97      1383705.00      6911038.00
      1383305.03      6910738.03
#Sta/Elev= 30
  4087.3 2036.39  4132.8 2033.00  4190.5 2033.62  4235.5 2030.86  4338.1 2029.52
  4387.2 2031.55  4403.1 2029.82  4440.7 2028.87  4549.1 2028.99  4772.2 2026.44
  4851.2 2025.53  4867.1 2024.54  4872.9 2022.94  4924.8 2023.48  5014.5 2020.89
  5015.0 2020.39  5022.9 2020.89  5068.7 2021.00  5077.0 2022.98  5083.3 2026.52
  5091.6 2029.18  5112.4 2026.91  5141.6 2026.71  5233.3 2028.71  5255.1 2030.69
  5291.6 2029.34  5347.9 2030.24  5391.6 2033.18  5433.3 2032.51  5505.1 2036.65
#Mann=4,-1,0
  4087.3   0.045       0  4772.2    0.07       0  5014.5    0.07       0
  5022.9    0.07       0
Bank Sta=5014.5,5022.9
Exp/Cntr=0.3,0.1

Type RM Length L Ch R = 1,3679,435,435,435
BEGIN DESCRIPTION:
Plum Creek Trib3 4.0
END DESCRIPTION:
XS GIS Cut Line= 3
      1384470.28      6911691.36      1384105.00      6910988.00
      1383555.01      6910238.01
#Sta/Elev= 30
  4203.8 2031.91  4297.7 2029.70  4342.8 2030.94  4396.6 2027.90  4478.0 2026.37
  4523.1 2027.60  4579.4 2025.05  4928.7 2024.76  4943.9 2023.70  4951.3 2020.04
  4960.4 2018.55  4978.2 2017.94  4978.7 2017.44  4986.8 2017.94  5039.2 2019.01
  5053.8 2023.31  5060.0 2022.97  5068.5 2026.76  5083.2 2027.97  5104.0 2024.83
  5160.7 2024.11  5408.8 2025.87  5532.4 2028.27  5567.9 2031.35  5632.7 2029.97
  5676.7 2033.32  5777.0 2033.65  5812.5 2036.24  5854.3 2035.57  5926.4 2038.92
#Mann=5,-1,0
  4203.8   0.045       0  4978.2    0.07       0  4986.8   0.045       0
  5160.7   0.045       0  5408.8    0.07       0
Bank Sta=4978.2,4986.8
Exp/Cntr=0.3,0.1

Type RM Length L Ch R = 1,3244,481,481,481
BEGIN DESCRIPTION:
Plum Creek Trib3 3.0
END DESCRIPTION:
XS GIS Cut Line= 3
      1384569.22      6911701.73      1384255.00      6910638.00
      1383804.96      6910387.98
#Sta/Elev= 30
  3886.2 2031.80  3973.5 2029.40  4027.8 2030.62  4088.2 2027.23  4171.6 2027.28
  4199.4 2025.06  4271.2 2024.16  4348.9 2025.49  4376.3 2023.33  4672.1 2022.96
  4801.9 2024.73  4846.2 2022.91  4940.2 2021.95  4945.4 2020.51  4984.9 2018.81
  5014.0 2015.94  5014.5 2015.44  5022.6 2015.94  5042.3 2019.10  5052.6 2023.56
  5075.5 2022.87  5112.1 2024.23  5144.1 2022.87  5296.2 2024.17  5350.0 2028.47
  5399.2 2027.72  5407.3 2030.29  5430.1 2031.59  5474.7 2029.97  5510.2 2032.56
#Mann=6,-1,0
  3886.2   0.045       0  4846.2    0.07       0  5014.0    0.07       0
  5022.6    0.07       0  5042.3   0.045       0  5407.3    0.07       0
Bank Sta=5014,5022.6
Exp/Cntr=0.3,0.1

Type RM Length L Ch R = 1,2763,570,570,570
BEGIN DESCRIPTION:
Plum Creek Trib3 2.0
END DESCRIPTION:
XS GIS Cut Line= 3
      1384631.73      6911712.13      1384655.00      6910588.00
      1384005.03      6909838.03
#Sta/Elev= 30
  3875.1 2033.78  3929.2 2029.95  3999.3 2030.02  4049.3 2026.92  4099.3 2027.55
  4139.3 2024.73  4399.3 2023.61  4479.4 2021.74  4519.4 2018.99  4629.4 2021.71
  4913.2 2020.82  4929.5 2020.21  4959.5 2015.52  5008.9 2013.78  5009.4 2013.28
  5017.6 2013.78  5056.0 2017.33  5063.6 2020.77  5106.5 2021.32  5190.8 2020.25
  5276.3 2020.95  5303.8 2023.24  5332.3 2021.61  5530.8 2022.14  5567.0 2024.03
  5673.3 2023.31  5857.6 2025.36  5924.5 2028.06  5949.7 2027.65  5991.9 2030.57
#Mann=6,-1,0
  3875.1   0.045       0  4913.2    0.07       0  5008.9    0.07       0
  5017.6    0.07       0  5106.5   0.045       0  5924.5   0.035       0
Bank Sta=5008.9,5017.6
Exp/Cntr=0.3,0.1

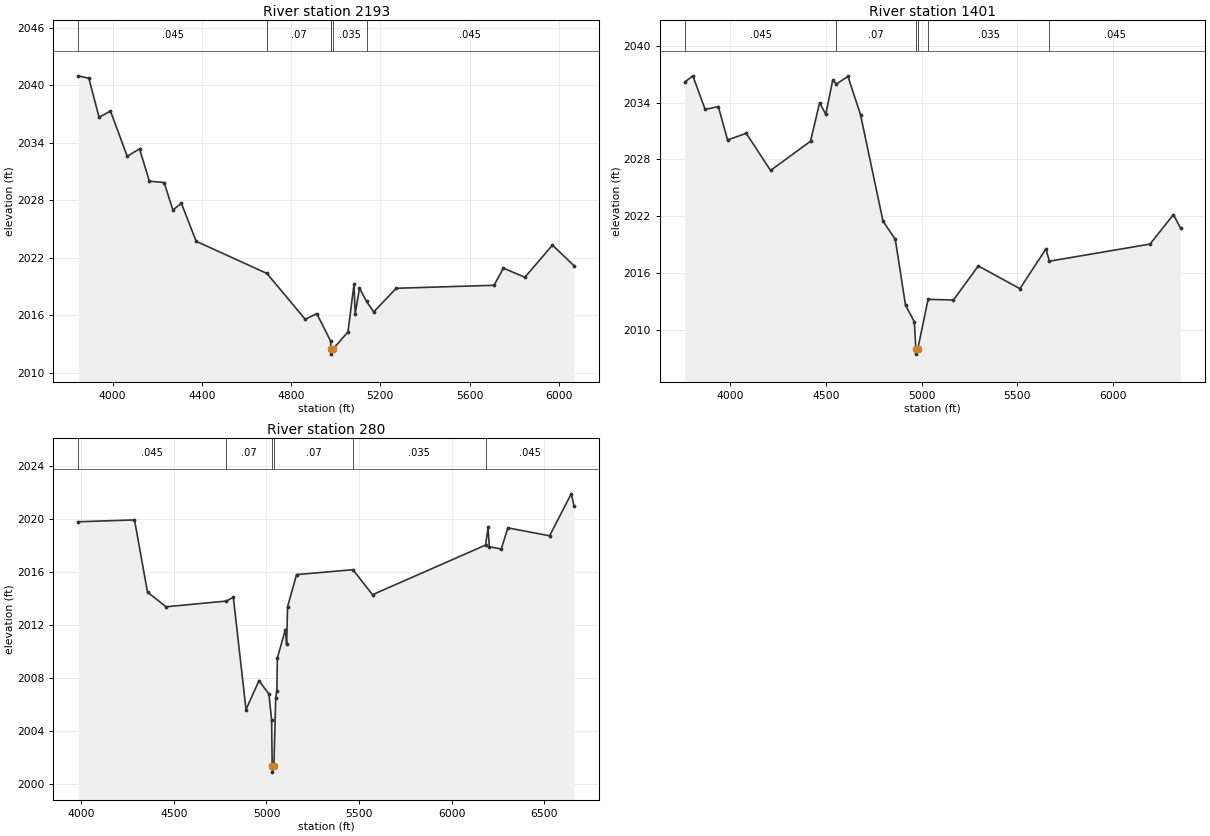
Type RM Length L Ch R = 1,2193,792,792,792
BEGIN DESCRIPTION:
Mapping XS 19caf444
END DESCRIPTION:
XS GIS Cut Line= 3
      1384590.07      6911956.94      1385079.65      6910910.08
      1384824.43      6909873.61
#Sta/Elev= 30
  3845.9 2040.99  3893.7 2040.73  3939.4 2036.67  3990.6 2037.31  4065.5 2032.60
  4120.7 2033.37  4164.9 2030.00  4231.1 2029.86  4270.2 2026.99  4308.4 2027.69
  4374.6 2023.73  4691.6 2020.38  4863.3 2015.60  4915.6 2016.18  4977.4 2013.32
  4978.7 2012.46  4979.2 2011.96  4987.5 2012.46  5055.2 2014.29  5082.3 2019.26
  5087.5 2016.16  5106.7 2018.84  5138.2 2017.47  5170.5 2016.36  5271.5 2018.83
  5710.1 2019.14  5751.7 2020.93  5848.2 2019.98  5971.8 2023.33  6069.0 2021.17
#Mann=6,-1,0
  3845.9   0.045       0  4691.6    0.07       0  4977.4   0.035       0
  4978.7   0.035       0  4987.5   0.035       0  5138.2   0.045       0
Bank Sta=4978.7,4987.5
Exp/Cntr=0.3,0.1

Type RM Length L Ch R = 1,1401,1121,1121,1121
BEGIN DESCRIPTION:
Mapping XS 6fe94da8
END DESCRIPTION:
XS GIS Cut Line= 3
      1386131.72      6912107.98      1385704.65      6910972.58
      1384954.62      6909816.30
#Sta/Elev= 30
  3762.2 2036.16  3804.9 2036.83  3869.0 2033.28  3938.0 2033.58  3986.5 2030.05
  4083.8 2030.76  4210.9 2026.83  4419.8 2029.92  4467.3 2033.99  4499.4 2032.76
  4535.4 2036.34  4555.2 2035.98  4615.4 2036.76  4681.2 2032.70  4798.5 2021.47
  4862.6 2019.56  4916.1 2012.59  4962.1 2010.84  4970.3 2007.92  4970.8 2007.42
  4979.7 2007.92  5034.0 2013.21  5166.5 2013.14  5296.4 2016.74  5513.9 2014.34
  5649.8 2018.55  5667.7 2017.24  6193.6 2019.05  6315.7 2022.16  6353.5 2020.72
#Mann=6,-1,0
  3762.2   0.045       0  4555.2    0.07       0  4970.3    0.07       0
  4979.7    0.07       0  5034.0   0.035       0  5667.7   0.045       0
Bank Sta=4970.3,4979.7
Exp/Cntr=0.3,0.1

Type RM Length L Ch R = 1,280,0,0,0
BEGIN DESCRIPTION:
Plum Creek Trib3 1.0
END DESCRIPTION:
XS GIS Cut Line= 6
      1386402.56      6911550.70      1386476.29      6910720.00
      1386475.08      6910537.47      1386437.23      6910492.14
      1385983.32      6910399.23      1385023.20      6909786.87
#Sta/Elev= 30
  3983.5 2019.79  4287.4 2019.93  4357.7 2014.47  4458.1 2013.37  4783.4 2013.80
  4821.0 2014.09  4889.5 2005.61  4959.5 2007.79  5013.4 2006.77  5027.7 2004.82
  5030.8 2001.38  5031.3 2000.88  5040.3 2001.38  5049.8 2006.49  5056.3 2007.04
  5058.5 2009.48  5102.0 2011.65  5108.8 2010.56  5113.9 2013.38  5162.4 2015.80
  5466.7 2016.17  5572.5 2014.28  6182.9 2018.03  6196.5 2019.36  6203.0 2017.90
  6267.7 2017.73  6303.2 2019.33  6528.6 2018.73  6645.5 2021.90  6661.2 2020.96
#Mann=6,-1,0
  3983.5   0.045       0  4783.4    0.07       0  5030.8    0.07       0
  5040.3    0.07       0  5466.7   0.035       0  6182.9   0.045       0
Bank Sta=5030.8,5040.3
Exp/Cntr=0.3,0.1

Chan Stop Cuts=-1