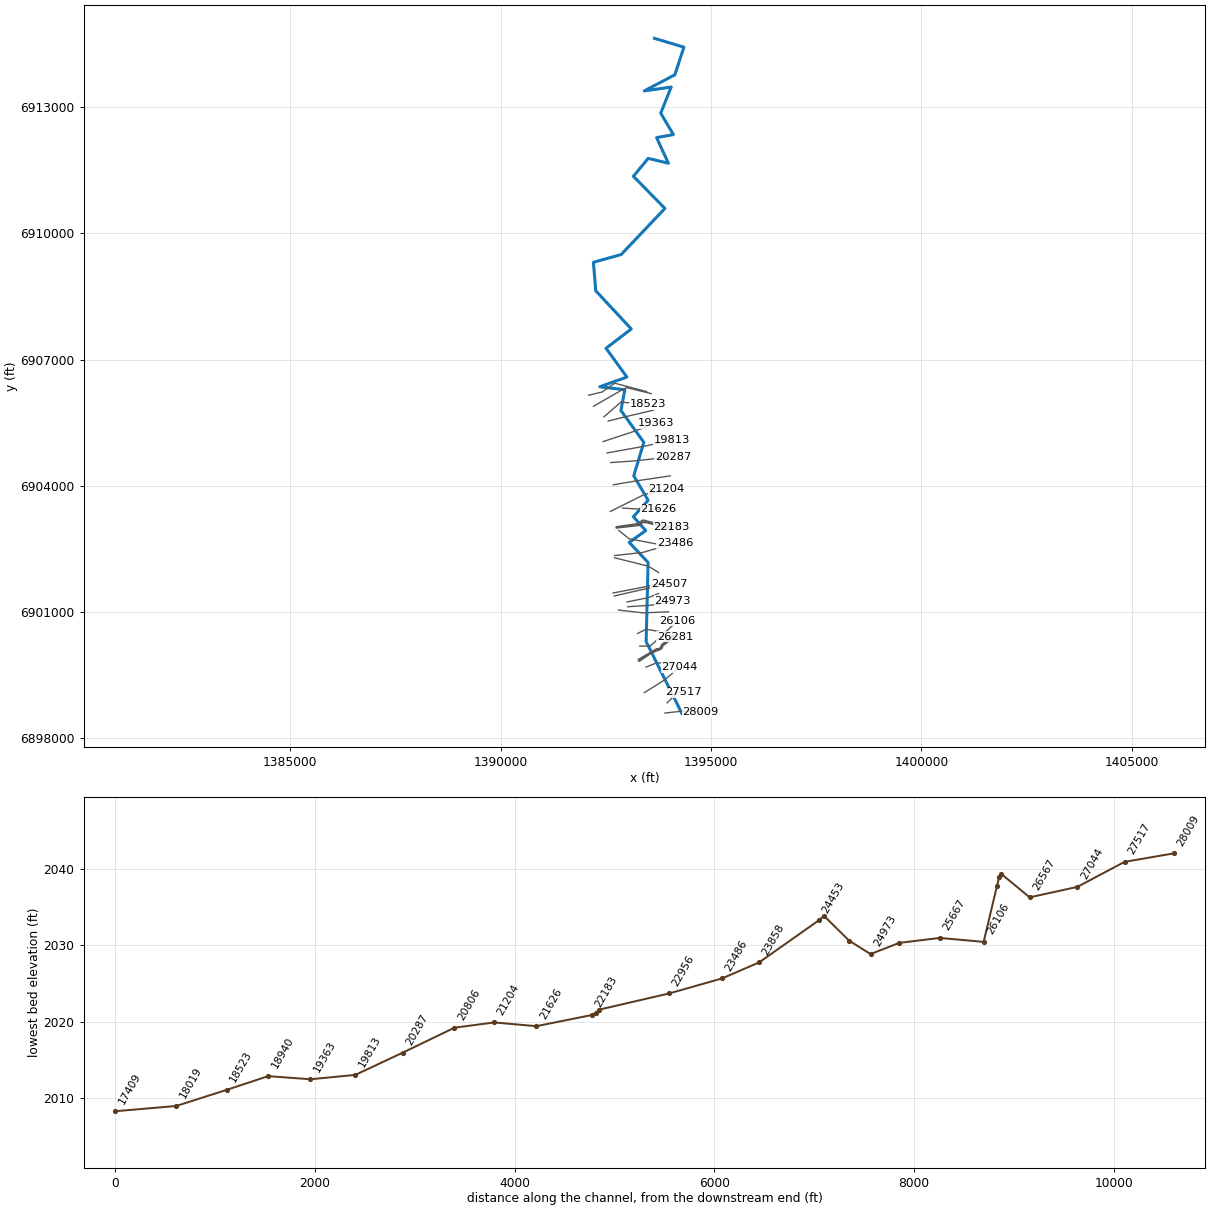
--- Plum Creek Trib4.prj (project) ---

Proj Title=Plum Creek Trib4 Base Level Engineering
Current Plan=p01
Default Exp/Contr=0.3,0.1
English Units
Geom File=g01
Flow File=f01
Plan File=p01
BEGIN DESCRIPTION:
Plum Creek Trib4
END DESCRIPTION:

--- Plum Creek Trib4.p01 (plan) ---

Plan Title=Multiple Run
Short Identifier=Multiple
Geom File=g01
Flow File=f01
Subcritical Flow
K Sum by GR= 0
Std Step Tol= 0.01
Critical Tol= 0.01
Num of Std Step Trials= 20
Max Error Tol= 0.3
Flow Tol Ratio= 0.001
Split Flow NTrial= 30
Split Flow Tol= 0.02
Split Flow Ratio= 0.02
Log Output Level= 0
Friction Slope Method= 1
Unsteady Friction Slope Method= 2
Unsteady Bridges Friction Slope Method= 1
Parabolic Critical Depth
Global Vel Dist=  1 , 1 , 1
Global Log Level= 0
CheckData=True
Encroach Param= -1, 0, 0, 0
BEGIN DESCRIPTION:
Multiple Run
END DESCRIPTION:

--- Plum Creek Trib4.f01 (steady flow) ---

Flow Title=Multiple
Number of Profiles=7
Profile Names=10-year,25-year,50-year,1pct_min,100-year,1pct_plu,500-year
River Rch & RM= Plum Creek Trib4,Reach-1,28009
     247     349     435     270     539    1076     839
River Rch & RM= Plum Creek Trib4,Reach-1,27517
     406     592     752     476     949    1893    1529
River Rch & RM= Plum Creek Trib4,Reach-1,26281
     555     820    1053     672    1341    2675    2201
River Rch & RM= Plum Creek Trib4,Reach-1,24758
     791    1180    1524     976    1948    3887    3225
River Rch & RM= Plum Creek Trib4,Reach-1,17409
     768    1140    1467     936    1868    3727    3069
River Rch & RM= Plum Creek Trib4,Reach-1,12583
     898    1337    1723    1100    2195    4379    3611
River Rch & RM= Plum Creek Trib4,Reach-1,3472
     881    1306    1680    1070    2135    4260    3495
Boundary for River Rch & Prof#=Plum Creek Trib4,Reach-1,1
Up Type=0
Dn Type=3
Dn Slope=0.005
Boundary for River Rch & Prof#=Plum Creek Trib4,Reach-1,2
Up Type=0
Dn Type=3
Dn Slope=0.005
Boundary for River Rch & Prof#=Plum Creek Trib4,Reach-1,3
Up Type=0
Dn Type=3
Dn Slope=0.005
Boundary for River Rch & Prof#=Plum Creek Trib4,Reach-1,4
Up Type=0
Dn Type=3
Dn Slope=0.005
Boundary for River Rch & Prof#=Plum Creek Trib4,Reach-1,5
Up Type=0
Dn Type=3
Dn Slope=0.005
Boundary for River Rch & Prof#=Plum Creek Trib4,Reach-1,6
Up Type=0
Dn Type=3
Dn Slope=0.005
Boundary for River Rch & Prof#=Plum Creek Trib4,Reach-1,7
Up Type=0
Dn Type=3
Dn Slope=0.005

--- Plum Creek Trib4.g01 (geometry) ---

Geom Title=Existing Conditions

River Reach=Plum Creek Trib4,Reach-1
Reach XY= 30
      1394305.00      6898588.00      1393457.06      6900293.85
      1393503.78      6902177.50      1393055.24      6902653.22
      1393447.35      6902934.30      1393154.41      6903263.01
      1393504.97      6903653.42      1393162.56      6904238.00
      1393402.95      6905032.14      1392858.47      6905789.50
      1392950.28      6906282.38      1392355.36      6906353.27
      1392999.53      6906584.98      1392504.78      6907267.95
      1393103.96      6907727.56      1392260.13      6908635.42
      1392204.50      6909312.99      1392864.68      6909498.17
      1393903.03      6910593.63      1393154.52      6911358.46
      1393506.25      6911784.49      1393985.78      6911667.41
      1393705.97      6912277.73      1394104.50      6912349.62
      1393804.45      6912858.14      1394052.03      6913479.69
      1393412.31      6913387.90      1394138.76      6913770.76
      1394354.25      6914427.32      1393655.00      6914638.00

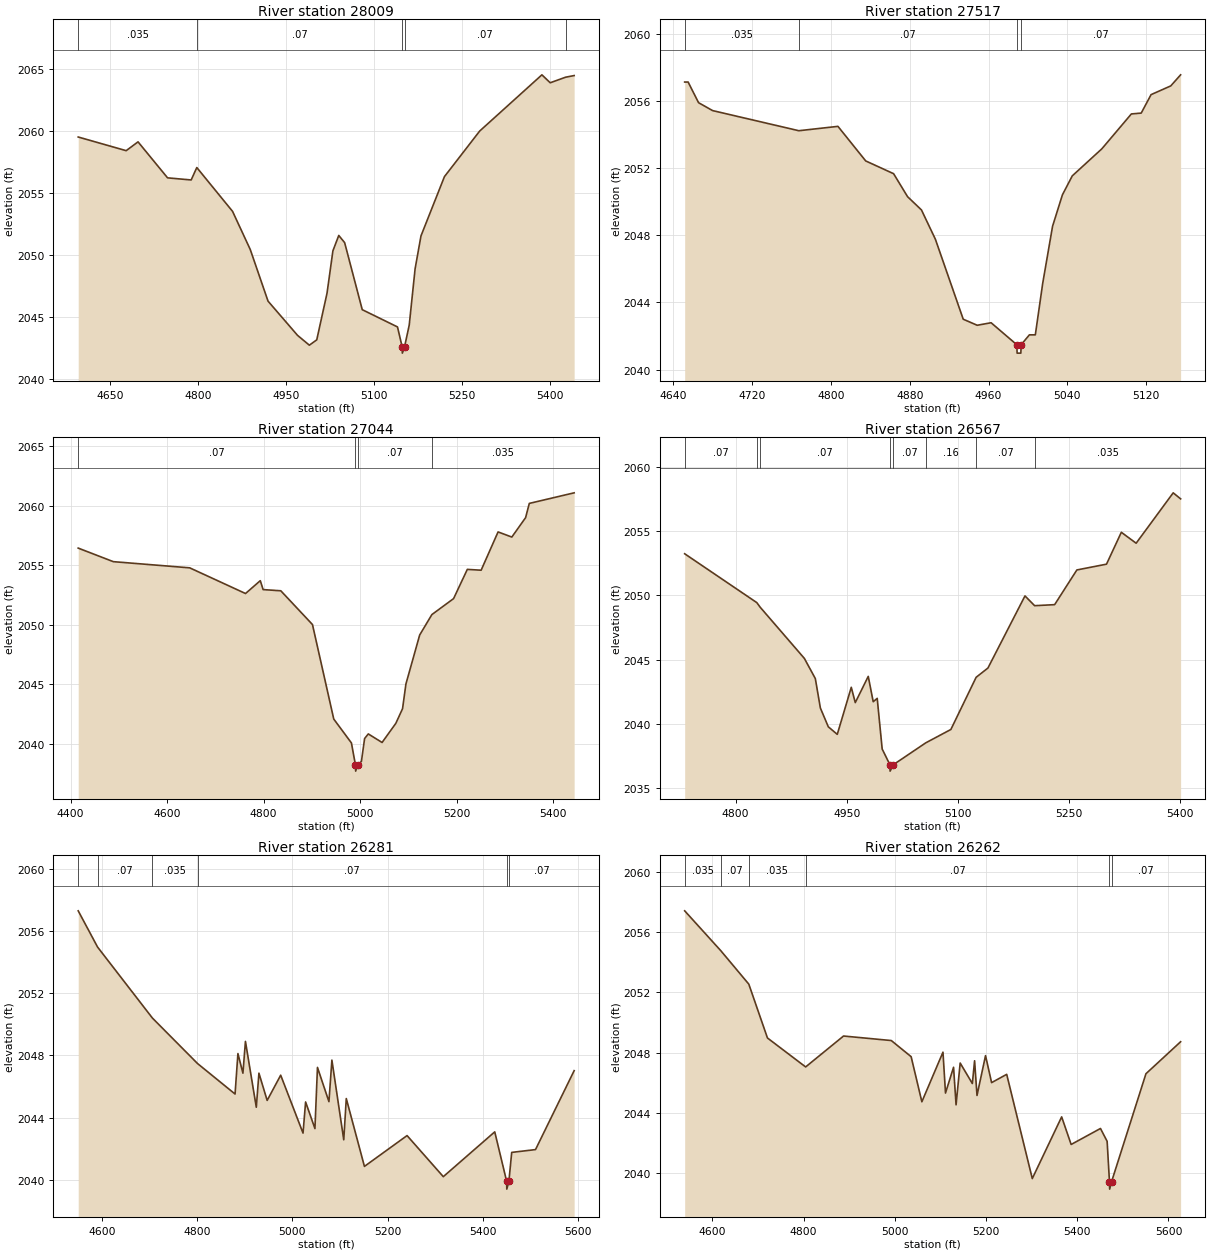
Type RM Length L Ch R = 1,28009,492,492,492
BEGIN DESCRIPTION:
Plum Creek Trib4 42.0
END DESCRIPTION:
XS GIS Cut Line= 3
      1393903.79      6898595.05      1394305.01      6898640.62
      1394745.83      6898631.94
#Sta/Elev= 30
  4596.2 2059.50  4677.9 2058.40  4698.1 2059.11  4748.4 2056.21  4788.6 2056.04
  4798.2 2057.04  4859.1 2053.51  4889.3 2050.43  4919.5 2046.28  4969.8 2043.52
  4989.9 2042.73  5002.5 2043.16  5020.0 2046.92  5030.0 2050.33  5040.0 2051.57
  5050.0 2050.99  5080.0 2045.59  5140.0 2044.20  5148.0 2042.59  5148.3 2042.09
  5152.0 2042.59  5160.0 2044.35  5170.0 2048.88  5180.0 2051.53  5220.0 2056.31
  5280.0 2059.98  5386.0 2064.51  5400.1 2063.87  5426.5 2064.32  5440.9 2064.45
#Mann=5,-1,0
  4596.2   0.035       0  4798.2    0.07       0  5148.0    0.07       0
  5152.0    0.07       0  5426.5   0.035       0
Bank Sta=5148,5152
Exp/Cntr=0.3,0.1

Type RM Length L Ch R = 1,27517,473,473,473
BEGIN DESCRIPTION:
Plum Creek Trib4 41.0
END DESCRIPTION:
XS GIS Cut Line= 3
      1393955.01      6898838.01      1394205.00      6899088.00
      1394354.96      6899088.00
#Sta/Elev= 30
  4651.5 2057.13  4655.0 2057.13  4665.6 2055.90  4679.8 2055.43  4767.4 2054.23
  4807.1 2054.49  4835.3 2052.43  4863.6 2051.67  4877.8 2050.30  4891.9 2049.51
  4906.0 2047.77  4934.3 2043.00  4948.5 2042.64  4962.6 2042.79  4988.7 2041.48
  4989.0 2040.98  4992.8 2040.98  4993.1 2041.48  5001.5 2042.07  5007.5 2042.07
  5015.0 2045.14  5025.0 2048.54  5035.0 2050.41  5045.0 2051.54  5075.0 2053.15
  5105.0 2055.23  5115.0 2055.28  5125.0 2056.38  5145.0 2056.90  5155.0 2057.56
#Mann=4,-1,0
  4651.5   0.035       0  4767.4    0.07       0  4988.7    0.07       0
  4993.1    0.07       0
Bank Sta=4988.7,4993.1
Exp/Cntr=0.3,0.1

Type RM Length L Ch R = 1,27044,477,477,477
BEGIN DESCRIPTION:
Plum Creek Trib4 40.0
END DESCRIPTION:
XS GIS Cut Line= 3
      1393413.34      6899081.16      1393905.00      6899388.00
      1394244.47      6899680.10
#Sta/Elev= 30
  4415.9 2056.45  4488.6 2055.31  4646.9 2054.79  4762.5 2052.63  4793.1 2053.71
  4799.0 2052.96  4835.6 2052.86  4901.2 2050.02  4945.3 2042.07  4981.9 2040.06
  4990.3 2038.19  4990.6 2037.69  4994.8 2038.19  5002.6 2038.51  5009.2 2040.43
  5016.8 2040.82  5045.4 2040.10  5073.9 2041.71  5087.8 2042.94  5094.8 2045.02
  5123.3 2049.14  5148.6 2050.86  5193.5 2052.20  5222.0 2054.66  5250.6 2054.59
  5285.7 2057.81  5314.2 2057.38  5342.7 2059.01  5350.4 2060.21  5443.3 2061.10
#Mann=4,-1,0
  4415.9    0.07       0  4990.3    0.07       0  4994.8    0.07       0
  5148.6   0.035       0
Bank Sta=4990.3,4994.8
Exp/Cntr=0.3,0.1

Type RM Length L Ch R = 1,26567,286,286,286
BEGIN DESCRIPTION:
Plum Creek Trib4 39.0
END DESCRIPTION:
XS GIS Cut Line= 3
      1393455.04      6899688.02      1393705.00      6899788.00
      1394104.98      6899788.00
#Sta/Elev= 30
  4731.2 2053.23  4828.5 2049.43  4833.1 2049.07  4892.7 2045.09  4907.5 2043.52
  4914.3 2041.23  4925.0 2039.77  4937.1 2039.18  4956.0 2042.84  4961.4 2041.65
  4978.9 2043.69  4985.6 2041.72  4991.0 2041.98  4997.7 2038.04  5008.1 2036.82
  5008.4 2036.32  5012.8 2036.82  5056.5 2038.52  5090.4 2039.56  5124.5 2043.62
  5140.4 2044.34  5190.4 2049.95  5203.4 2049.19  5230.4 2049.27  5260.4 2051.97
  5300.4 2052.42  5320.4 2054.90  5340.4 2054.05  5390.4 2057.97  5400.4 2057.50
#Mann=8,-1,0
  4731.2    0.07       0  4828.5    0.16       0  4833.1    0.07       0
  5008.1    0.07       0  5012.8    0.07       0  5056.5    0.16       0
  5124.5    0.07       0  5203.4   0.035       0
Bank Sta=5008.1,5012.8
Exp/Cntr=0.3,0.1

Type RM Length L Ch R = 1,26281,19,19,19
BEGIN DESCRIPTION:
Mapping XS c37569f3
END DESCRIPTION:
XS GIS Cut Line= 6
      1393298.33      6899827.70      1393580.43      6900018.66
      1393821.31      6900118.48      1393845.19      6900157.55
      1393856.04      6900196.61      1394138.14      6900409.27
#Sta/Elev= 30
  4550.6 2057.29  4591.3 2054.96  4706.4 2050.40  4801.1 2047.48  4879.9 2045.52
  4885.9 2048.12  4896.4 2046.86  4901.7 2048.90  4924.5 2044.67  4930.0 2046.86
  4947.3 2045.11  4975.7 2046.73  5022.6 2043.01  5028.0 2045.01  5047.6 2043.30
  5052.9 2047.23  5077.0 2045.03  5083.2 2047.70  5108.1 2042.58  5113.4 2045.23
  5151.5 2040.87  5241.0 2042.85  5317.1 2040.21  5425.1 2043.09  5450.1 2039.91
  5450.4 2039.41  5454.8 2039.91  5460.7 2041.77  5510.7 2041.95  5591.8 2047.02
#Mann=6,-1,0
  4550.6   0.035       0  4591.3    0.07       0  4706.4   0.035       0
  4801.1    0.07       0  5450.1    0.07       0  5454.8    0.07       0
Bank Sta=5450.1,5454.8
Exp/Cntr=0.3,0.1

Type RM Length L Ch R = 1,26262,22,22,22
BEGIN DESCRIPTION:
Mapping XS fcfba3da
END DESCRIPTION:
XS GIS Cut Line= 6
      1393272.26      6899838.53      1393699.79      6900105.46
      1393754.04      6900109.80      1393816.97      6900138.02
      1393838.67      6900205.29      1394146.86      6900441.85
#Sta/Elev= 30
  4539.3 2057.41  4618.4 2054.77  4679.9 2052.55  4720.8 2048.98  4804.5 2047.06
  4887.6 2049.11  4992.3 2048.81  5035.8 2047.74  5059.3 2044.75  5105.6 2048.04
  5111.1 2045.33  5128.8 2047.04  5134.3 2044.55  5143.3 2047.32  5170.0 2045.96
  5174.9 2047.47  5180.2 2045.17  5198.9 2047.81  5212.2 2046.02  5245.3 2046.57
  5301.4 2039.66  5365.8 2043.75  5386.6 2041.92  5450.9 2042.98  5465.5 2042.13
  5470.6 2039.46  5471.0 2038.96  5475.3 2039.46  5550.6 2046.61  5626.6 2048.73
#Mann=6,-1,0
  4539.3   0.035       0  4618.4    0.07       0  4679.9   0.035       0
  4804.5    0.07       0  5470.6    0.07       0  5475.3    0.07       0
Bank Sta=5470.6,5475.3
Exp/Cntr=0.3,0.1

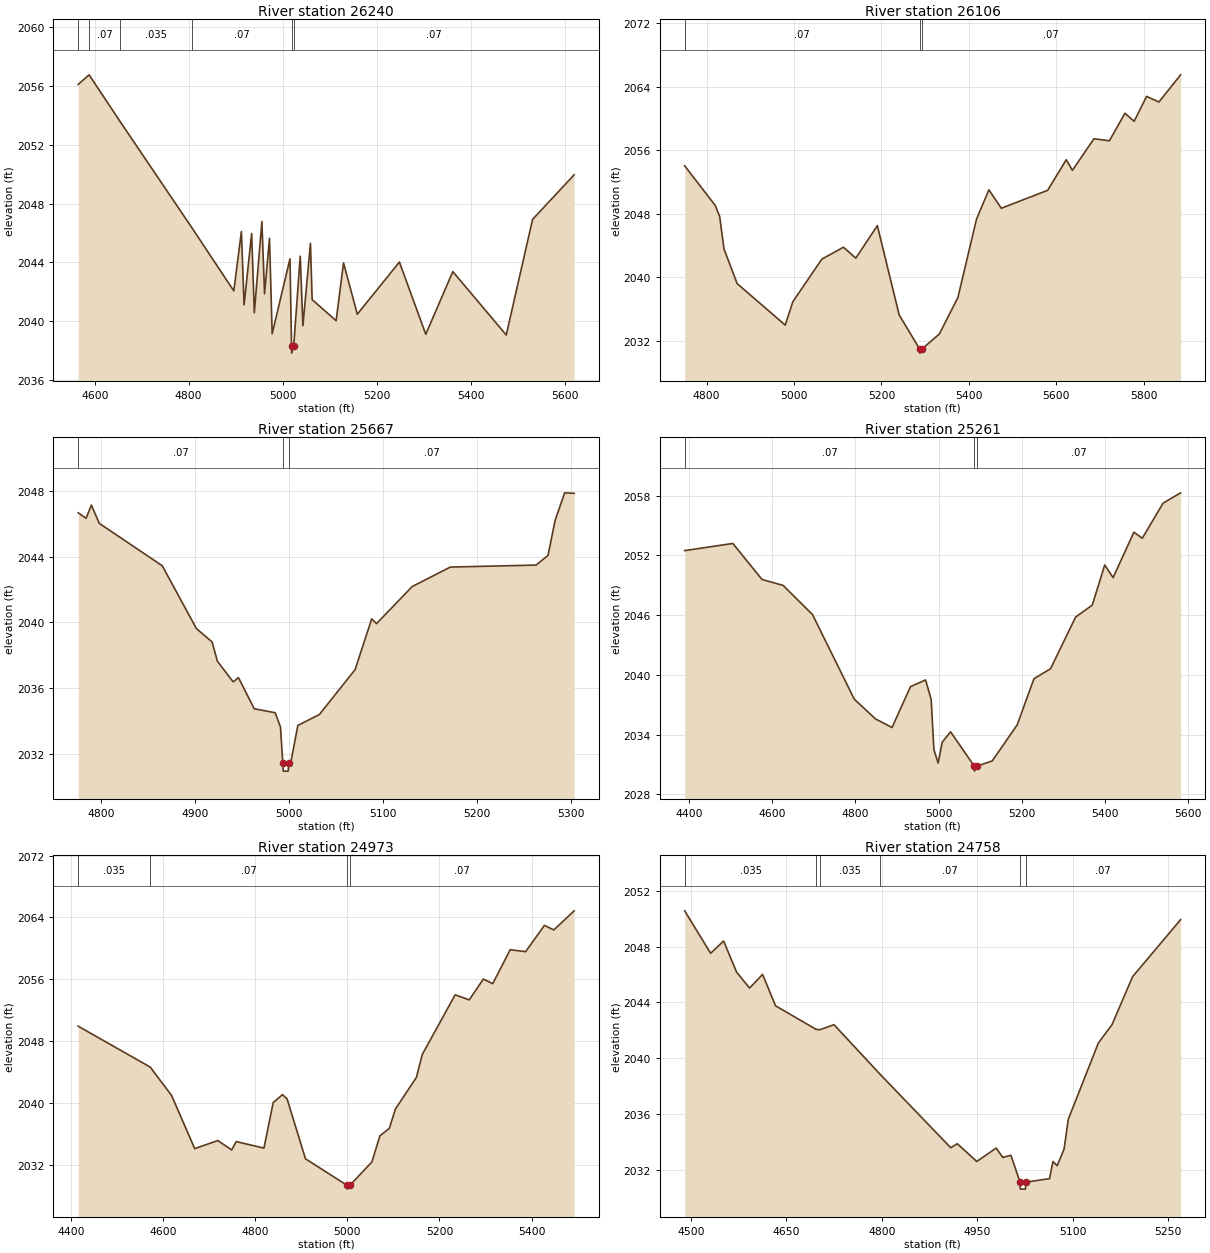
Type RM Length L Ch R = 1,26240,134,134,134
BEGIN DESCRIPTION:
Mapping XS f9abe6e6
END DESCRIPTION:
XS GIS Cut Line= 6
      1393274.47      6899873.28      1393706.30      6900124.99
      1393771.40      6900131.51      1393806.12      6900174.91
      1393825.65      6900222.65      1394125.12      6900461.36
#Sta/Elev= 30
  4564.9 2056.08  4588.1 2056.73  4653.9 2053.57  4807.6 2046.32  4896.1 2042.07
  4912.2 2046.10  4917.9 2041.12  4934.0 2045.97  4939.7 2040.59  4955.8 2046.78
  4961.5 2041.88  4972.0 2045.64  4977.7 2039.16  5015.6 2044.25  5018.9 2038.35
  5019.3 2037.85  5023.6 2038.35  5037.4 2044.43  5043.1 2039.71  5059.2 2045.30
  5062.8 2041.48  5113.8 2040.05  5129.6 2043.97  5158.9 2040.49  5248.5 2044.03
  5304.6 2039.13  5362.2 2043.38  5475.9 2039.08  5531.9 2046.92  5620.4 2049.95
#Mann=6,-1,0
  4564.9   0.035       0  4588.1    0.07       0  4653.9   0.035       0
  4807.6    0.07       0  5018.9    0.07       0  5023.6    0.07       0
Bank Sta=5018.9,5023.6
Exp/Cntr=0.3,0.1

Type RM Length L Ch R = 1,26106,439,439,439
BEGIN DESCRIPTION:
Plum Creek Trib4 38.0
END DESCRIPTION:
XS GIS Cut Line= 3
      1393304.97      6900188.00      1393555.00      6900188.00
      1394204.98      6900787.99
#Sta/Elev= 30
  4750.0 2054.07  4820.0 2049.07  4830.0 2047.70  4840.0 2043.59  4870.0 2039.23
  4980.0 2034.00  4997.5 2036.95  5063.8 2042.31  5113.2 2043.81  5141.5 2042.44
  5190.8 2046.53  5240.7 2035.29  5287.7 2030.97  5288.1 2030.47  5292.4 2030.97
  5332.6 2032.88  5375.1 2037.48  5417.7 2047.36  5446.0 2051.04  5474.4 2048.72
  5580.4 2050.98  5622.9 2054.83  5637.1 2053.50  5686.4 2057.48  5721.6 2057.22
  5757.3 2060.69  5778.3 2059.67  5806.7 2062.81  5835.0 2062.11  5884.6 2065.53
#Mann=3,-1,0
  4750.0    0.07       0  5287.7    0.07       0  5292.4    0.07       0
Bank Sta=5287.7,5292.4
Exp/Cntr=0.3,0.1

Type RM Length L Ch R = 1,25667,406,406,406
BEGIN DESCRIPTION:
Plum Creek Trib4 37.0
END DESCRIPTION:
XS GIS Cut Line= 3
      1393255.00      6900488.00      1393455.00      6900588.00
      1393754.96      6900538.01
#Sta/Elev= 30
  4776.0 2046.65  4784.4 2046.32  4790.0 2047.12  4798.4 2046.01  4865.4 2043.44
  4901.8 2039.63  4918.5 2038.82  4924.1 2037.65  4940.9 2036.40  4946.5 2036.66
  4963.3 2034.77  4985.6 2034.53  4991.2 2033.67  4993.7 2031.49  4994.2 2030.99
  4999.5 2030.99  5000.0 2031.49  5002.1 2031.49  5009.7 2033.76  5032.6 2034.42
  5070.6 2037.14  5088.3 2040.22  5093.4 2039.93  5131.4 2042.18  5172.0 2043.36
  5263.2 2043.48  5275.9 2044.07  5283.5 2046.20  5293.6 2047.86  5303.7 2047.83
#Mann=3,-1,0
  4776.0    0.07       0  4993.7    0.07       0  5000.0    0.07       0
Bank Sta=4993.7,5000
Exp/Cntr=0.3,0.1

Type RM Length L Ch R = 1,25261,288,288,288
BEGIN DESCRIPTION:
Mapping XS 83abad61
END DESCRIPTION:
XS GIS Cut Line= 3
      1392800.01      6901044.70      1393388.41      6900977.24
      1393987.09      6901003.47
#Sta/Elev= 30
  4390.0 2052.47  4505.7 2053.19  4575.9 2049.57  4626.5 2048.98  4697.0 2046.06
  4797.6 2037.55  4848.5 2035.58  4888.2 2034.72  4932.6 2038.82  4968.8 2039.49
  4982.2 2037.54  4988.8 2032.49  4998.9 2031.16  5008.9 2033.26  5028.9 2034.28
  5085.8 2030.84  5086.3 2030.34  5092.1 2030.84  5129.0 2031.37  5189.0 2034.99
  5229.1 2039.61  5269.1 2040.62  5329.2 2045.80  5369.2 2047.00  5399.2 2051.03
  5419.3 2049.76  5469.3 2054.32  5489.3 2053.71  5539.4 2057.23  5581.5 2058.27
#Mann=3,-1,0
  4390.0    0.07       0  5085.8    0.07       0  5092.1    0.07       0
Bank Sta=5085.8,5092.1
Exp/Cntr=0.3,0.1

Type RM Length L Ch R = 1,24973,215,215,215
BEGIN DESCRIPTION:
Plum Creek Trib4 36.0
END DESCRIPTION:
XS GIS Cut Line= 3
      1393022.69      6901123.26      1393605.54      6901162.88
      1394088.27      6901259.98
#Sta/Elev= 30
  4415.8 2049.94  4572.2 2044.65  4618.6 2040.97  4668.7 2034.11  4718.8 2035.15
  4748.9 2033.94  4758.9 2035.02  4819.0 2034.17  4839.1 2040.06  4859.2 2041.09
  4869.2 2040.55  4909.2 2032.79  4999.4 2029.37  4999.9 2028.87  5005.7 2029.37
  5053.4 2032.39  5070.8 2035.77  5091.2 2036.72  5104.3 2039.22  5150.0 2043.32
  5162.7 2046.28  5234.1 2054.00  5264.7 2053.34  5295.3 2056.04  5315.7 2055.44
  5353.5 2059.83  5387.1 2059.58  5427.9 2062.98  5448.3 2062.39  5492.4 2064.86
#Mann=4,-1,0
  4415.8   0.035       0  4572.2    0.07       0  4999.4    0.07       0
  5005.7    0.07       0
Bank Sta=4999.4,5005.7
Exp/Cntr=0.3,0.1

Type RM Length L Ch R = 1,24758,251,251,251
BEGIN DESCRIPTION:
Plum Creek Trib4 35.0
END DESCRIPTION:
XS GIS Cut Line= 3
      1393005.00      6901238.00      1393505.00      6901338.00
      1393755.04      6901438.02
#Sta/Elev= 30
  4490.1 2050.56  4530.9 2047.52  4551.3 2048.40  4571.7 2046.17  4592.1 2045.03
  4612.5 2046.01  4632.9 2043.76  4696.9 2042.07  4702.5 2042.05  4724.7 2042.41
  4797.6 2038.84  4908.2 2033.60  4918.4 2033.89  4949.0 2032.62  4979.6 2033.58
  4989.8 2032.91  5002.7 2033.06  5017.0 2031.14  5017.5 2030.64  5025.5 2030.64
  5026.0 2031.14  5063.3 2031.39  5068.7 2032.62  5075.4 2032.31  5086.2 2033.51
  5092.9 2035.65  5140.0 2041.09  5161.6 2042.42  5193.9 2045.85  5269.3 2049.93
#Mann=6,-1,0
  4490.1   0.035       0  4696.9    0.07       0  4702.5   0.035       0
  4797.6    0.07       0  5017.0    0.07       0  5026.0    0.07       0
Bank Sta=5017,5026
Exp/Cntr=0.3,0.1

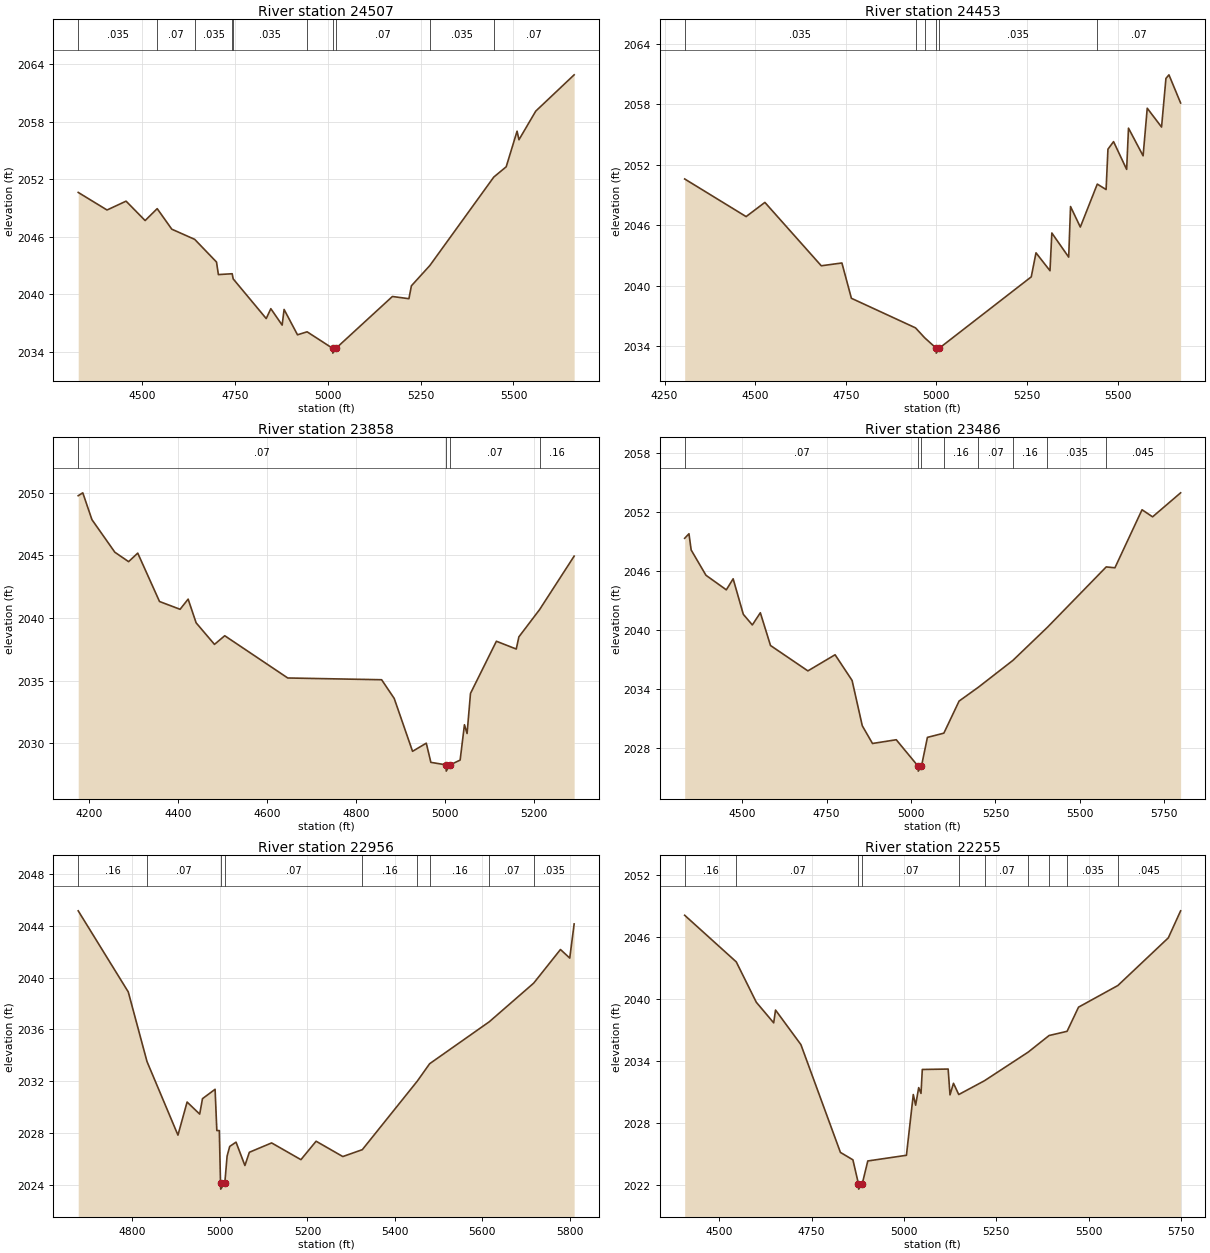
Type RM Length L Ch R = 1,24507,54,54,54
BEGIN DESCRIPTION:
Mapping XS aa6e822e
END DESCRIPTION:
XS GIS Cut Line= 3
      1392699.37      6901379.34      1393343.88      6901526.90
      1394004.25      6901663.31
#Sta/Elev= 30
  4327.9 2050.63  4405.5 2048.80  4456.8 2049.72  4508.1 2047.70  4540.6 2048.94
  4579.9 2046.80  4641.6 2045.74  4700.3 2043.38  4705.4 2042.07  4742.5 2042.16
  4745.3 2041.62  4834.2 2037.49  4846.6 2038.52  4877.1 2036.81  4882.3 2038.44
  4918.4 2035.80  4944.3 2036.11  5013.0 2034.39  5013.5 2033.89  5022.0 2034.39
  5174.0 2039.79  5218.5 2039.56  5225.1 2040.90  5274.9 2043.02  5447.0 2052.23
  5480.4 2053.30  5509.7 2057.01  5514.8 2056.12  5560.0 2059.10  5663.4 2062.88
#Mann=10,-1,0
  4327.9   0.035       0  4540.6    0.07       0  4641.6   0.035       0
  4742.5    0.07       0  4745.3   0.035       0  4944.3    0.07       0
  5013.0    0.07       0  5022.0    0.07       0  5274.9   0.035       0
  5447.0    0.07       0
Bank Sta=5013,5022
Exp/Cntr=0.3,0.1

Type RM Length L Ch R = 1,24453,595,595,595
BEGIN DESCRIPTION:
Mapping XS 005bf9c3
END DESCRIPTION:
XS GIS Cut Line= 3
      1392673.33      6901450.95      1393348.22      6901581.16
      1394016.62      6901711.37
#Sta/Elev= 30
  4305.5 2050.59  4475.0 2046.85  4526.8 2048.26  4682.4 2041.96  4739.3 2042.24
  4765.5 2038.73  4942.4 2035.79  4967.8 2034.80  4999.2 2033.78  4999.7 2033.28
  5008.2 2033.78  5261.7 2040.86  5274.8 2043.25  5313.4 2041.47  5318.5 2045.22
  5365.0 2042.82  5370.1 2047.85  5397.1 2045.81  5443.9 2050.08  5468.2 2049.54
  5473.3 2053.55  5488.8 2054.30  5524.9 2051.54  5530.0 2055.64  5570.3 2052.89
  5581.7 2057.62  5621.2 2055.75  5633.3 2060.58  5641.6 2060.94  5673.8 2058.14
#Mann=6,-1,0
  4305.5   0.035       0  4942.4    0.07       0  4967.8   0.035       0
  4999.2   0.035       0  5008.2   0.035       0  5443.9    0.07       0
Bank Sta=4999.2,5008.2
Exp/Cntr=0.3,0.1

Type RM Length L Ch R = 1,23858,372,372,372
BEGIN DESCRIPTION:
Plum Creek Trib4 33.0
END DESCRIPTION:
XS GIS Cut Line= 3
      1392705.00      6902288.00      1393505.00      6902088.00
      1393755.03      6901937.98
#Sta/Elev= 30
  4175.2 2049.75  4185.5 2049.98  4206.1 2047.84  4257.7 2045.24  4288.6 2044.49
  4309.2 2045.17  4358.2 2041.31  4404.5 2040.69  4422.6 2041.50  4440.6 2039.61
  4481.9 2037.89  4505.0 2038.58  4646.8 2035.21  4858.1 2035.07  4886.4 2033.58
  4927.7 2029.36  4958.6 2030.01  4968.9 2028.48  5003.0 2028.28  5003.5 2027.78
  5012.2 2028.28  5034.8 2028.66  5044.5 2031.48  5050.4 2030.78  5058.1 2033.98
  5116.4 2038.14  5161.1 2037.52  5167.0 2038.49  5213.5 2040.66  5291.4 2044.93
#Mann=4,-1,0
  4175.2    0.07       0  5003.0    0.07       0  5012.2    0.07       0
  5213.5    0.16       0
Bank Sta=5003,5012.2
Exp/Cntr=0.3,0.1

Type RM Length L Ch R = 1,23486,530,530,530
BEGIN DESCRIPTION:
Plum Creek Trib4 32.0
END DESCRIPTION:
XS GIS Cut Line= 3
      1392712.42      6902340.71      1393378.42      6902414.76
      1394144.65      6902638.01
#Sta/Elev= 30
  4329.9 2049.34  4342.6 2049.80  4349.1 2048.15  4392.9 2045.58  4453.2 2044.10
  4473.4 2045.22  4503.5 2041.61  4530.2 2040.53  4553.9 2041.77  4584.0 2038.44
  4694.7 2035.86  4775.2 2037.50  4825.5 2034.89  4855.7 2030.28  4885.9 2028.48
  4956.3 2028.86  5021.0 2026.17  5021.5 2025.67  5030.9 2026.17  5048.5 2029.10
  5097.2 2029.53  5142.3 2032.79  5199.4 2034.20  5301.7 2036.93  5404.0 2040.30
  5577.9 2046.43  5603.6 2046.34  5683.9 2052.24  5715.1 2051.52  5798.1 2053.96
#Mann=8,-1,0
  4329.9    0.07       0  5021.0    0.07       0  5030.9    0.07       0
  5097.2    0.16       0  5199.4    0.07       0  5301.7    0.16       0
  5404.0   0.035       0  5577.9   0.045       0
Bank Sta=5021,5030.9
Exp/Cntr=0.3,0.1

Type RM Length L Ch R = 1,22956,701,701,701
BEGIN DESCRIPTION:
Plum Creek Trib4 31.0
END DESCRIPTION:
XS GIS Cut Line= 3
      1392804.97      6902938.02      1393055.00      6902738.00
      1393854.97      6902588.01
#Sta/Elev= 30
  4675.9 2045.14  4790.4 2038.89  4833.2 2033.53  4904.0 2027.86  4924.9 2030.41
  4953.7 2029.48  4960.1 2030.67  4988.9 2031.39  4992.9 2028.21  4998.6 2028.21
  5001.3 2024.20  5001.8 2023.70  5011.2 2024.20  5016.4 2026.25  5022.4 2026.99
  5036.8 2027.32  5057.1 2025.52  5067.3 2026.54  5118.2 2027.26  5185.2 2025.97
  5219.9 2027.39  5281.0 2026.21  5325.6 2026.74  5451.5 2032.03  5479.5 2033.36
  5616.2 2036.60  5717.5 2039.57  5778.7 2042.16  5799.9 2041.50  5810.0 2044.13
#Mann=9,-1,0
  4675.9    0.16       0  4833.2    0.07       0  5001.3    0.07       0
  5011.2    0.07       0  5325.6    0.16       0  5451.5    0.07       0
  5479.5    0.16       0  5616.2    0.07       0  5717.5   0.035       0
Bank Sta=5001.3,5011.2
Exp/Cntr=0.3,0.1

Type RM Length L Ch R = 1,22255,32,32,32
BEGIN DESCRIPTION:
Mapping XS 006c7890
END DESCRIPTION:
XS GIS Cut Line= 6
      1392762.27      6902996.09      1393306.99      6903056.85
      1393346.05      6903091.57      1393374.27      6903128.47
      1393480.60      6903119.79      1394046.99      6902957.03
#Sta/Elev= 30
  4406.5 2048.12  4546.2 2043.60  4600.4 2039.69  4647.5 2037.69  4652.5 2038.93
  4721.2 2035.58  4828.2 2025.13  4862.0 2024.41  4877.1 2022.07  4877.6 2021.57
  4887.2 2022.07  4902.3 2024.30  5006.9 2024.85  5025.5 2030.74  5031.8 2029.71
  5040.1 2031.41  5046.4 2030.85  5049.9 2033.17  5119.9 2033.21  5124.9 2030.71
  5134.3 2031.83  5148.6 2030.74  5218.3 2032.08  5336.5 2034.85  5393.1 2036.46
  5441.9 2036.87  5472.9 2039.21  5579.4 2041.31  5716.0 2045.93  5749.3 2048.55
#Mann=10,-1,0
  4406.5    0.16       0  4546.2    0.07       0  4877.1    0.07       0
  4887.2    0.07       0  5148.6    0.16       0  5218.3    0.07       0
  5336.5   0.035       0  5393.1    0.16       0  5441.9   0.035       0
  5579.4   0.045       0
Bank Sta=4877.1,4887.2
Exp/Cntr=0.3,0.1

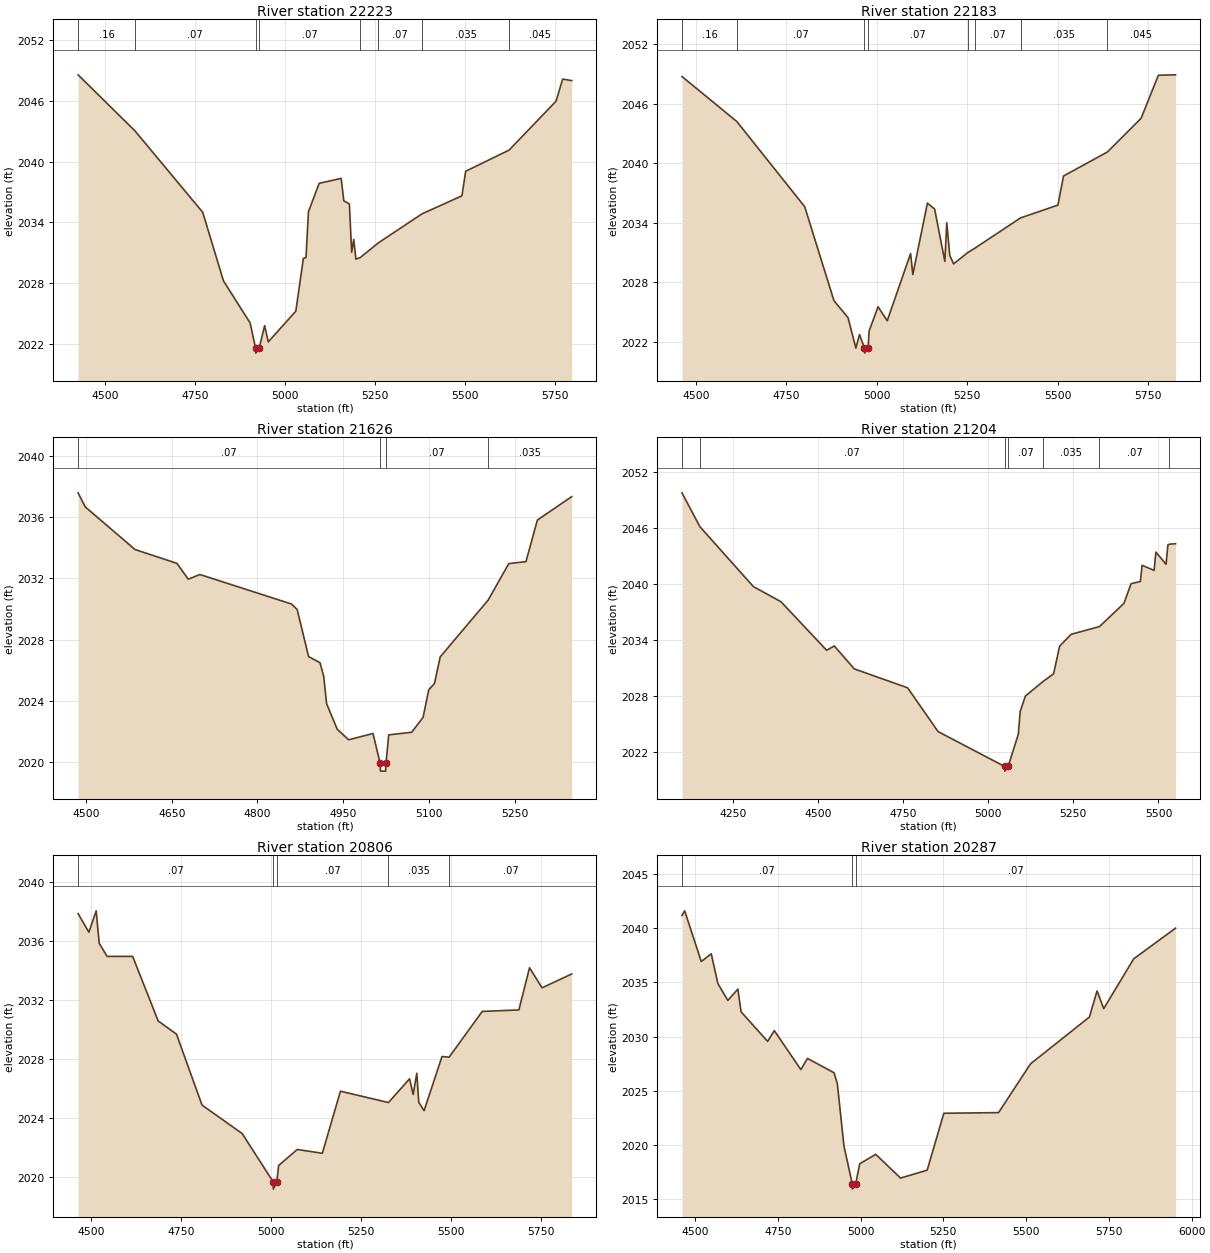
Type RM Length L Ch R = 1,22223,40,40,40
BEGIN DESCRIPTION:
Mapping XS 3571bd04
END DESCRIPTION:
XS GIS Cut Line= 6
      1392742.74      6903002.60      1393304.82      6903087.23
      1393367.75      6903156.68      1393428.52      6903161.02
      1393471.92      6903137.15      1394049.16      6902980.90
#Sta/Elev= 30
  4426.0 2048.57  4583.9 2043.04  4772.1 2035.00  4829.7 2028.23  4903.7 2024.08
  4918.8 2021.60  4919.3 2021.10  4928.9 2021.60  4944.0 2023.81  4954.1 2022.21
  5030.6 2025.24  5051.5 2030.44  5058.9 2030.54  5065.7 2035.06  5095.4 2037.86
  5156.5 2038.35  5163.9 2036.13  5179.3 2035.83  5185.7 2031.05  5191.4 2032.32
  5197.5 2030.38  5209.3 2030.53  5260.0 2031.99  5381.1 2034.85  5491.9 2036.63
  5502.2 2039.05  5622.9 2041.14  5753.2 2045.97  5771.6 2048.15  5796.6 2048.00
#Mann=8,-1,0
  4426.0    0.16       0  4583.9    0.07       0  4918.8    0.07       0
  4928.9    0.07       0  5209.3    0.16       0  5260.0    0.07       0
  5381.1   0.035       0  5622.9   0.045       0
Bank Sta=4918.8,4928.9
Exp/Cntr=0.3,0.1

Type RM Length L Ch R = 1,22183,557,557,557
BEGIN DESCRIPTION:
Mapping XS a769ab35
END DESCRIPTION:
XS GIS Cut Line= 6
      1392749.27      6903026.47      1393257.08      6903100.26
      1393367.75      6903182.72      1393430.69      6903178.38
      1393469.75      6903163.19      1394061.06      6903020.24
#Sta/Elev= 30
  4461.7 2048.73  4613.3 2044.20  4801.0 2035.62  4881.8 2026.16  4920.8 2024.44
  4942.4 2021.38  4952.5 2022.74  4966.2 2021.37  4966.7 2020.87  4976.3 2021.37
  4979.0 2023.09  5003.8 2025.54  5029.1 2024.13  5093.7 2030.90  5099.9 2028.78
  5140.2 2035.98  5160.2 2035.38  5188.4 2030.11  5193.7 2034.00  5202.0 2030.71
  5212.6 2029.86  5251.4 2030.99  5271.5 2031.44  5397.7 2034.49  5501.0 2035.78
  5516.5 2038.71  5637.5 2041.12  5730.9 2044.52  5778.8 2048.86  5826.2 2048.90
#Mann=8,-1,0
  4461.7    0.16       0  4613.3    0.07       0  4966.2    0.07       0
  4976.3    0.07       0  5251.4    0.16       0  5271.5    0.07       0
  5397.7   0.035       0  5637.5   0.045       0
Bank Sta=4966.2,4976.3
Exp/Cntr=0.3,0.1

Type RM Length L Ch R = 1,21626,422,422,422
BEGIN DESCRIPTION:
Plum Creek Trib4 28.0
END DESCRIPTION:
XS GIS Cut Line= 3
      1392892.53      6903469.18      1393405.00      6903438.00
      1393754.98      6903438.00
#Sta/Elev= 30
  4486.2 2037.60  4498.7 2036.68  4585.9 2033.89  4659.0 2032.99  4679.0 2031.95
  4699.1 2032.26  4859.4 2030.33  4869.4 2029.97  4889.4 2026.89  4909.4 2026.49
  4915.9 2025.59  4920.9 2023.81  4939.5 2022.14  4959.5 2021.45  5002.1 2021.86
  5014.6 2019.90  5015.1 2019.40  5024.2 2019.40  5024.7 2019.90  5029.6 2021.77
  5069.6 2021.94  5089.6 2022.91  5099.6 2024.72  5109.6 2025.13  5119.6 2026.87
  5203.4 2030.58  5239.6 2032.97  5269.6 2033.10  5289.6 2035.82  5349.6 2037.35
#Mann=4,-1,0
  4486.2    0.07       0  5014.6    0.07       0  5024.7    0.07       0
  5203.4   0.035       0
Bank Sta=5014.6,5024.7
Exp/Cntr=0.3,0.1

Type RM Length L Ch R = 1,21204,398,398,398
BEGIN DESCRIPTION:
Plum Creek Trib4 27.0
END DESCRIPTION:
XS GIS Cut Line= 3
      1392605.01      6903388.01      1393405.00      6903788.00
      1393941.40      6903928.87
#Sta/Elev= 30
  4101.2 2049.81  4153.8 2046.17  4310.8 2039.73  4391.9 2038.10  4526.0 2032.88
  4548.4 2033.35  4607.1 2030.88  4763.6 2028.85  4853.1 2024.14  5048.5 2020.39
  5049.0 2019.89  5058.7 2020.39  5088.7 2023.87  5093.9 2026.28  5109.3 2027.96
  5160.5 2029.51  5192.1 2030.35  5209.9 2033.33  5243.7 2034.60  5326.8 2035.43
  5398.8 2037.93  5419.5 2040.04  5446.9 2040.28  5452.0 2042.02  5487.2 2041.47
  5492.4 2043.44  5522.4 2042.13  5527.6 2044.20  5532.4 2044.29  5550.2 2044.34
#Mann=7,-1,0
  4101.2    0.16       0  4153.8    0.07       0  5048.5    0.07       0
  5058.7    0.07       0  5160.5   0.035       0  5326.8    0.07       0
  5532.4   0.045       0
Bank Sta=5048.5,5058.7
Exp/Cntr=0.3,0.1

Type RM Length L Ch R = 1,20806,519,519,519
BEGIN DESCRIPTION:
Plum Creek Trib4 26.0
END DESCRIPTION:
XS GIS Cut Line= 3
      1392675.45      6904022.56      1393204.98      6904113.00
      1394030.90      6904235.10
#Sta/Elev= 30
  4462.8 2037.88  4492.8 2036.62  4513.1 2038.07  4521.5 2035.87  4543.5 2034.98
  4614.5 2034.98  4685.5 2030.60  4736.3 2029.71  4807.3 2024.90  4918.9 2022.97
  5005.0 2019.70  5005.5 2019.20  5015.3 2019.70  5020.2 2020.80  5072.1 2021.89
  5141.7 2021.63  5192.1 2025.84  5325.6 2025.07  5384.2 2026.68  5394.3 2025.62
  5404.4 2027.06  5409.8 2025.09  5424.6 2024.52  5474.4 2028.19  5494.2 2028.15
  5586.3 2031.25  5688.1 2031.35  5717.7 2034.21  5752.6 2032.85  5834.9 2033.79
#Mann=5,-1,0
  4462.8    0.07       0  5005.0    0.07       0  5015.3    0.07       0
  5325.6   0.035       0  5494.2    0.07       0
Bank Sta=5005,5015.3
Exp/Cntr=0.3,0.1

Type RM Length L Ch R = 1,20287,474,474,474
BEGIN DESCRIPTION:
Plum Creek Trib4 25.0
END DESCRIPTION:
XS GIS Cut Line= 3
      1392616.84      6904552.08      1393155.00      6904588.00
      1394100.66      6904690.90
#Sta/Elev= 30
  4460.8 2041.17  4469.0 2041.60  4519.1 2036.92  4549.2 2037.64  4569.2 2034.89
  4599.3 2033.33  4629.6 2034.38  4639.4 2032.28  4719.5 2029.55  4739.6 2030.55
  4819.8 2026.95  4839.8 2027.98  4920.0 2026.66  4930.0 2025.65  4950.0 2019.90
  4975.0 2016.42  4975.5 2015.92  4985.3 2016.42  4997.6 2018.26  5045.9 2019.13
  5120.9 2016.94  5201.3 2017.67  5251.6 2022.92  5416.9 2022.98  5513.4 2027.48
  5691.3 2031.80  5714.3 2034.21  5734.5 2032.58  5825.0 2037.17  5951.4 2040.00
#Mann=3,-1,0
  4460.8    0.07       0  4975.0    0.07       0  4985.3    0.07       0
Bank Sta=4975,4985.3
Exp/Cntr=0.3,0.1

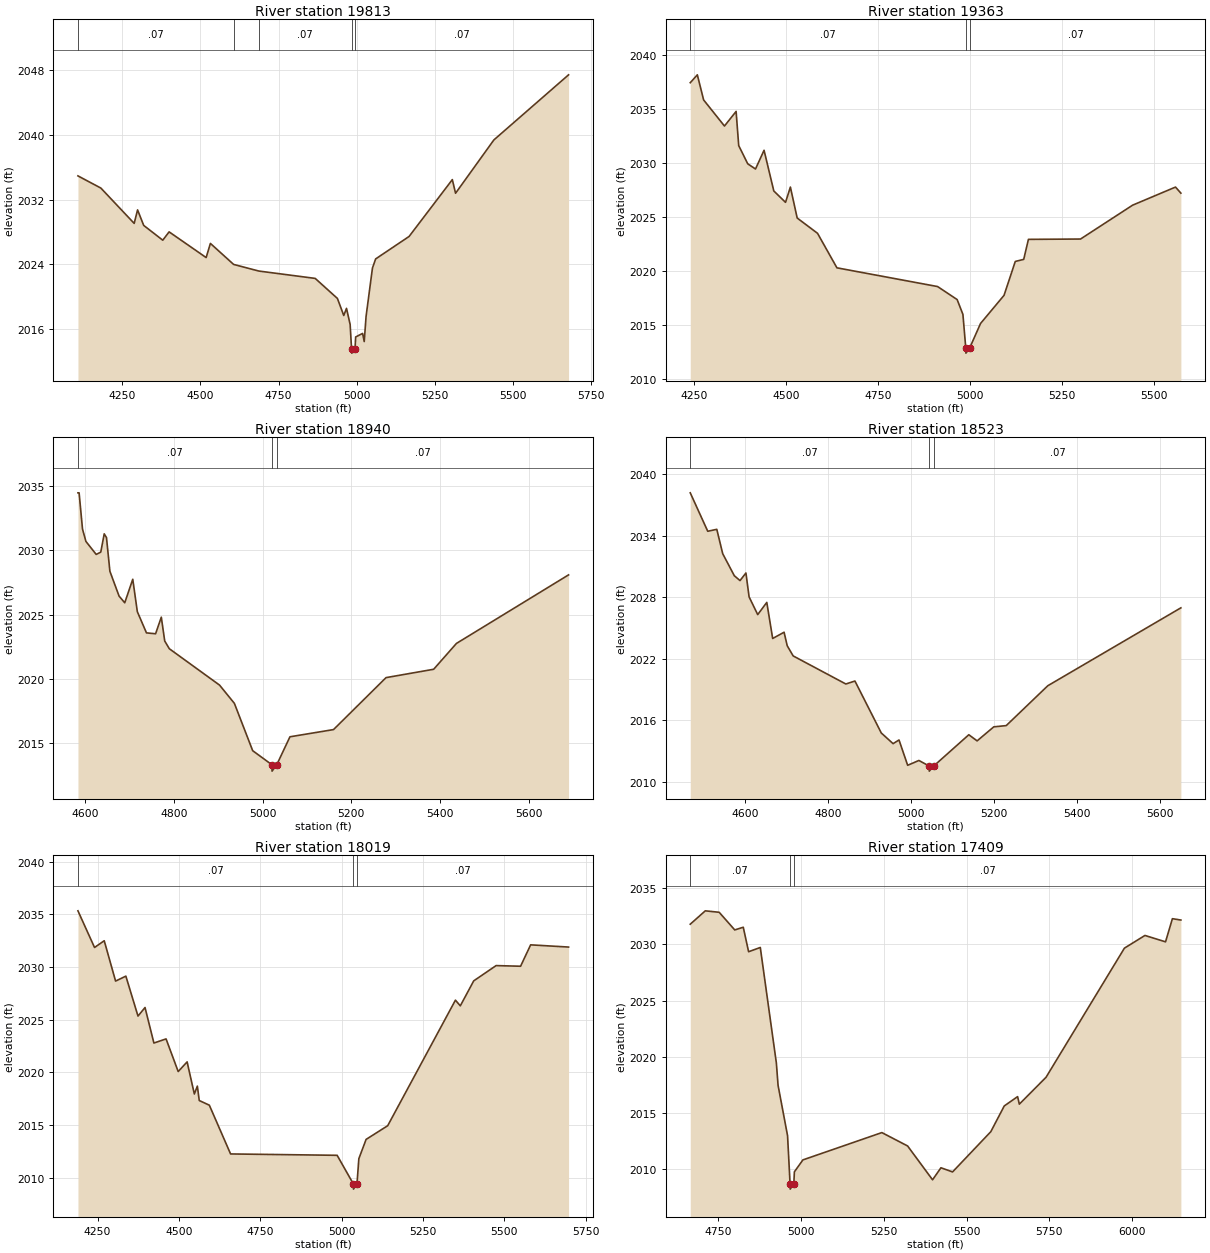
Type RM Length L Ch R = 1,19813,450,450,450
BEGIN DESCRIPTION:
Plum Creek Trib4 24.0
END DESCRIPTION:
XS GIS Cut Line= 3
      1392527.95      6904779.95      1393405.00      6904938.00
      1394068.72      6905079.42
#Sta/Elev= 30
  4108.3 2034.94  4181.7 2033.43  4288.2 2029.06  4299.1 2030.73  4318.7 2028.81
  4379.7 2026.98  4400.0 2028.01  4518.5 2024.83  4532.1 2026.58  4606.4 2023.98
  4687.1 2023.16  4867.4 2022.25  4938.5 2019.77  4958.8 2017.66  4967.6 2018.54
  4979.2 2016.55  4983.8 2013.50  4984.3 2013.00  4994.8 2013.50  4996.9 2015.00
  5019.1 2015.44  5024.3 2014.43  5030.2 2017.55  5050.6 2023.53  5060.8 2024.66
  5167.8 2027.44  5306.2 2034.48  5316.5 2032.79  5439.1 2039.39  5678.1 2047.45
#Mann=5,-1,0
  4108.3    0.07       0  4606.4   0.035       0  4687.1    0.07       0
  4983.8    0.07       0  4994.8    0.07       0
Bank Sta=4983.8,4994.8
Exp/Cntr=0.3,0.1

Type RM Length L Ch R = 1,19363,423,423,423
BEGIN DESCRIPTION:
Plum Creek Trib4 23.0
END DESCRIPTION:
XS GIS Cut Line= 3
      1392436.75      6905051.20      1393155.00      6905288.00
      1393695.41      6905487.39
#Sta/Elev= 30
  4239.8 2037.41  4259.0 2038.14  4276.1 2035.82  4332.7 2033.41  4364.3 2034.76
  4371.4 2031.60  4395.9 2029.92  4417.0 2029.44  4440.2 2031.17  4466.7 2027.41
  4498.5 2026.36  4511.7 2027.77  4530.2 2024.91  4585.4 2023.50  4638.1 2020.31
  4911.4 2018.58  4964.5 2017.38  4980.2 2016.01  4987.9 2012.93  4988.4 2012.43
  4998.9 2012.93  5028.1 2015.17  5091.9 2017.77  5122.4 2020.90  5145.3 2021.09
  5158.1 2022.94  5299.6 2022.97  5441.1 2026.10  5557.5 2027.77  5572.1 2027.21
#Mann=3,-1,0
  4239.8    0.07       0  4987.9    0.07       0  4998.9    0.07       0
Bank Sta=4987.9,4998.9
Exp/Cntr=0.3,0.1

Type RM Length L Ch R = 1,18940,417,417,417
BEGIN DESCRIPTION:
Plum Creek Trib4 22.0
END DESCRIPTION:
XS GIS Cut Line= 3
      1392555.01      6905538.00      1392955.00      6905638.00
      1393631.26      6905797.44
#Sta/Elev= 30
  4583.3 2034.48  4585.9 2034.48  4593.6 2031.66  4601.3 2030.70  4624.5 2029.69
  4634.8 2029.87  4642.6 2031.29  4647.7 2031.00  4655.4 2028.38  4676.1 2026.45
  4688.9 2025.93  4707.0 2027.76  4717.3 2025.24  4737.9 2023.59  4758.5 2023.52
  4771.4 2024.81  4779.1 2022.96  4789.4 2022.36  4902.8 2019.53  4936.3 2018.11
  4977.6 2014.43  5020.8 2013.34  5021.3 2012.84  5032.0 2013.34  5061.7 2015.51
  5160.0 2016.07  5278.5 2020.11  5386.0 2020.76  5437.4 2022.77  5690.4 2028.10
#Mann=3,-1,0
  4583.3    0.07       0  5020.8    0.07       0  5032.0    0.07       0
Bank Sta=5020.8,5032
Exp/Cntr=0.3,0.1

Type RM Length L Ch R = 1,18523,504,504,504
BEGIN DESCRIPTION:
Plum Creek Trib4 21.0
END DESCRIPTION:
XS GIS Cut Line= 3
      1392455.03      6905638.03      1392855.00      6905988.00
      1393505.01      6905938.00
#Sta/Elev= 30
  4468.0 2038.18  4510.2 2034.43  4532.0 2034.62  4546.3 2032.24  4574.3 2030.09
  4588.0 2029.62  4602.3 2030.36  4609.9 2028.03  4630.7 2026.30  4652.6 2027.49
  4666.8 2023.97  4694.3 2024.58  4701.9 2023.26  4716.2 2022.27  4843.3 2019.53
  4865.2 2019.82  4928.8 2014.75  4957.2 2013.71  4971.5 2014.07  4992.4 2011.60
  5019.5 2012.07  5044.0 2011.53  5044.5 2011.03  5055.3 2011.53  5139.9 2014.58
  5159.9 2013.98  5200.1 2015.35  5230.1 2015.47  5330.4 2019.36  5651.4 2026.96
#Mann=3,-1,0
  4468.0    0.07       0  5044.0    0.07       0  5055.3    0.07       0
Bank Sta=5044,5055.3
Exp/Cntr=0.3,0.1

Type RM Length L Ch R = 1,18019,610,610,610
BEGIN DESCRIPTION:
Plum Creek Trib4 20.0
END DESCRIPTION:
XS GIS Cut Line= 4
      1392204.97      6905887.99      1392907.26      6906292.40
      1392992.32      6906333.76      1393578.28      6906190.53
#Sta/Elev= 30
  4189.6 2035.34  4240.6 2031.86  4270.4 2032.50  4305.3 2028.67  4336.9 2029.14
  4374.2 2025.35  4395.8 2026.16  4423.1 2022.79  4460.5 2023.18  4497.8 2020.08
  4525.2 2021.00  4547.4 2017.95  4556.7 2018.70  4562.5 2017.33  4593.5 2016.89
  4658.8 2012.26  4986.4 2012.13  5036.1 2009.42  5036.6 2008.92  5047.4 2009.42
  5053.1 2011.81  5075.4 2013.64  5141.8 2014.94  5350.0 2026.86  5365.0 2026.32
  5406.2 2028.69  5475.0 2030.14  5550.3 2030.08  5581.2 2032.11  5697.8 2031.90
#Mann=3,-1,0
  4189.6    0.07       0  5036.1    0.07       0  5047.4    0.07       0
Bank Sta=5036.1,5047.4
Exp/Cntr=0.3,0.1

Type RM Length L Ch R = 1,17409,509,509,509
BEGIN DESCRIPTION:
Mapping XS f9800cb8
END DESCRIPTION:
XS GIS Cut Line= 4
      1392089.50      6906151.46      1392412.89      6906229.60
      1392712.37      6906437.93      1393469.78      6906238.27
#Sta/Elev= 30
  4666.0 2031.80  4711.4 2032.99  4753.3 2032.86  4800.3 2031.29  4826.0 2031.53
  4842.1 2029.35  4877.4 2029.73  4925.9 2019.45  4931.0 2017.47  4959.7 2012.98
  4967.2 2008.73  4967.7 2008.23  4978.6 2008.73  4980.3 2009.77  5006.0 2010.83
  5244.3 2013.26  5322.0 2012.07  5397.3 2009.06  5422.6 2010.13  5457.7 2009.76
  5573.1 2013.34  5613.7 2015.63  5654.0 2016.46  5659.2 2015.79  5739.8 2018.18
  5976.4 2029.67  6038.4 2030.80  6100.5 2030.23  6121.2 2032.29  6146.8 2032.17
#Mann=3,-1,0
  4666.0    0.07       0  4967.2    0.07       0  4978.6    0.07       0
Bank Sta=4967.2,4978.6
Exp/Cntr=0.3,0.1