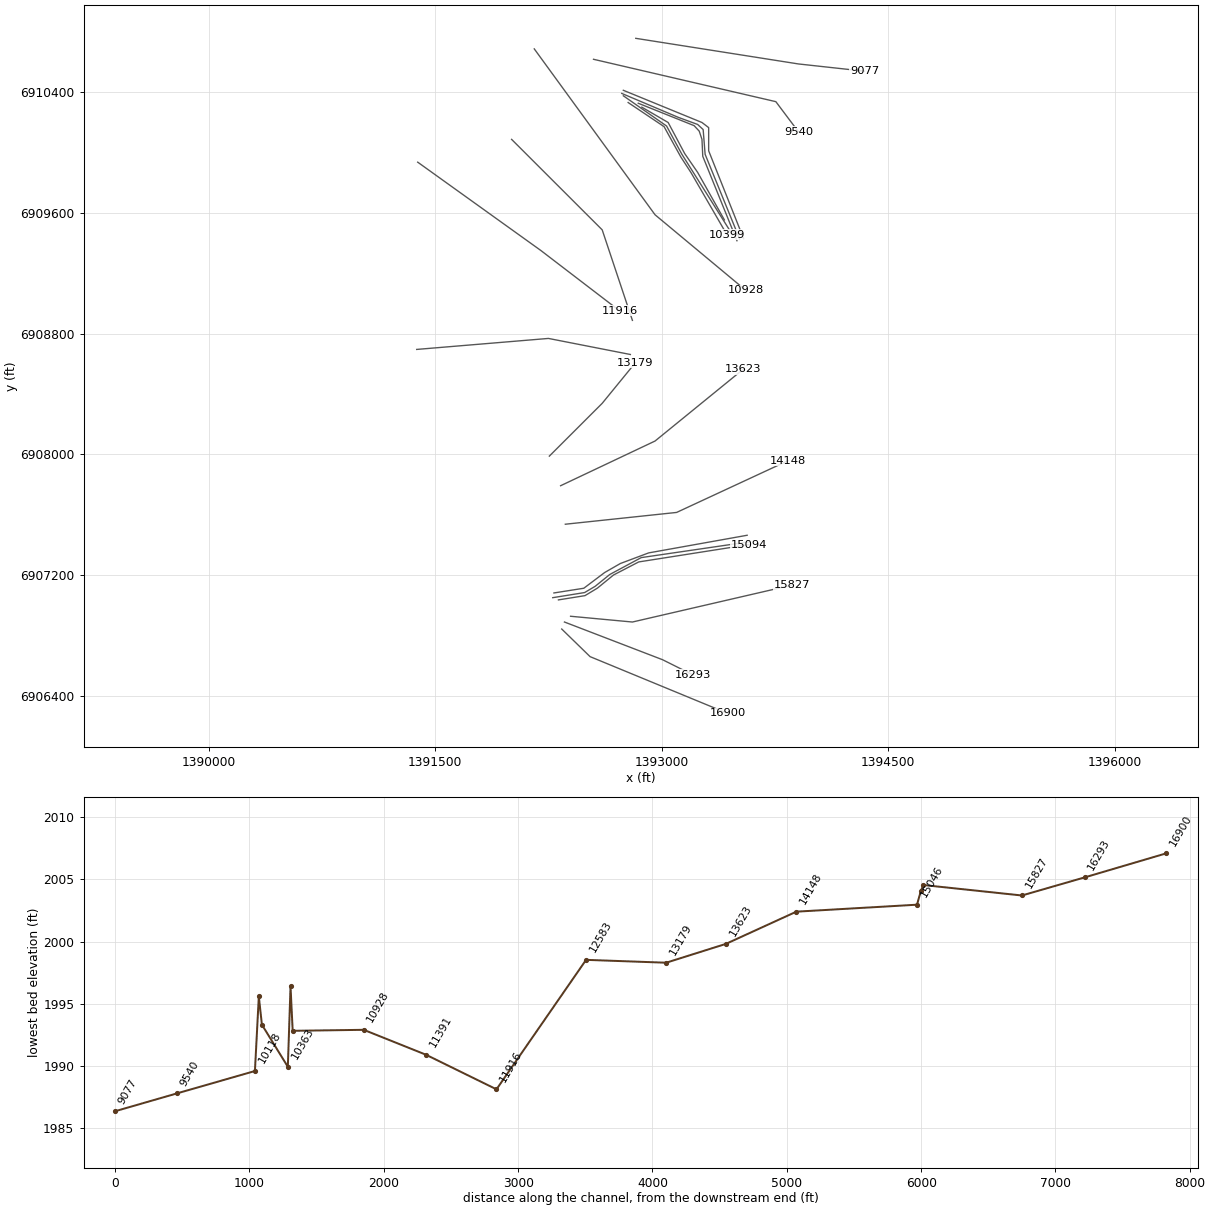
HEC-RAS study Plum Creek Trib4.prj: Plum Creek Trib4 Base Level Engineering

--- Plum Creek Trib4.g01 (geometry) --- (continued)

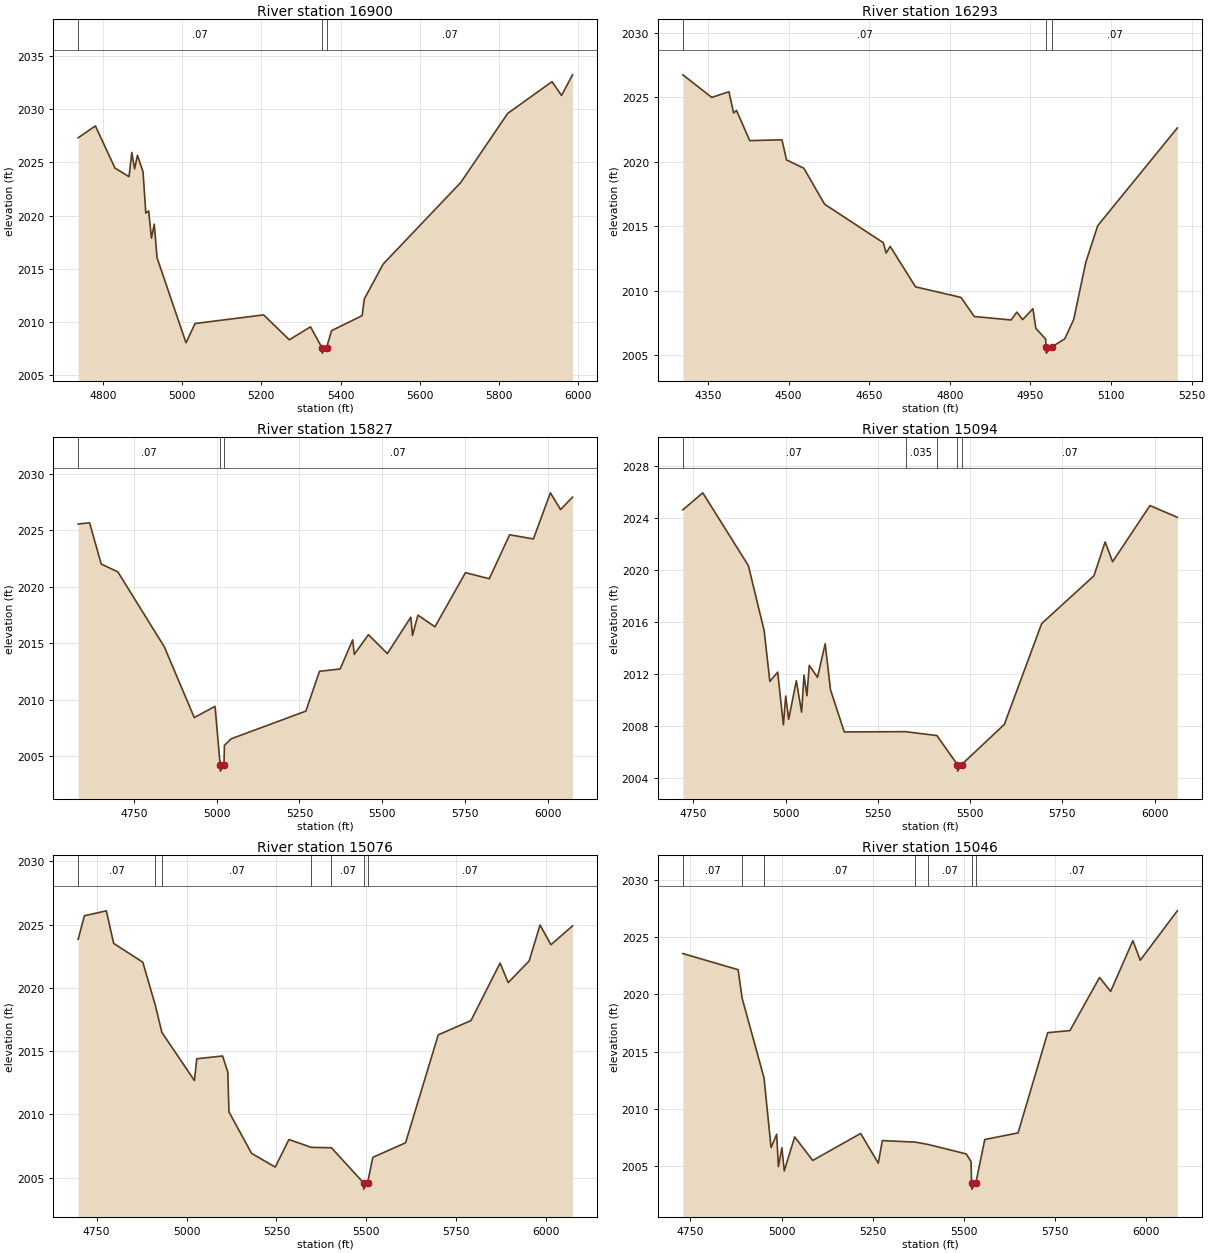
Type RM Length L Ch R = 1,16900,607,607,607
BEGIN DESCRIPTION:
Plum Creek Trib4 19.0
END DESCRIPTION:
XS GIS Cut Line= 3
      1392336.97      6906841.55      1392524.72      6906658.52
      1393435.60      6906282.34
#Sta/Elev= 30
  4737.8 2027.30  4781.3 2028.41  4830.9 2024.45  4866.2 2023.65  4873.3 2025.92
  4880.3 2024.38  4887.5 2025.65  4901.6 2024.10  4908.6 2020.23  4915.8 2020.43
  4922.8 2017.88  4929.9 2019.19  4936.9 2016.04  5010.1 2008.05  5032.8 2009.86
  5205.9 2010.67  5270.8 2008.33  5324.2 2009.55  5353.2 2007.58  5353.7 2007.08
  5364.6 2007.58  5377.4 2009.19  5454.6 2010.60  5460.0 2012.17  5507.8 2015.45
  5703.6 2023.11  5821.9 2029.59  5933.8 2032.57  5957.7 2031.27  5985.5 2033.21
#Mann=3,-1,0
  4737.8    0.07       0  5353.2    0.07       0  5364.6    0.07       0
Bank Sta=5353.2,5364.6
Exp/Cntr=0.3,0.1

Type RM Length L Ch R = 1,16293,466,466,466
BEGIN DESCRIPTION:
Plum Creek Trib4 18.0
END DESCRIPTION:
XS GIS Cut Line= 3
      1392354.98      6906888.01      1393005.00      6906638.00
      1393204.96      6906538.02
#Sta/Elev= 30
  4303.2 2026.73  4356.8 2024.98  4388.9 2025.42  4397.5 2023.77  4402.9 2023.97
  4427.5 2021.63  4487.5 2021.69  4496.1 2020.13  4528.2 2019.49  4566.8 2016.70
  4676.1 2013.71  4681.4 2012.91  4688.9 2013.43  4736.1 2010.29  4820.7 2009.47
  4845.4 2007.99  4913.9 2007.72  4924.6 2008.33  4935.4 2007.75  4954.6 2008.59
  4960.0 2007.07  4978.2 2006.24  4978.9 2005.65  4979.4 2005.15  4990.3 2005.65
  5013.6 2006.25  5030.4 2007.75  5052.7 2012.16  5075.1 2015.03  5223.2 2022.61
#Mann=3,-1,0
  4303.2    0.07       0  4978.9    0.07       0  4990.3    0.07       0
Bank Sta=4978.9,4990.3
Exp/Cntr=0.3,0.1

Type RM Length L Ch R = 1,15827,733,733,733
BEGIN DESCRIPTION:
Plum Creek Trib4 17.0
END DESCRIPTION:
XS GIS Cut Line= 3
      1392395.51      6906926.21      1392805.00      6906888.00
      1393860.21      6907132.34
#Sta/Elev= 30
  4581.0 2025.56  4615.6 2025.67  4650.8 2022.02  4701.0 2021.33  4841.6 2014.69
  4932.0 2008.44  4994.8 2009.43  5010.5 2004.20  5011.0 2003.70  5021.9 2004.20
  5023.1 2005.98  5043.6 2006.56  5269.4 2009.01  5310.5 2012.53  5373.1 2012.74
  5410.7 2015.31  5415.8 2014.03  5458.5 2015.77  5515.8 2014.10  5586.6 2017.32
  5591.7 2015.70  5608.1 2017.50  5659.5 2016.47  5751.8 2021.26  5823.7 2020.72
  5885.3 2024.61  5957.1 2024.24  6008.5 2028.32  6039.3 2026.84  6075.4 2027.94
#Mann=3,-1,0
  4581.0    0.07       0  5010.5    0.07       0  5021.9    0.07       0
Bank Sta=5010.5,5021.9
Exp/Cntr=0.3,0.1

Type RM Length L Ch R = 1,15094,18,18,18
BEGIN DESCRIPTION:
Mapping XS 7b184632
END DESCRIPTION:
XS GIS Cut Line= 6
      1392315.25      6907034.72      1392491.02      6907062.93
      1392573.48      6907112.84      1392679.82      6907199.65
      1392846.92      6907286.45      1393578.25      6907401.47
#Sta/Elev= 30
  4721.4 2024.61  4775.3 2025.91  4898.9 2020.32  4941.6 2015.33  4957.1 2011.43
  4978.4 2012.14  4993.8 2008.09  5000.1 2010.31  5008.1 2008.52  5028.9 2011.48
  5043.2 2009.07  5049.7 2011.91  5057.6 2010.33  5064.0 2012.66  5086.3 2011.74
  5107.1 2014.32  5121.5 2010.78  5158.9 2007.55  5325.0 2007.57  5410.0 2007.27
  5465.6 2005.04  5466.1 2004.54  5477.0 2005.04  5592.8 2008.13  5694.0 2015.87
  5835.7 2019.54  5866.1 2022.14  5886.3 2020.62  5987.6 2024.93  6061.7 2024.03
#Mann=5,-1,0
  4721.4    0.07       0  5325.0   0.035       0  5410.0    0.07       0
  5465.6    0.07       0  5477.0    0.07       0
Bank Sta=5465.6,5477
Exp/Cntr=0.3,0.1

Type RM Length L Ch R = 1,15076,30,30,30
BEGIN DESCRIPTION:
Mapping XS 16a8a3eb
END DESCRIPTION:
XS GIS Cut Line= 6
      1392277.51      6907049.48      1392488.41      6907083.33
      1392558.73      6907124.99      1392655.08      6907203.12
      1392863.41      6907315.10      1393574.32      6907419.26
#Sta/Elev= 30
  4698.6 2023.83  4716.0 2025.70  4777.1 2026.09  4797.3 2023.52  4878.4 2022.03
  4913.6 2018.58  4931.3 2016.49  5021.9 2012.68  5028.4 2014.40  5100.2 2014.62
  5114.6 2013.36  5117.9 2010.20  5180.7 2006.93  5246.5 2005.84  5284.6 2008.02
  5346.8 2007.40  5402.7 2007.37  5491.9 2004.60  5492.4 2004.10  5503.3 2004.60
  5517.8 2006.61  5608.8 2007.76  5699.7 2016.29  5790.7 2017.42  5871.6 2021.96
  5894.3 2020.42  5952.4 2022.13  5982.7 2024.97  6013.0 2023.41  6073.0 2024.90
#Mann=7,-1,0
  4698.6    0.07       0  4913.6   0.035       0  4931.3    0.07       0
  5346.8   0.035       0  5402.7    0.07       0  5491.9    0.07       0
  5503.3    0.07       0
Bank Sta=5491.9,5503.3
Exp/Cntr=0.3,0.1

Type RM Length L Ch R = 1,15046,898,898,898
BEGIN DESCRIPTION:
Mapping XS 0f0805e0
END DESCRIPTION:
XS GIS Cut Line= 6
      1392285.32      6907080.73      1392483.21      6907111.97
      1392621.23      6907216.14      1392725.39      6907276.04
      1392912.89      6907346.35      1393565.00      6907463.26
#Sta/Elev= 30
  4729.3 2023.57  4880.8 2022.16  4891.7 2019.68  4951.9 2012.69  4971.2 2006.60
  4986.6 2007.76  4991.3 2004.93  5000.9 2006.58  5007.4 2004.55  5036.0 2007.53
  5085.5 2005.47  5217.0 2007.83  5265.4 2005.23  5276.5 2007.21  5367.5 2007.07
  5402.2 2006.87  5506.8 2006.04  5519.9 2005.37  5521.4 2003.46  5521.9 2002.96
  5532.8 2003.46  5557.6 2007.30  5649.0 2007.88  5730.3 2016.65  5791.3 2016.83
  5872.6 2021.48  5903.0 2020.26  5964.0 2024.70  5984.3 2022.99  6085.9 2027.31
#Mann=7,-1,0
  4729.3    0.07       0  4891.7   0.035       0  4951.9    0.07       0
  5367.5   0.035       0  5402.2    0.07       0  5521.4    0.07       0
  5532.8    0.07       0
Bank Sta=5521.4,5532.8
Exp/Cntr=0.3,0.1

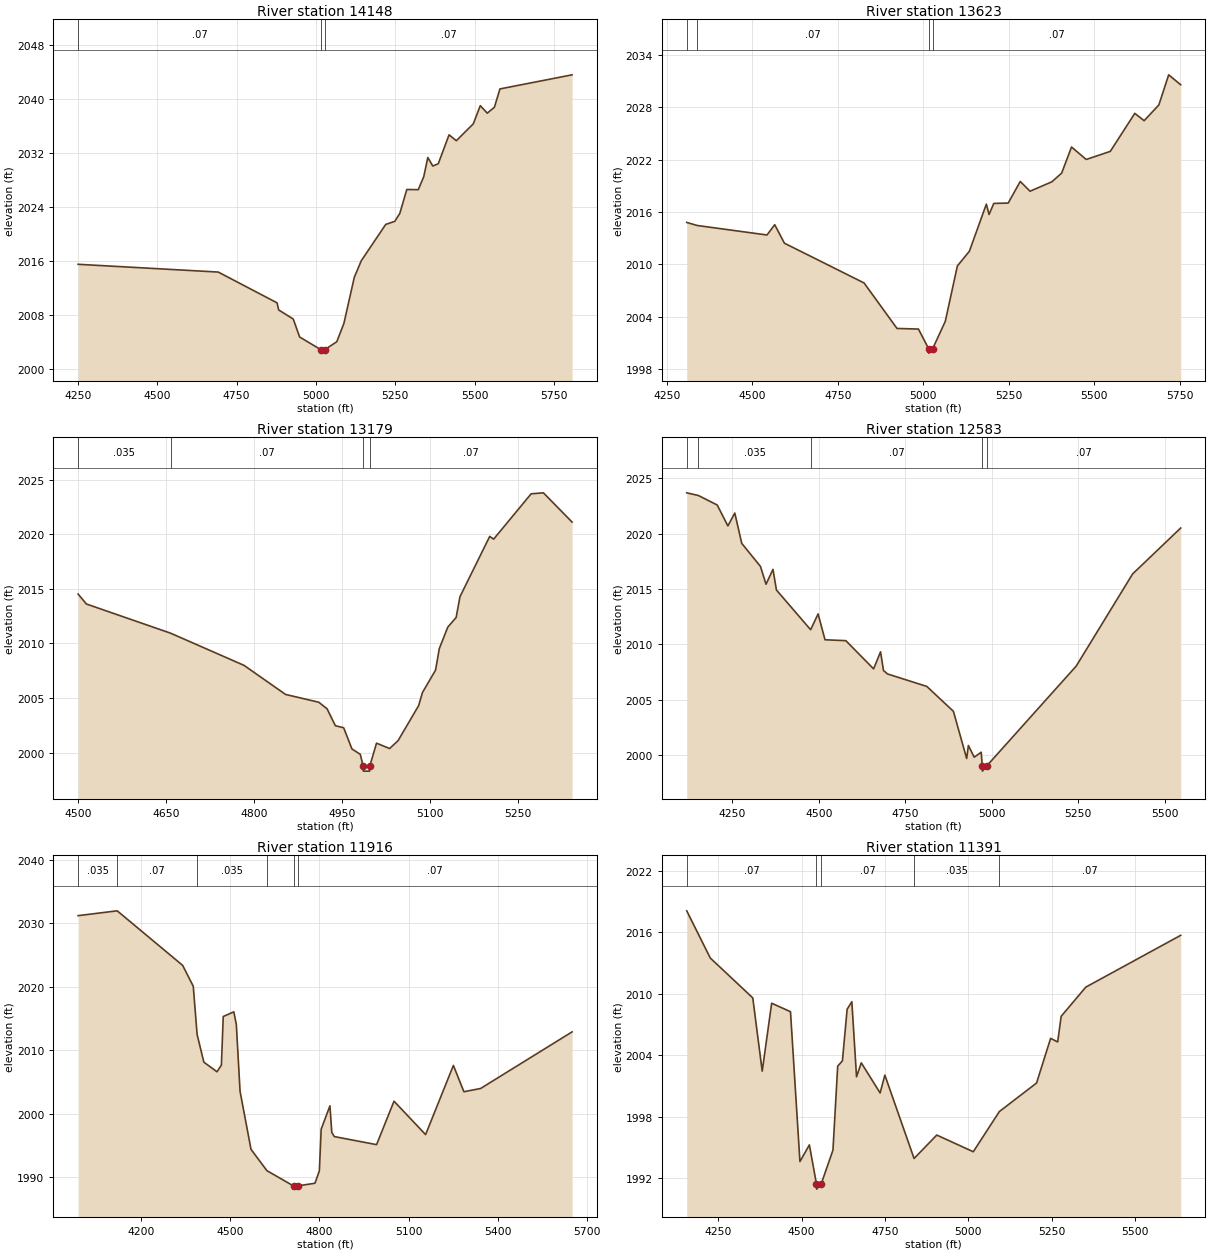
Type RM Length L Ch R = 1,14148,525,525,525
BEGIN DESCRIPTION:
Mapping XS 70f34461
END DESCRIPTION:
XS GIS Cut Line= 3
      1392360.79      6907536.45      1393097.79      6907614.58
      1393837.37      6907958.33
#Sta/Elev= 30
  4250.4 2015.56  4692.0 2014.41  4877.4 2009.85  4882.4 2008.80  4928.4 2007.45
  4948.5 2004.79  5015.7 2002.90  5016.2 2002.40  5027.3 2002.90  5065.6 2004.09
  5088.0 2006.81  5120.8 2013.64  5142.8 2016.09  5219.8 2021.47  5248.2 2021.92
  5264.1 2023.09  5286.2 2026.64  5322.4 2026.62  5339.7 2028.55  5352.4 2031.38
  5368.1 2030.12  5385.4 2030.46  5419.4 2034.74  5442.3 2033.87  5495.7 2036.37
  5517.8 2039.06  5539.8 2037.95  5562.3 2038.83  5579.7 2041.54  5807.1 2043.63
#Mann=3,-1,0
  4250.4    0.07       0  5015.7    0.07       0  5027.3    0.07       0
Bank Sta=5015.7,5027.3
Exp/Cntr=0.3,0.1

Type RM Length L Ch R = 1,13623,444,444,444
BEGIN DESCRIPTION:
Plum Creek Trib4 15.0
END DESCRIPTION:
XS GIS Cut Line= 3
      1392329.54      6907791.65      1392955.00      6908088.00
      1393538.96      6908563.85
#Sta/Elev= 30
  4307.6 2014.80  4338.2 2014.45  4542.4 2013.36  4565.1 2014.54  4593.4 2012.42
  4826.4 2007.86  4922.9 2002.64  4985.6 2002.57  5015.5 2000.31  5016.0 1999.81
  5027.1 2000.31  5064.2 2003.46  5099.5 2009.81  5134.7 2011.50  5184.3 2016.90
  5192.2 2015.71  5206.1 2016.98  5248.2 2017.02  5283.5 2019.50  5312.1 2018.38
  5376.0 2019.46  5404.7 2020.46  5433.5 2023.45  5476.5 2022.02  5546.9 2022.95
  5618.7 2027.31  5646.0 2026.47  5689.1 2028.28  5717.8 2031.73  5753.0 2030.59
#Mann=4,-1,0
  4307.6   0.035       0  4338.2    0.07       0  5015.5    0.07       0
  5027.1    0.07       0
Bank Sta=5015.5,5027.1
Exp/Cntr=0.3,0.1

Type RM Length L Ch R = 1,13179,596,596,596
BEGIN DESCRIPTION:
Plum Creek Trib4 14.0
END DESCRIPTION:
XS GIS Cut Line= 3
      1392254.98      6907987.98      1392605.00      6908338.00
      1392824.34      6908606.75
#Sta/Elev= 30
  4500.2 2014.51  4514.4 2013.60  4657.8 2010.93  4783.1 2007.98  4853.8 2005.32
  4910.3 2004.61  4924.5 2004.01  4938.6 2002.46  4952.8 2002.27  4966.9 2000.33
  4981.1 1999.84  4985.8 1998.80  4986.3 1998.30  4997.0 1998.30  4997.5 1998.80
  5008.8 2000.86  5031.1 2000.37  5045.5 2001.09  5080.6 2004.30  5087.1 2005.50
  5109.4 2007.55  5115.8 2009.52  5130.2 2011.48  5144.5 2012.37  5151.0 2014.27
  5201.7 2019.79  5208.4 2019.54  5272.3 2023.69  5293.2 2023.78  5342.1 2021.10
#Mann=4,-1,0
  4500.2   0.035       0  4657.8    0.07       0  4985.8    0.07       0
  4997.5    0.07       0
Bank Sta=4985.8,4997.5
Exp/Cntr=0.3,0.1

Type RM Length L Ch R = 1,12583,667,667,667
BEGIN DESCRIPTION:
Mapping XS de2430fd
END DESCRIPTION:
XS GIS Cut Line= 3
      1391376.46      6908695.31      1392248.83      6908768.22
      1392791.57      6908661.75
#Sta/Elev= 30
  4118.3 2023.70  4151.9 2023.46  4206.4 2022.60  4237.3 2020.71  4257.3 2021.87
  4277.4 2019.13  4331.6 2017.04  4347.6 2015.43  4367.7 2016.78  4377.7 2014.91
  4476.6 2011.32  4498.2 2012.75  4518.2 2010.41  4578.4 2010.33  4658.7 2007.78
  4678.8 2009.32  4687.3 2007.63  4698.9 2007.32  4812.6 2006.19  4889.5 2003.94
  4927.8 1999.67  4932.8 2000.85  4949.7 1999.79  4969.8 2000.24  4972.9 1999.03
  4973.4 1998.53  4986.7 1999.03  5244.6 2008.03  5407.6 2016.36  5546.8 2020.52
#Mann=5,-1,0
  4118.3    0.07       0  4151.9   0.035       0  4476.6    0.07       0
  4972.9    0.07       0  4986.7    0.07       0
Bank Sta=4972.9,4986.7
Exp/Cntr=0.3,0.1

Type RM Length L Ch R = 1,11916,525,525,525
BEGIN DESCRIPTION:
Mapping XS f0e4dbee
END DESCRIPTION:
XS GIS Cut Line= 3
      1391383.17      6909936.84      1392199.13      6909350.91
      1392719.07      6908952.29
#Sta/Elev= 30
  3989.1 2031.17  4120.5 2031.93  4340.4 2023.34  4376.0 2020.06  4388.9 2012.47
  4411.6 2008.11  4455.8 2006.60  4470.5 2007.65  4476.7 2015.30  4512.3 2016.03
  4520.7 2014.04  4533.2 2003.53  4570.0 1994.39  4623.6 1991.03  4712.9 1988.63
  4713.4 1988.13  4726.7 1988.63  4784.9 1989.06  4799.6 1991.00  4805.8 1997.57
  4835.2 2001.24  4841.4 1997.06  4849.9 1996.40  4991.9 1995.13  5050.5 2001.97
  5156.6 1996.71  5250.0 2007.60  5285.3 2003.46  5341.5 2003.97  5648.8 2012.88
#Mann=6,-1,0
  3989.1   0.035       0  4120.5    0.07       0  4388.9   0.035       0
  4623.6    0.07       0  4712.9    0.07       0  4726.7    0.07       0
Bank Sta=4712.9,4726.7
Exp/Cntr=0.3,0.1

Type RM Length L Ch R = 1,11391,463,463,463
BEGIN DESCRIPTION:
Plum Creek Trib4 11.0
END DESCRIPTION:
XS GIS Cut Line= 3
      1392004.99      6910088.01      1392605.00      6909488.00
      1392805.00      6908888.00
#Sta/Elev= 30
  4155.9 2018.08  4226.6 2013.47  4353.9 2009.58  4382.2 2002.43  4410.5 2009.06
  4467.0 2008.23  4495.3 1993.60  4523.6 1995.23  4544.9 1991.41  4545.4 1990.91
  4559.0 1991.41  4594.3 1994.72  4608.5 2002.92  4622.6 2003.43  4636.8 2008.47
  4650.9 2009.21  4665.0 2001.88  4679.2 2003.24  4735.7 2000.30  4749.9 2002.04
  4837.5 1993.90  4905.5 1996.19  5015.0 1994.56  5093.1 1998.48  5204.7 2001.27
  5246.9 2005.63  5268.0 2005.28  5278.5 2007.78  5352.3 2010.63  5636.9 2015.69
#Mann=5,-1,0
  4155.9    0.07       0  4544.9   0.035       0  4559.0    0.07       0
  4837.5   0.035       0  5093.1    0.07       0
Bank Sta=4544.9,4559
Exp/Cntr=0.3,0.1

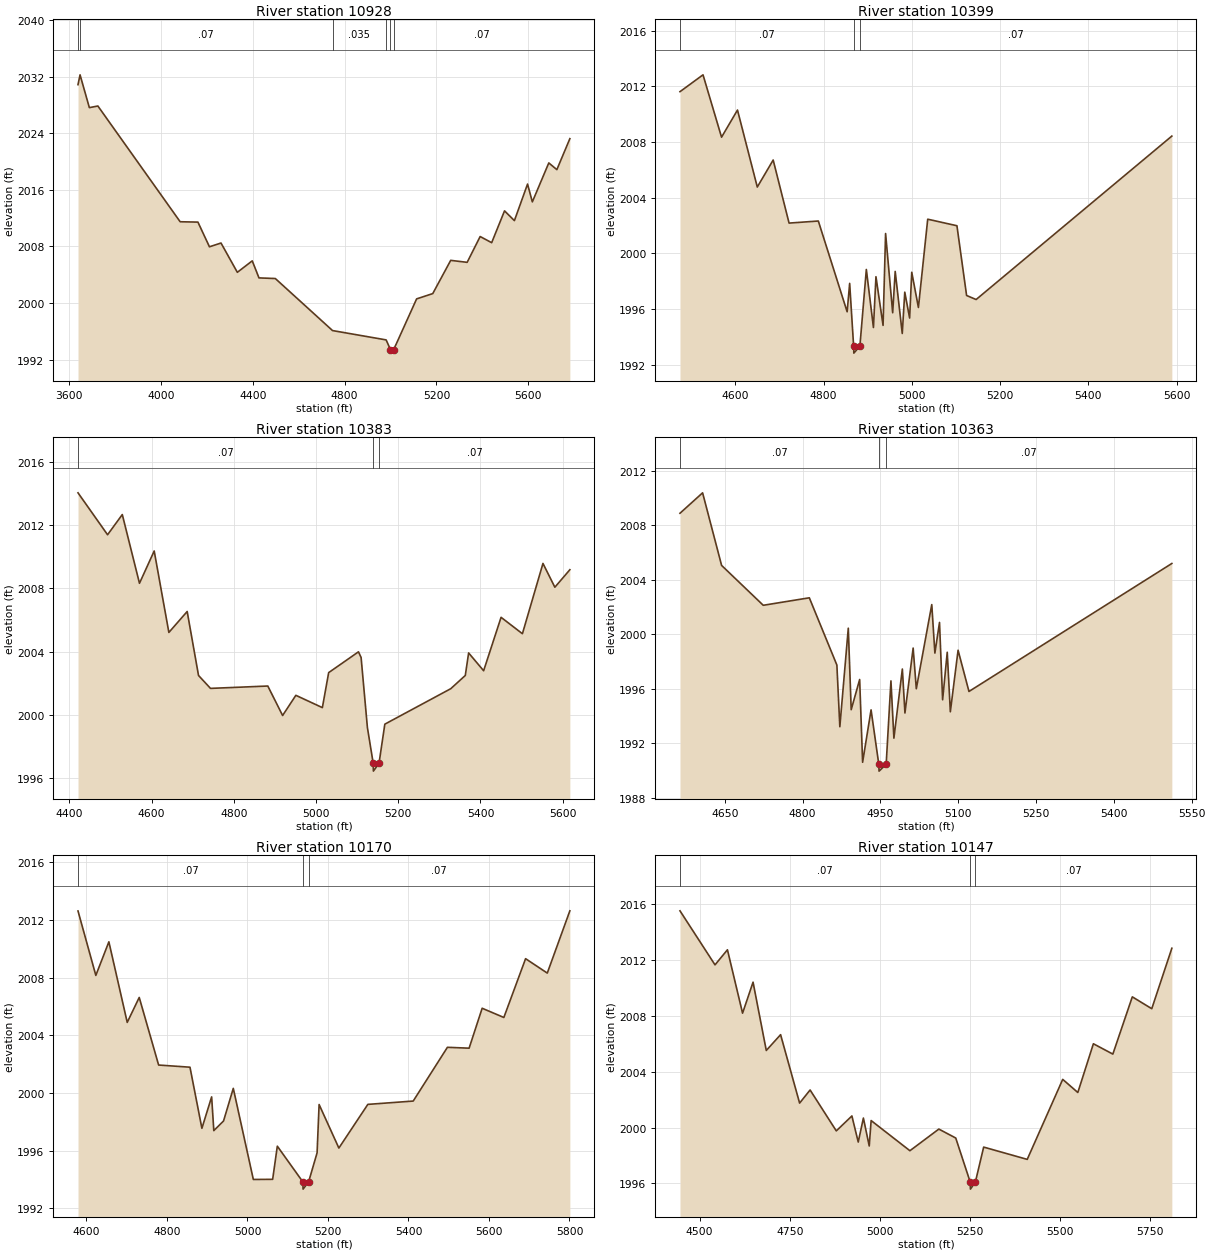
Type RM Length L Ch R = 1,10928,529,529,529
BEGIN DESCRIPTION:
Plum Creek Trib4 10.0
END DESCRIPTION:
XS GIS Cut Line= 3
      1392155.02      6910687.97      1392955.00      6909588.00
      1393554.97      6909088.02
#Sta/Elev= 30
  3639.6 2030.88  3648.5 2032.27  3689.0 2027.63  3726.1 2027.86  4084.3 2011.49
  4161.6 2011.44  4211.8 2007.95  4262.1 2008.48  4333.2 2004.34  4398.1 2005.96
  4427.4 2003.55  4498.5 2003.46  4747.6 1996.10  4980.9 1994.78  4999.8 1993.41
  5000.3 1992.91  5013.9 1993.41  5113.6 2000.58  5183.9 2001.33  5262.0 2006.03
  5333.6 2005.75  5390.2 2009.40  5440.3 2008.53  5496.3 2013.03  5539.3 2011.65
  5596.5 2016.82  5617.4 2014.30  5689.0 2019.81  5724.1 2018.86  5780.7 2023.24
#Mann=6,-1,0
  3639.6   0.035       0  3648.5    0.07       0  4747.6   0.035       0
  4980.9    0.07       0  4999.8    0.07       0  5013.9    0.07       0
Bank Sta=4999.8,5013.9
Exp/Cntr=0.3,0.1

Type RM Length L Ch R = 1,10399,16,16,16
BEGIN DESCRIPTION:
Mapping XS e03ace39
END DESCRIPTION:
XS GIS Cut Line= 5
      1392776.84      6910332.23      1393014.67      6910172.52
      1393125.78      6909971.13      1393193.49      6909866.97
      1393430.65      6909456.70
#Sta/Elev= 30
  4474.7 2011.61  4526.9 2012.82  4568.9 2008.34  4605.0 2010.29  4649.9 2004.76
  4685.9 2006.70  4721.9 2002.17  4788.2 2002.32  4853.5 1995.80  4859.2 1997.84
  4868.2 1993.33  4868.7 1992.83  4882.4 1993.33  4897.0 1998.84  4913.1 1994.67
  4918.8 1998.32  4934.9 1994.82  4940.6 2001.42  4956.7 1995.73  4962.4 1998.70
  4978.4 1994.24  4984.1 1997.21  4995.1 1995.35  4999.9 1998.64  5015.0 1996.11
  5036.1 2002.45  5102.3 2001.98  5124.2 1996.97  5145.8 1996.68  5589.3 2008.42
#Mann=3,-1,0
  4474.7    0.07       0  4868.2    0.07       0  4882.4    0.07       0
Bank Sta=4868.2,4882.4
Exp/Cntr=0.3,0.1

Type RM Length L Ch R = 1,10383,20,20,20
BEGIN DESCRIPTION:
Mapping XS 7693472b
END DESCRIPTION:
XS GIS Cut Line= 4
      1392744.92      6910376.95      1393031.38      6910176.43
      1393132.95      6909988.93      1393469.75      6909452.63
#Sta/Elev= 30
  4421.2 2014.07  4493.1 2011.41  4528.9 2012.69  4570.7 2008.33  4606.5 2010.38
  4642.2 2005.21  4686.7 2006.54  4714.3 2002.48  4743.4 2001.66  4882.8 2001.81
  4918.8 1999.94  4951.0 2001.22  5015.5 2000.44  5030.8 2002.66  5103.3 2003.98
  5109.7 2003.62  5125.0 1999.18  5139.1 1996.91  5139.6 1996.41  5153.3 1996.91
  5167.4 1999.39  5327.7 2001.64  5363.1 2002.48  5371.2 2003.91  5407.7 2002.78
  5450.1 2006.17  5502.0 2005.13  5552.0 2009.59  5580.9 2008.08  5617.4 2009.19
#Mann=3,-1,0
  4421.2    0.07       0  5139.1    0.07       0  5153.3    0.07       0
Bank Sta=5139.1,5153.3
Exp/Cntr=0.3,0.1

Type RM Length L Ch R = 1,10363,193,193,193
BEGIN DESCRIPTION:
Mapping XS deacd4e4
END DESCRIPTION:
XS GIS Cut Line= 5
      1392867.34      6910301.42      1393041.80      6910199.86
      1393151.17      6909994.14      1393237.11      6909869.14
      1393414.19      6909554.04
#Sta/Elev= 30
  4563.8 2008.88  4607.4 2010.38  4644.0 2005.05  4724.3 2002.12  4813.1 2002.67
  4866.2 1997.73  4871.9 1993.20  4888.2 2000.44  4893.8 1994.45  4910.1 1996.67
  4915.8 1990.59  4932.1 1994.44  4947.0 1990.44  4947.5 1989.94  4961.2 1990.44
  4970.4 1996.57  4976.1 1992.36  4992.4 1997.44  4997.4 1994.21  5013.2 1998.98
  5019.3 1995.99  5049.1 2002.17  5055.1 1998.61  5064.0 2000.86  5070.0 1995.18
  5078.9 1998.67  5084.9 1994.30  5099.8 1998.82  5120.8 1995.79  5511.8 2005.19
#Mann=3,-1,0
  4563.8    0.07       0  4947.0    0.07       0  4961.2    0.07       0
Bank Sta=4947,4961.2
Exp/Cntr=0.3,0.1

Type RM Length L Ch R = 1,10170,23,23,23
BEGIN DESCRIPTION:
Mapping XS 3a6b3cc2
END DESCRIPTION:
XS GIS Cut Line= 6
      1392843.86      6910327.48      1393213.67      6910179.03
      1393247.53      6910142.57      1393265.76      6910087.89
      1393270.97      6909975.91      1393497.53      6909416.01
#Sta/Elev= 30
  4579.0 2012.62  4623.3 2008.15  4655.7 2010.48  4701.3 2004.89  4731.1 2006.62
  4779.3 2001.93  4857.2 2001.78  4886.8 1997.54  4911.0 1999.72  4916.4 1997.38
  4940.6 1998.05  4964.8 2000.31  5014.6 1993.99  5062.6 1994.00  5074.2 1996.30
  5137.7 1993.82  5138.2 1993.32  5151.9 1993.82  5173.0 1995.84  5178.0 1999.19
  5227.1 1996.17  5299.1 1999.20  5411.8 1999.43  5496.8 2003.16  5550.7 2003.10
  5583.1 2005.87  5637.0 2005.23  5691.0 2009.31  5744.9 2008.31  5801.0 2012.63
#Mann=3,-1,0
  4579.0    0.07       0  5137.7    0.07       0  5151.9    0.07       0
Bank Sta=5137.7,5151.9
Exp/Cntr=0.3,0.1

Type RM Length L Ch R = 1,10147,29,29,29
BEGIN DESCRIPTION:
Mapping XS 06e642e8
END DESCRIPTION:
XS GIS Cut Line= 6
      1392734.47      6910392.59      1393109.51      6910233.72
      1393237.11      6910186.84      1393273.57      6910152.99
      1393286.59      6909988.93      1393515.77      6909426.40
#Sta/Elev= 30
  4445.4 2015.52  4542.6 2011.65  4577.1 2012.73  4619.1 2008.19  4648.2 2010.41
  4684.9 2005.52  4724.6 2006.65  4777.4 2001.75  4806.5 2002.69  4879.2 1999.76
  4922.5 2000.83  4940.1 1998.96  4954.4 2000.68  4970.6 1998.68  4975.9 2000.50
  5083.5 1998.34  5163.8 1999.89  5210.7 1999.25  5250.9 1996.09  5251.4 1995.59
  5265.1 1996.09  5288.2 1998.60  5409.1 1997.72  5507.6 2003.45  5549.5 2002.51
  5592.7 2006.00  5646.7 2005.26  5700.7 2009.36  5754.7 2008.51  5810.4 2012.84
#Mann=3,-1,0
  4445.4    0.07       0  5250.9    0.07       0  5265.1    0.07       0
Bank Sta=5250.9,5265.1
Exp/Cntr=0.3,0.1

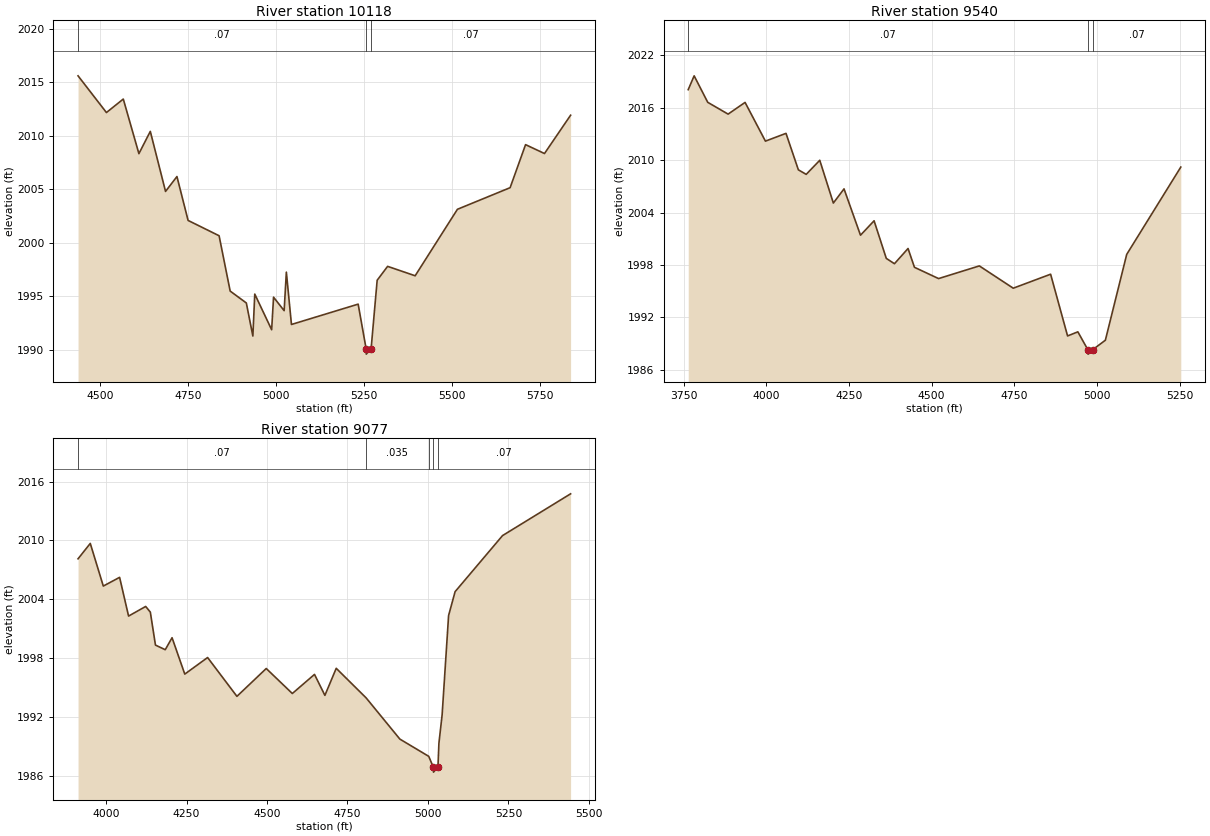
Type RM Length L Ch R = 1,10118,578,578,578
BEGIN DESCRIPTION:
Mapping XS 8e4c335f
END DESCRIPTION:
XS GIS Cut Line= 5
      1392744.91      6910413.41      1393265.76      6910199.86
      1393310.03      6910166.01      1393310.03      6910012.36
      1393541.80      6909429.03
#Sta/Elev= 30
  4436.8 2015.60  4517.5 2012.17  4565.4 2013.43  4609.8 2008.33  4642.2 2010.41
  4685.5 2004.80  4717.9 2006.19  4749.6 2002.09  4837.7 2000.66  4869.2 1995.49
  4915.1 1994.38  4933.7 1991.29  4939.1 1995.21  4987.1 1991.88  4992.5 1994.92
  5022.6 1993.66  5028.9 1997.26  5043.4 1992.37  5233.0 1994.27  5255.6 1990.10
  5256.1 1989.60  5269.8 1990.10  5287.0 1996.50  5316.7 1997.80  5395.0 1996.92
  5515.1 2003.13  5664.9 2005.15  5708.8 2009.17  5762.6 2008.34  5836.8 2011.92
#Mann=3,-1,0
  4436.8    0.07       0  5255.6    0.07       0  5269.8    0.07       0
Bank Sta=5255.6,5269.8
Exp/Cntr=0.3,0.1

Type RM Length L Ch R = 1,9540,463,463,463
BEGIN DESCRIPTION:
Plum Creek Trib4 7.0
END DESCRIPTION:
XS GIS Cut Line= 3
      1392547.53      6910618.96      1393755.00      6910338.00
      1393904.98      6910138.02
#Sta/Elev= 30
  3763.9 2018.06  3781.8 2019.64  3822.9 2016.61  3884.5 2015.26  3935.8 2016.60
  3997.4 2012.17  4059.6 2013.06  4097.0 2008.89  4120.7 2008.37  4161.7 2009.98
  4202.8 2005.09  4235.1 2006.71  4284.9 2001.41  4326.0 2003.06  4362.9 1998.76
  4387.6 1998.15  4428.7 1999.89  4448.1 1997.74  4521.1 1996.45  4644.3 1997.90
  4746.9 1995.35  4859.9 1996.95  4911.2 1989.89  4942.3 1990.36  4972.6 1988.31
  4973.1 1987.81  4986.9 1988.31  5025.5 1989.40  5090.1 1999.22  5253.6 2009.20
#Mann=3,-1,0
  3763.9    0.07       0  4972.6    0.07       0  4986.9    0.07       0
Bank Sta=4972.6,4986.9
Exp/Cntr=0.3,0.1

Type RM Length L Ch R = 1,9077,661,661,661
BEGIN DESCRIPTION:
Plum Creek Trib4 6.0
END DESCRIPTION:
XS GIS Cut Line= 3
      1392827.43      6910757.86      1393905.00      6910588.00
      1394341.71      6910540.15
#Sta/Elev= 30
  3912.9 2008.13  3950.9 2009.70  3991.4 2005.35  4042.0 2006.24  4069.9 2002.29
  4123.0 2003.27  4137.5 2002.69  4153.4 1999.33  4183.8 1998.86  4205.0 2000.08
  4244.5 1996.37  4315.4 1998.06  4406.5 1994.10  4497.6 1996.94  4578.6 1994.39
  4647.5 1996.34  4679.8 1994.20  4715.0 1996.96  4807.7 1993.95  4912.7 1989.74
  5002.4 1987.98  5016.7 1986.87  5017.2 1986.37  5031.0 1986.87  5034.0 1989.31
  5044.0 1992.22  5064.1 2002.35  5084.3 2004.78  5231.7 2010.50  5443.1 2014.76
#Mann=5,-1,0
  3912.9    0.07       0  4807.7   0.035       0  5002.4    0.07       0
  5016.7   0.035       0  5031.0    0.07       0
Bank Sta=5016.7,5031
Exp/Cntr=0.3,0.1