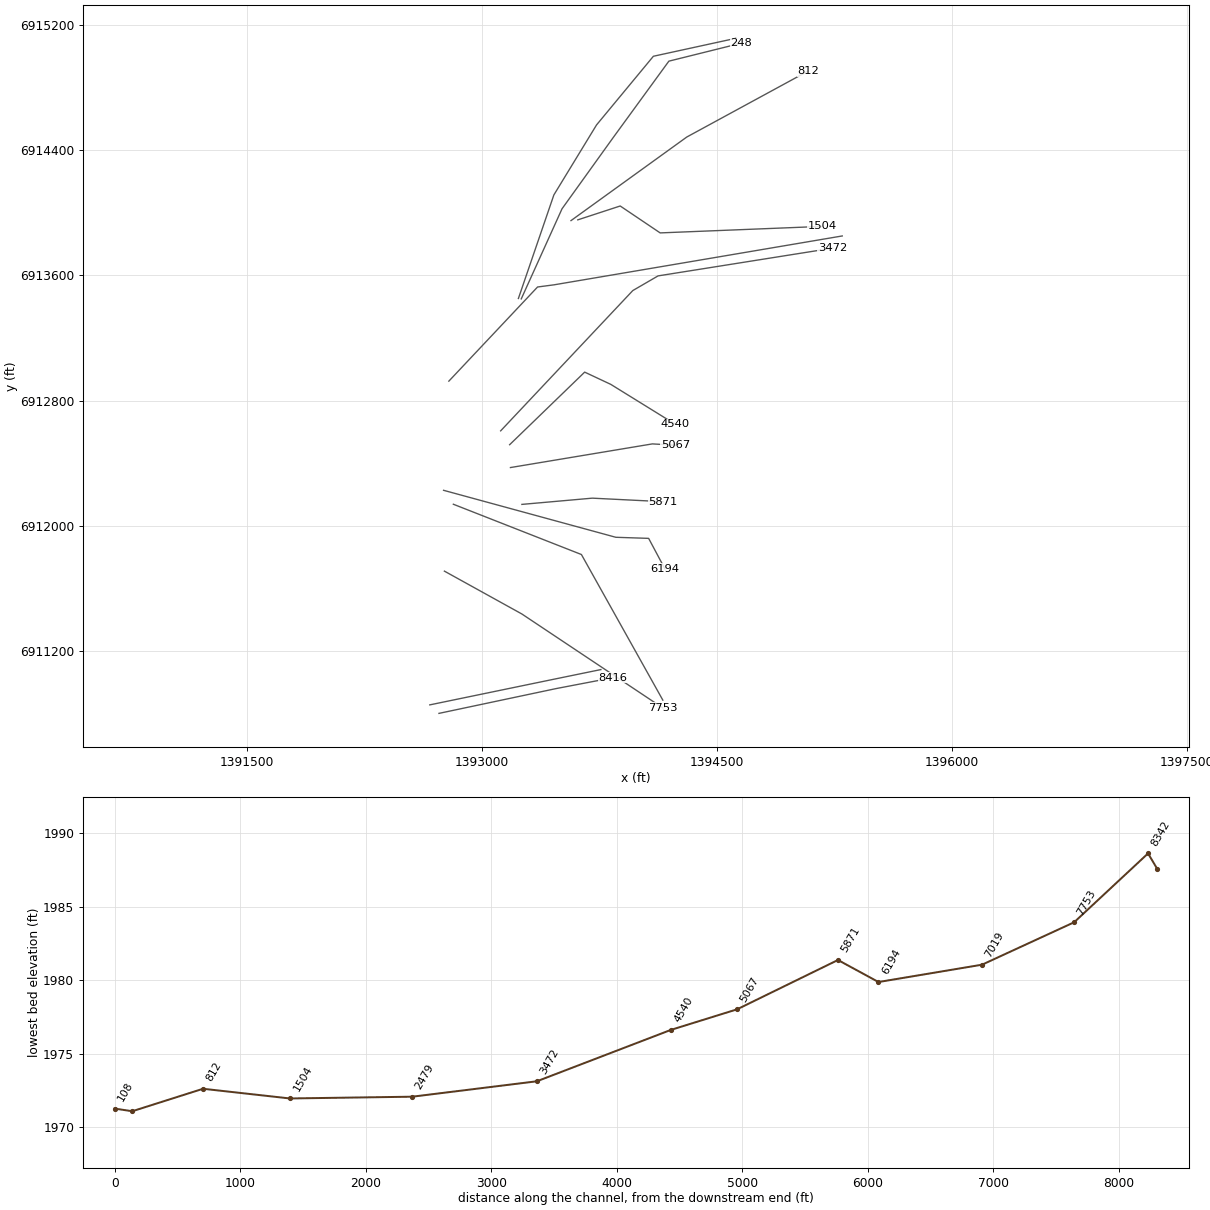
HEC-RAS study Plum Creek Trib4.prj: Plum Creek Trib4 Base Level Engineering

--- Plum Creek Trib4.g01 (geometry) --- (continued)

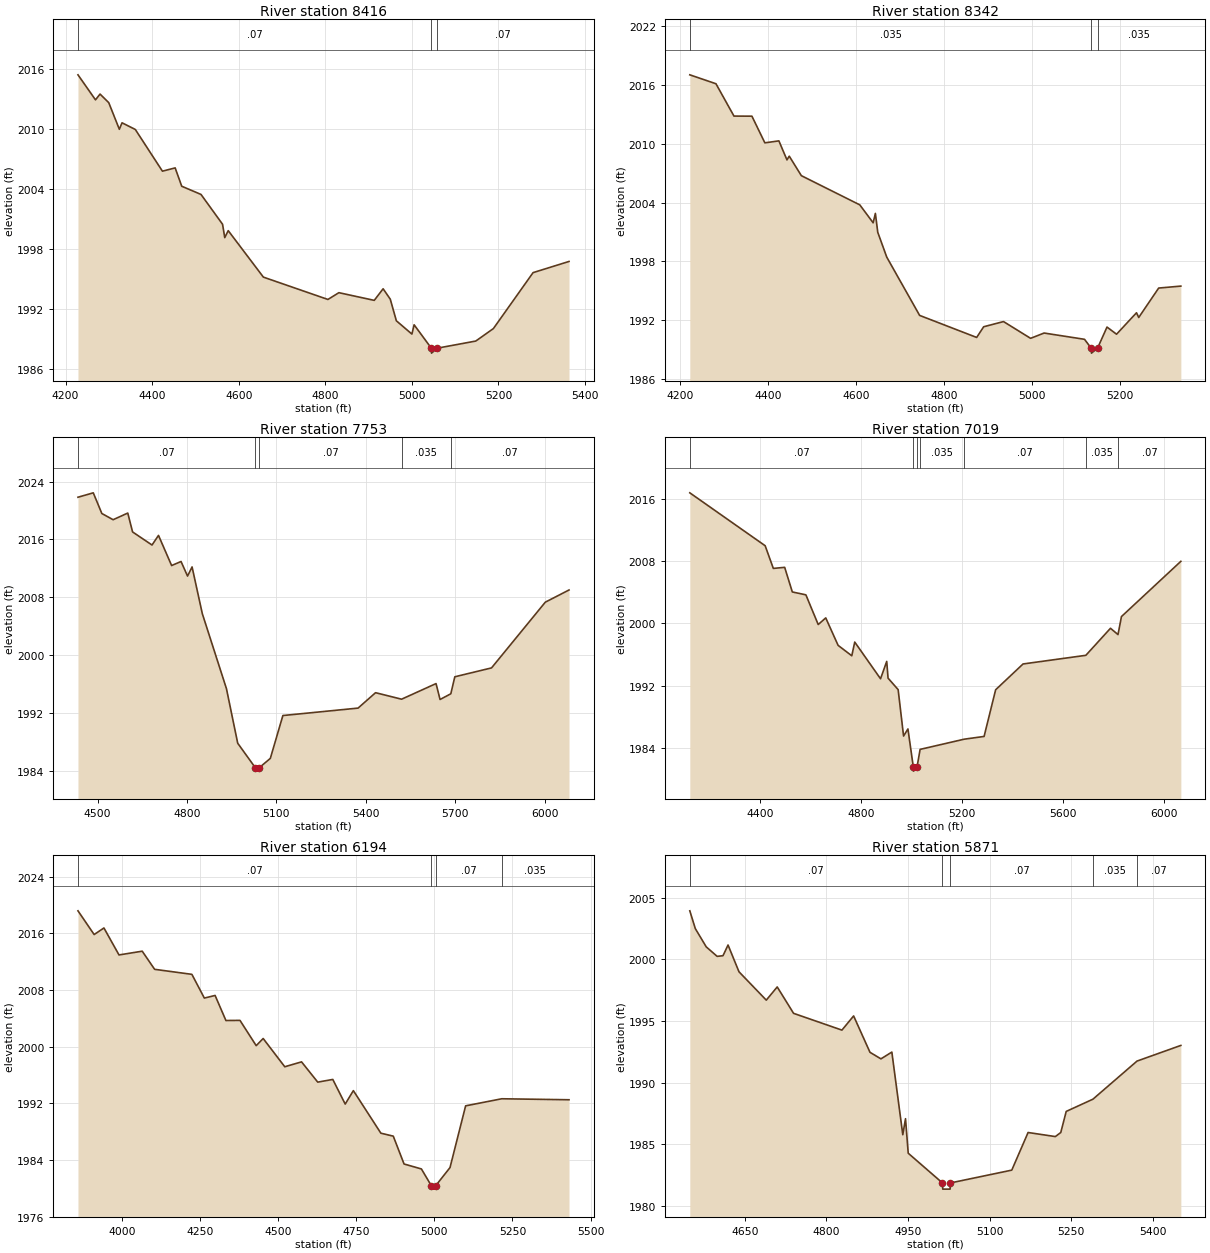
Type RM Length L Ch R = 1,8416,74,74,74
BEGIN DESCRIPTION:
Mapping XS 0ee2a9b8
END DESCRIPTION:
XS GIS Cut Line= 3
      1392725.40      6910803.42      1393474.14      6910961.85
      1393836.53      6911031.29
#Sta/Elev= 30
  4228.7 2015.46  4269.2 2012.95  4279.7 2013.53  4299.8 2012.67  4324.3 2010.00
  4330.5 2010.65  4361.2 2009.98  4423.8 2005.80  4453.2 2006.13  4468.4 2004.29
  4512.9 2003.47  4562.7 2000.48  4567.8 1999.14  4575.8 1999.84  4657.0 1995.18
  4806.1 1992.94  4831.4 1993.62  4913.1 1992.85  4933.6 1994.01  4950.1 1992.97
  4964.2 1990.80  5000.1 1989.47  5005.2 1990.40  5044.9 1988.06  5045.4 1987.56
  5059.2 1988.06  5147.6 1988.77  5188.3 1990.02  5280.0 1995.63  5363.0 1996.75
#Mann=3,-1,0
  4228.7    0.07       0  5044.9    0.07       0  5059.2    0.07       0
Bank Sta=5044.9,5059.2
Exp/Cntr=0.3,0.1

Type RM Length L Ch R = 1,8342,589,589,589
BEGIN DESCRIPTION:
Mapping XS a00cad1f
END DESCRIPTION:
XS GIS Cut Line= 3
      1392666.82      6910857.68      1393432.91      6911016.10
      1393759.40      6911083.13
#Sta/Elev= 30
  4222.8 2017.03  4282.2 2016.12  4323.1 2012.82  4363.9 2012.81  4393.3 2010.09
  4425.2 2010.29  4443.5 2008.35  4448.7 2008.73  4476.2 2006.74  4609.0 2003.76
  4639.3 2001.93  4644.4 2002.89  4649.8 2000.96  4670.3 1998.42  4744.9 1992.48
  4874.5 1990.23  4890.4 1991.32  4935.5 1991.85  4997.0 1990.14  5027.7 1990.68
  5119.5 1990.04  5134.8 1989.13  5135.3 1988.63  5149.1 1989.13  5170.6 1991.29
  5192.3 1990.56  5237.6 1992.75  5242.7 1992.27  5288.0 1995.27  5338.4 1995.47
#Mann=3,-1,0
  4222.8   0.035       0  5134.8   0.035       0  5149.1   0.035       0
Bank Sta=5134.8,5149.1
Exp/Cntr=0.3,0.1

Type RM Length L Ch R = 1,7753,734,734,734
BEGIN DESCRIPTION:
Plum Creek Trib4 5.0
END DESCRIPTION:
XS GIS Cut Line= 3
      1392760.03      6911711.84      1393255.00      6911438.00
      1394154.97      6910838.02
#Sta/Elev= 30
  4434.4 2021.83  4485.8 2022.44  4514.5 2019.58  4552.3 2018.72  4601.5 2019.64
  4617.6 2017.03  4682.8 2015.22  4704.6 2016.55  4748.6 2012.38  4780.2 2012.94
  4802.0 2010.92  4817.2 2012.19  4851.5 2005.73  4932.5 1995.35  4970.3 1987.80
  5028.9 1984.44  5029.4 1983.94  5043.3 1984.44  5079.7 1985.70  5121.8 1991.63
  5374.1 1992.66  5432.7 1994.79  5520.0 1993.89  5635.6 1996.05  5649.1 1993.85
  5685.2 1994.64  5698.6 1996.99  5821.8 1998.22  6002.1 2007.31  6081.7 2009.00
#Mann=5,-1,0
  4434.4    0.07       0  5028.9    0.07       0  5043.3    0.07       0
  5520.0   0.035       0  5685.2    0.07       0
Bank Sta=5028.9,5043.3
Exp/Cntr=0.3,0.1

Type RM Length L Ch R = 1,7019,825,825,825
BEGIN DESCRIPTION:
Plum Creek Trib4 4.0
END DESCRIPTION:
XS GIS Cut Line= 3
      1392817.29      6912138.94      1393635.04      6911817.94
      1394154.99      6910888.02
#Sta/Elev= 30
  4121.5 2016.76  4419.8 2009.97  4452.1 2007.06  4497.0 2007.20  4527.3 2004.04
  4581.0 2003.67  4629.8 1999.86  4659.6 2000.71  4708.5 1997.19  4762.7 1995.85
  4774.4 1997.61  4876.5 1992.90  4901.0 1995.13  4906.3 1992.98  4946.2 1991.51
  4967.7 1985.55  4985.0 1986.46  5006.4 1981.55  5006.9 1981.05  5020.8 1981.55
  5033.2 1983.84  5208.0 1985.15  5286.4 1985.50  5332.2 1991.49  5440.7 1994.80
  5689.3 1995.91  5786.8 1999.38  5816.6 1998.57  5830.2 2000.88  6065.4 2007.97
#Mann=7,-1,0
  4121.5    0.07       0  5006.4    0.07       0  5020.8    0.07       0
  5033.2   0.035       0  5208.0    0.07       0  5689.3   0.035       0
  5816.6    0.07       0
Bank Sta=5006.4,5020.8
Exp/Cntr=0.3,0.1

Type RM Length L Ch R = 1,6194,323,323,323
BEGIN DESCRIPTION:
Plum Creek Trib4 3.0
END DESCRIPTION:
XS GIS Cut Line= 4
      1392754.83      6912227.96      1393854.85      6911927.95
      1394064.42      6911921.05      1394168.57      6911725.77
#Sta/Elev= 30
  3859.8 2019.17  3911.6 2015.82  3942.9 2016.75  3991.1 2012.94  4065.4 2013.47
  4105.1 2010.91  4224.3 2010.20  4264.2 2006.85  4298.6 2007.22  4333.2 2003.68
  4378.2 2003.70  4430.1 2000.13  4452.4 2001.14  4521.5 1997.15  4575.2 1997.84
  4627.0 1994.98  4675.2 1995.36  4714.9 1991.88  4741.0 1993.78  4829.0 1987.77
  4868.7 1987.35  4903.2 1983.42  4958.7 1982.72  4990.2 1980.37  4990.7 1979.87
  5004.7 1980.37  5050.2 1982.91  5100.2 1991.63  5215.9 1992.63  5431.0 1992.49
#Mann=4,-1,0
  3859.8    0.07       0  4990.2    0.07       0  5004.7    0.07       0
  5215.9   0.035       0
Bank Sta=4990.2,5004.7
Exp/Cntr=0.3,0.1

Type RM Length L Ch R = 1,5871,804,804,804
BEGIN DESCRIPTION:
Plum Creek Trib4 2.0
END DESCRIPTION:
XS GIS Cut Line= 3
      1393254.95      6912138.00      1393704.49      6912177.83
      1394155.53      6912155.43
#Sta/Elev= 30
  4548.7 2003.93  4558.8 2002.49  4578.9 2001.01  4598.9 2000.24  4609.7 2000.29
  4619.0 2001.16  4639.1 1998.99  4689.3 1996.69  4709.4 1997.76  4739.5 1995.62
  4828.4 1994.26  4849.9 1995.41  4880.0 1992.46  4900.1 1991.93  4920.2 1992.48
  4940.3 1985.78  4945.3 1987.08  4950.3 1984.28  5013.3 1981.87  5013.8 1981.37
  5027.3 1981.37  5027.8 1981.87  5140.7 1982.91  5170.7 1985.96  5220.8 1985.63
  5230.8 1985.96  5240.8 1987.67  5289.9 1988.66  5371.0 1991.75  5451.6 1993.02
#Mann=5,-1,0
  4548.7    0.07       0  5013.3    0.07       0  5027.8    0.07       0
  5289.9   0.035       0  5371.0    0.07       0
Bank Sta=5013.3,5027.8
Exp/Cntr=0.3,0.1

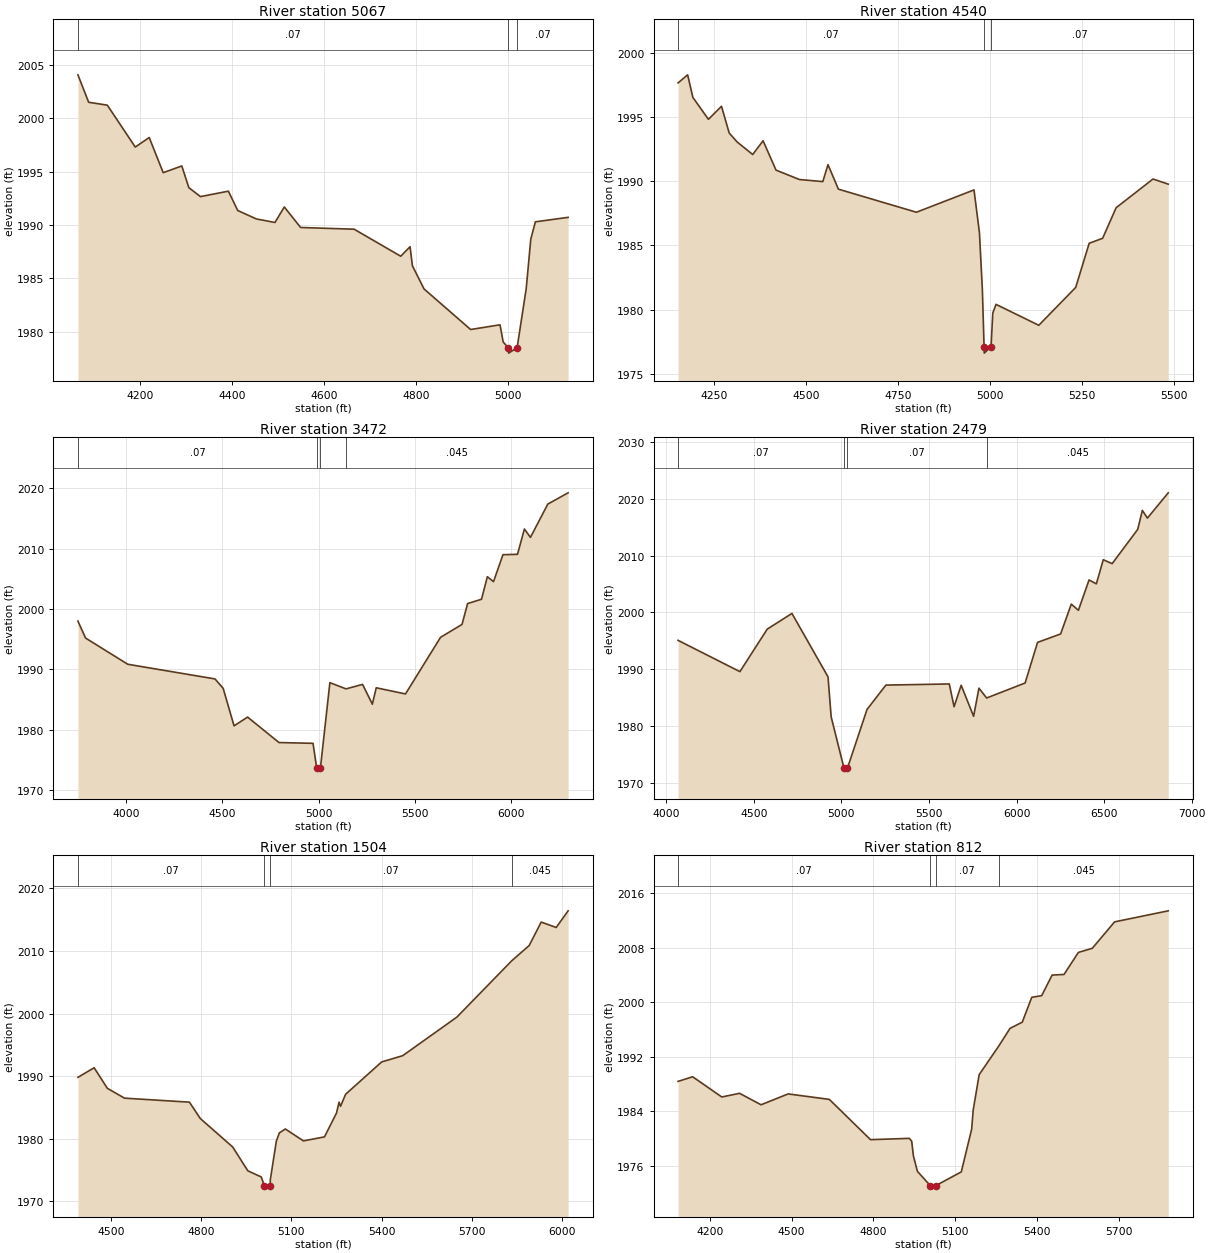
Type RM Length L Ch R = 1,5067,527,527,527
BEGIN DESCRIPTION:
Mapping XS 2e8ad08e
END DESCRIPTION:
XS GIS Cut Line= 3
      1393181.93      6912373.31      1394088.15      6912524.34
      1394236.09      6912515.83
#Sta/Elev= 30
  4064.8 2004.06  4088.2 2001.49  4128.8 2001.22  4189.6 1997.30  4220.0 1998.19
  4250.4 1994.90  4290.9 1995.53  4306.2 1993.50  4331.5 1992.66  4392.3 1993.17
  4412.6 1991.36  4453.2 1990.57  4493.7 1990.24  4514.0 1991.69  4549.5 1989.77
  4666.0 1989.61  4767.4 1987.08  4787.7 1987.97  4792.8 1986.19  4818.1 1984.02
  4919.5 1980.22  4983.5 1980.66  4990.4 1979.05  5001.7 1978.51  5002.2 1978.01
  5020.7 1978.51  5040.5 1984.04  5050.5 1988.69  5060.5 1990.30  5131.7 1990.72
#Mann=3,-1,0
  4064.8    0.07       0  5001.7    0.07       0  5020.7    0.07       0
Bank Sta=5001.7,5020.7
Exp/Cntr=0.3,0.1

Type RM Length L Ch R = 1,4540,1068,1068,1068
BEGIN DESCRIPTION:
Mapping XS 4fd30c89
END DESCRIPTION:
XS GIS Cut Line= 4
      1393176.73      6912519.17      1393655.86      6912982.68
      1393822.53      6912904.55      1394233.71      6912650.21
#Sta/Elev= 30
  4150.9 1997.67  4177.0 1998.30  4191.2 1996.54  4233.6 1994.83  4269.1 1995.85
  4290.2 1993.76  4311.6 1993.07  4354.0 1992.09  4382.3 1993.16  4417.6 1990.87
  4481.3 1990.14  4544.9 1989.98  4559.0 1991.30  4587.3 1989.39  4799.6 1987.59
  4956.4 1989.33  4971.2 1986.00  4979.2 1981.54  4983.8 1977.11  4984.3 1976.61
  5002.8 1977.11  5007.5 1979.73  5016.3 1980.41  5132.8 1978.78  5233.2 1981.73
  5269.9 1985.17  5306.5 1985.56  5343.2 1987.94  5443.6 1990.18  5485.1 1989.78
#Mann=3,-1,0
  4150.9    0.07       0  4983.8    0.07       0  5002.8    0.07       0
Bank Sta=4983.8,5002.8
Exp/Cntr=0.3,0.1

Type RM Length L Ch R = 1,3472,993,993,993
BEGIN DESCRIPTION:
Mapping XS 41d5c252
END DESCRIPTION:
XS GIS Cut Line= 4
      1393119.38      6912607.66      1393963.15      6913503.51
      1394124.61      6913597.26      1395239.18      6913774.34
#Sta/Elev= 30
  3749.8 1997.99  3789.5 1995.18  4008.8 1990.83  4461.6 1988.40  4504.0 1986.85
  4560.7 1980.62  4631.1 1982.07  4794.1 1977.85  4970.9 1977.72  4990.0 1973.61
  4990.5 1973.11  5009.2 1973.61  5058.4 1987.78  5142.3 1986.75  5228.3 1987.49
  5278.9 1984.21  5299.2 1986.93  5451.1 1985.91  5633.3 1995.30  5744.7 1997.44
  5773.7 2000.90  5846.0 2001.61  5876.3 2005.35  5908.3 2004.53  5957.3 2009.00
  6032.8 2009.06  6068.7 2013.26  6100.1 2011.87  6190.2 2017.39  6295.7 2019.26
#Mann=4,-1,0
  3749.8    0.07       0  4990.0    0.07       0  5009.2    0.07       0
  5142.3   0.045       0
Bank Sta=4990,5009.2
Exp/Cntr=0.3,0.1

Type RM Length L Ch R = 1,2479,975,975,975
BEGIN DESCRIPTION:
Plum Creek Trib4 1.0
END DESCRIPTION:
XS GIS Cut Line= 4
      1392788.54      6912925.14      1393354.97      6913526.30
      1393460.77      6913540.32      1395300.80      6913852.32
#Sta/Elev= 30
  4067.3 1995.09  4420.5 1989.58  4576.3 1997.06  4717.5 1999.83  4923.6 1988.66
  4941.5 1981.62  5015.0 1972.56  5015.5 1972.06  5034.2 1972.56  5146.3 1982.92
  5254.0 1987.21  5616.1 1987.41  5643.3 1983.40  5683.9 1987.18  5754.9 1981.71
  5785.3 1986.67  5829.2 1984.94  6049.0 1987.58  6120.0 1994.73  6251.8 1996.22
  6312.7 2001.47  6353.3 2000.38  6414.1 2005.73  6455.7 2005.04  6495.3 2009.29
  6546.0 2008.60  6692.0 2014.63  6718.4 2017.97  6747.3 2016.62  6866.3 2021.07
#Mann=4,-1,0
  4067.3    0.07       0  5015.0    0.07       0  5034.2    0.07       0
  5829.2   0.045       0
Bank Sta=5015,5034.2
Exp/Cntr=0.3,0.1

Type RM Length L Ch R = 1,1504,692,692,692
BEGIN DESCRIPTION:
Mapping XS 1cce076a
END DESCRIPTION:
XS GIS Cut Line= 4
      1393611.94      6913955.13      1393882.75      6914043.66
      1394137.96      6913871.79      1395174.42      6913913.46
#Sta/Elev= 30
  4390.2 1989.81  4444.2 1991.34  4488.1 1988.05  4545.1 1986.48  4761.0 1985.84
  4797.0 1983.23  4904.9 1978.67  4955.1 1974.87  4999.9 1973.88  5010.3 1972.44
  5010.8 1971.94  5029.5 1972.44  5029.9 1973.43  5049.9 1979.60  5059.9 1980.93
  5079.9 1981.55  5140.0 1979.65  5210.0 1980.29  5250.1 1984.11  5258.5 1985.84
  5263.5 1985.18  5280.1 1987.09  5400.2 1992.27  5470.2 1993.27  5650.4 1999.44
  5832.1 2008.41  5890.6 2010.87  5930.6 2014.62  5980.6 2013.76  6020.1 2016.42
#Mann=4,-1,0
  4390.2    0.07       0  5010.3    0.07       0  5029.5    0.07       0
  5832.1   0.045       0
Bank Sta=5010.3,5029.5
Exp/Cntr=0.3,0.1

Type RM Length L Ch R = 1,812,564,564,564
BEGIN DESCRIPTION:
Mapping XS 3f11670b
END DESCRIPTION:
XS GIS Cut Line= 3
      1393568.57      6913950.32      1394308.16      6914484.18
      1395084.16      6914906.04
#Sta/Elev= 30
  4084.4 1988.41  4137.9 1989.09  4244.6 1986.12  4309.6 1986.66  4388.3 1984.98
  4487.6 1986.57  4638.4 1985.77  4789.3 1979.86  4931.7 1980.05  4940.2 1979.62
  4946.4 1977.47  4961.1 1975.21  5008.6 1973.10  5009.1 1972.60  5027.9 1973.10
  5121.8 1975.13  5159.8 1981.41  5165.5 1984.23  5187.3 1989.40  5258.9 1993.59
  5300.3 1996.19  5345.1 1997.10  5379.9 2000.75  5416.3 2000.99  5454.3 2004.01
  5498.0 2004.10  5550.7 2007.34  5601.6 2007.94  5683.3 2011.82  5879.8 2013.44
#Mann=4,-1,0
  4084.4    0.07       0  5008.6    0.07       0  5027.9    0.07       0
  5258.9   0.045       0
Bank Sta=5008.6,5027.9
Exp/Cntr=0.3,0.1

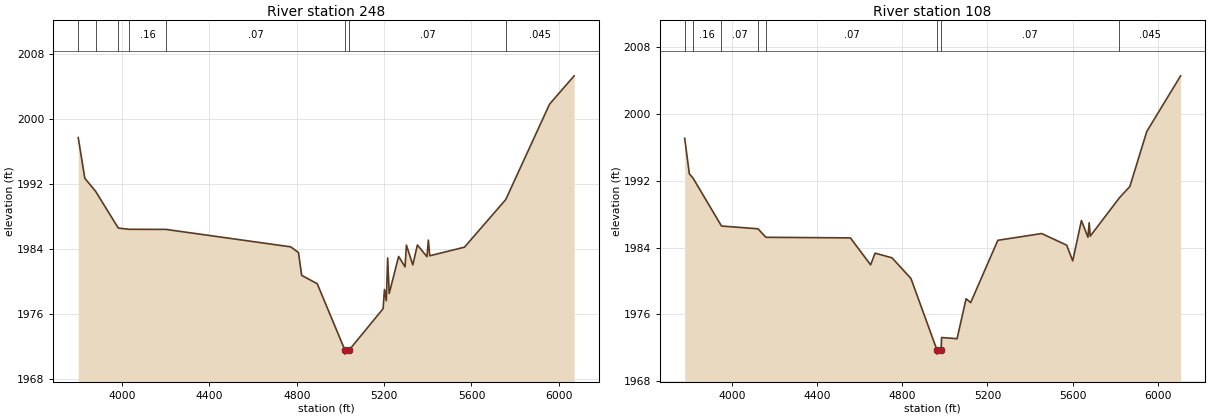
Type RM Length L Ch R = 1,248,140,140,140
BEGIN DESCRIPTION:
Mapping XS acf6fdd1
END DESCRIPTION:
XS GIS Cut Line= 5
      1393250.88      6913450.36      1393511.29      6914025.85
      1393836.81      6914478.98      1394193.58      6914968.56
      1394654.28      6915083.08
#Sta/Elev= 30
  3799.9 1997.74  3830.2 1992.72  3879.3 1991.13  3983.4 1986.59  4034.2 1986.44
  4201.0 1986.43  4772.5 1984.28  4808.1 1983.58  4822.8 1980.77  4894.0 1979.74
  5020.6 1971.57  5021.1 1971.07  5039.9 1971.57  5195.6 1976.67  5201.7 1979.03
  5210.2 1977.65  5216.4 1982.92  5223.4 1978.54  5266.6 1983.10  5296.0 1981.81
  5302.2 1984.49  5331.5 1982.06  5352.4 1984.51  5396.4 1983.07  5402.6 1985.11
  5409.0 1983.18  5567.9 1984.24  5757.1 1990.11  5957.4 2001.85  6070.0 2005.34
#Mann=8,-1,0
  3799.9    0.07       0  3879.3    0.16       0  3983.4    0.07       0
  4034.2    0.16       0  4201.0    0.07       0  5020.6    0.07       0
  5039.9    0.07       0  5757.1   0.045       0
Bank Sta=5020.6,5039.9
Exp/Cntr=0.3,0.1

Type RM Length L Ch R = 1,108,0,0,0
BEGIN DESCRIPTION:
Mapping XS 44d250ab
END DESCRIPTION:
XS GIS Cut Line= 5
      1393232.66      6913452.98      1393459.20      6914114.39
      1393731.64      6914561.26      1394094.62      6914999.81
      1394620.31      6915114.32
#Sta/Elev= 30
  3777.5 1997.12  3799.4 1992.86  3816.6 1992.35  3950.4 1986.60  4121.7 1986.27
  4159.3 1985.25  4556.0 1985.18  4650.9 1981.95  4672.2 1983.35  4751.6 1982.79
  4840.6 1980.31  4962.6 1971.75  4963.1 1971.25  4981.9 1971.75  4984.5 1973.24
  5057.2 1973.10  5099.6 1977.89  5121.0 1977.42  5248.6 1984.89  5454.4 1985.70
  5572.0 1984.31  5600.4 1982.43  5641.3 1987.26  5672.0 1985.25  5677.7 1987.00
  5682.8 1985.39  5819.3 1989.97  5868.9 1991.34  5948.3 1997.93  6107.3 2004.60
#Mann=8,-1,0
  3777.5    0.07       0  3816.6    0.16       0  3950.4    0.07       0
  4121.7    0.16       0  4159.3    0.07       0  4962.6    0.07       0
  4981.9    0.07       0  5819.3   0.045       0
Bank Sta=4962.6,4981.9
Exp/Cntr=0.3,0.1

Chan Stop Cuts=-1