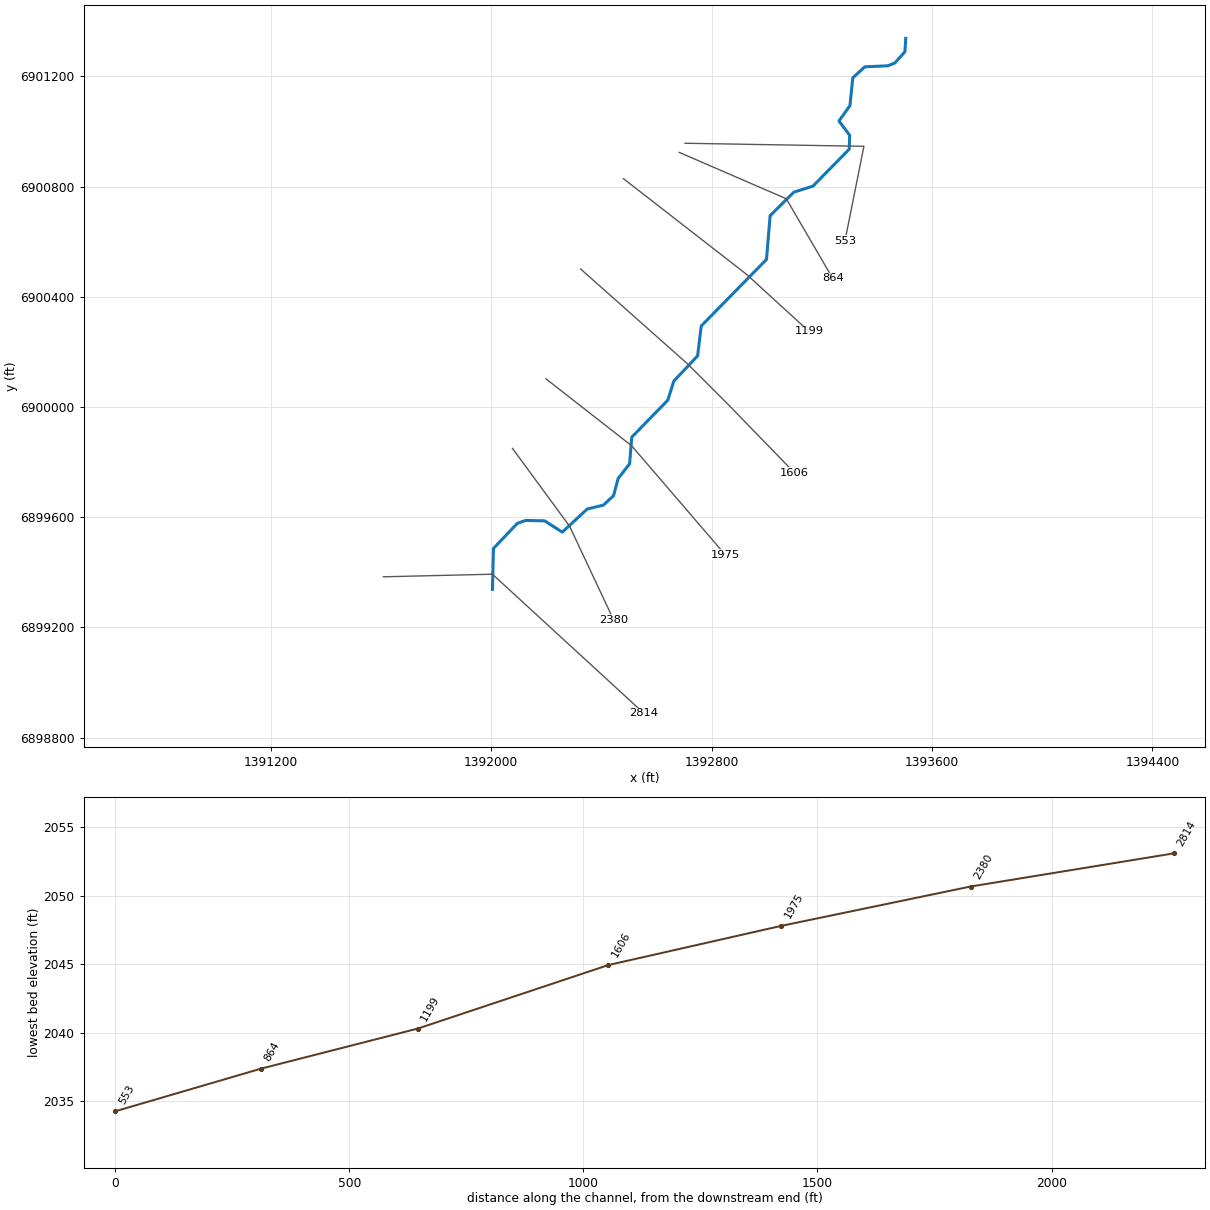
--- Plum Creek Trib4_1.prj (project) ---

Proj Title=Plum Creek Trib4_1 Base Level Engineering
Current Plan=p01
Default Exp/Contr=0.3,0.1
English Units
Geom File=g01
Flow File=f01
Plan File=p01
BEGIN DESCRIPTION:
Plum Creek Trib4_1
END DESCRIPTION:

--- Plum Creek Trib4_1.p01 (plan) ---

Plan Title=Multiple Run
Short Identifier=Multiple
Geom File=g01
Flow File=f01
Subcritical Flow
K Sum by GR= 0
Std Step Tol= 0.01
Critical Tol= 0.01
Num of Std Step Trials= 20
Max Error Tol= 0.3
Flow Tol Ratio= 0.001
Split Flow NTrial= 30
Split Flow Tol= 0.02
Split Flow Ratio= 0.02
Log Output Level= 0
Friction Slope Method= 1
Unsteady Friction Slope Method= 2
Unsteady Bridges Friction Slope Method= 1
Parabolic Critical Depth
Global Vel Dist=  1 , 1 , 1
Global Log Level= 0
CheckData=True
Encroach Param= -1, 0, 0, 0
BEGIN DESCRIPTION:
Multiple Run
END DESCRIPTION:

--- Plum Creek Trib4_1.f01 (steady flow) ---

Flow Title=Multiple
Number of Profiles=7
Profile Names=10-year,25-year,50-year,1pct_min,100-year,1pct_plu,500-year
River Rch & RM= Plum Creek Trib4,Reach-1,2814
     279     396     495     308     614    1226     958
River Rch & RM= Plum Creek Trib4,Reach-1,2380
     303     432     541     337     673    1342    1053
Boundary for River Rch & Prof#=Plum Creek Trib4,Reach-1,1
Up Type=0
Dn Type=3
Dn Slope=0.005
Boundary for River Rch & Prof#=Plum Creek Trib4,Reach-1,2
Up Type=0
Dn Type=3
Dn Slope=0.005
Boundary for River Rch & Prof#=Plum Creek Trib4,Reach-1,3
Up Type=0
Dn Type=3
Dn Slope=0.005
Boundary for River Rch & Prof#=Plum Creek Trib4,Reach-1,4
Up Type=0
Dn Type=3
Dn Slope=0.005
Boundary for River Rch & Prof#=Plum Creek Trib4,Reach-1,5
Up Type=0
Dn Type=3
Dn Slope=0.005
Boundary for River Rch & Prof#=Plum Creek Trib4,Reach-1,6
Up Type=0
Dn Type=3
Dn Slope=0.005
Boundary for River Rch & Prof#=Plum Creek Trib4,Reach-1,7
Up Type=0
Dn Type=3
Dn Slope=0.005

--- Plum Creek Trib4_1.g01 (geometry) ---

Geom Title=Existing Conditions

River Reach=Plum Creek Trib4,Reach-1
Reach XY= 30
      1392005.00      6899338.00      1392008.49      6899486.56
      1392095.19      6899577.57      1392125.05      6899588.20
      1392194.52      6899586.73      1392258.41      6899545.81
      1392348.97      6899629.80      1392407.54      6899643.75
      1392444.37      6899678.00      1392461.15      6899740.15
      1392502.67      6899793.97      1392510.52      6899890.43
      1392641.37      6900024.79      1392663.18      6900094.04
      1392749.46      6900185.58      1392762.86      6900294.17
      1392999.53      6900535.55      1393012.81      6900694.21
      1393098.93      6900779.85      1393168.21      6900801.63
      1393299.89      6900935.71      1393301.43      6900986.35
      1393262.59      6901037.99      1393302.44      6901093.90
      1393312.72      6901194.50      1393356.25      6901234.49
      1393439.88      6901238.47      1393465.09      6901248.27
      1393501.88      6901288.99      1393505.00      6901338.00

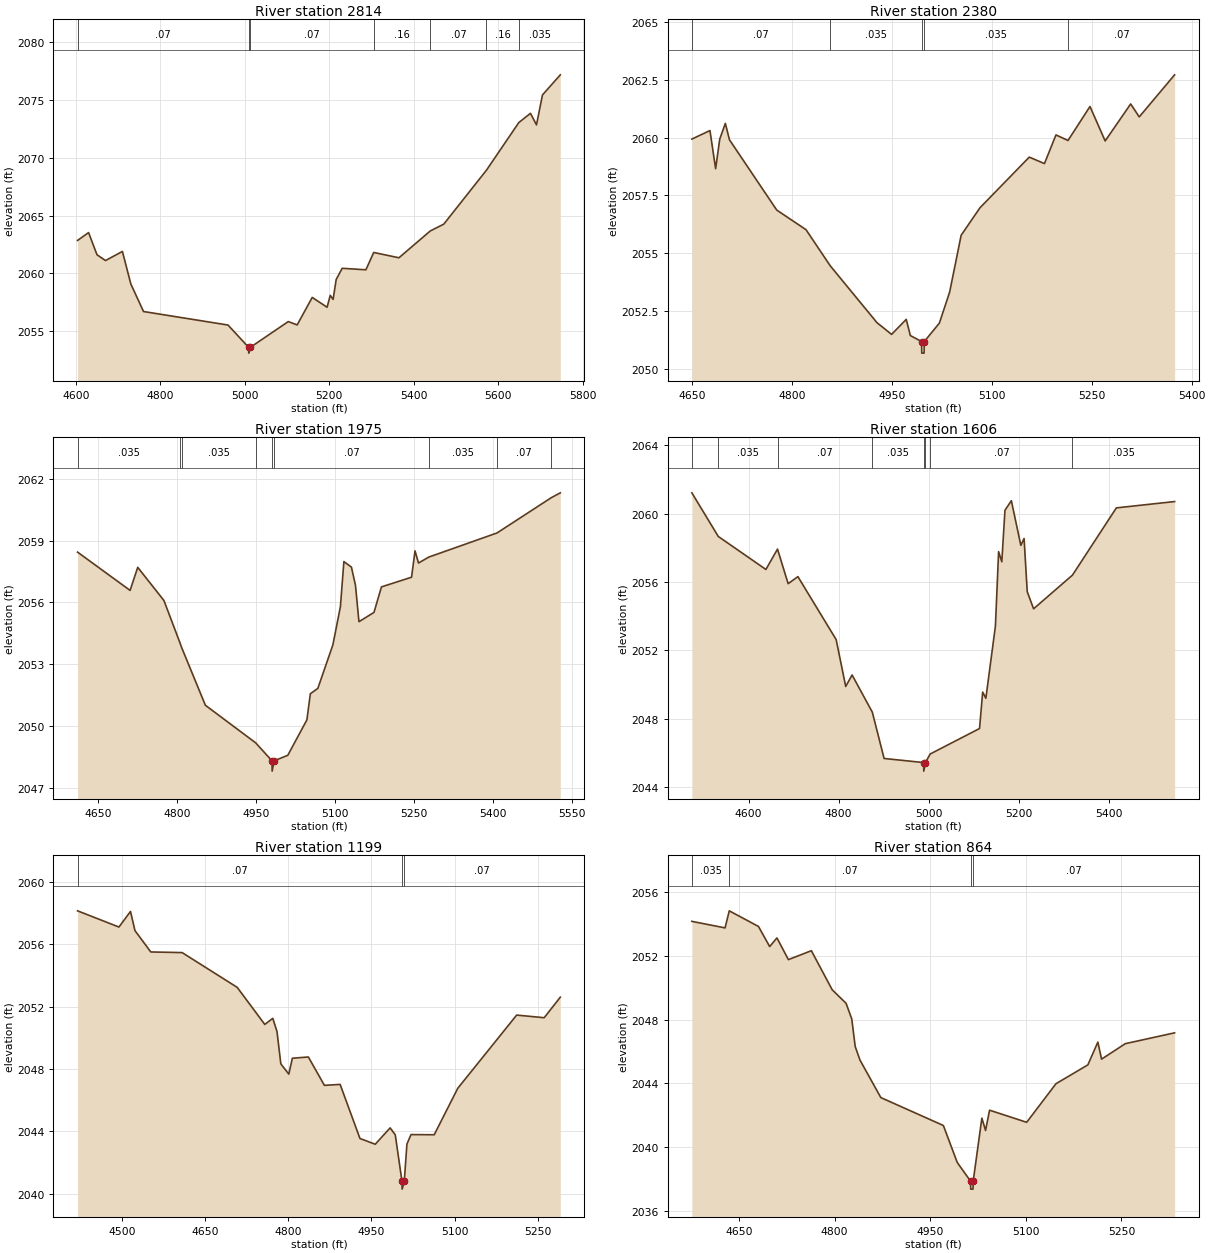
Type RM Length L Ch R = 1,2814,434,434,434
BEGIN DESCRIPTION:
Plum Creek Trib4_1 5.0
END DESCRIPTION:
XS GIS Cut Line= 3
      1391608.87      6899383.70      1392004.86      6899393.06
      1392554.98      6898888.01
#Sta/Elev= 30
  4603.9 2062.85  4630.0 2063.53  4650.0 2061.61  4670.1 2061.11  4710.1 2061.90
  4730.1 2059.08  4760.1 2056.70  4960.1 2055.53  5008.9 2053.60  5009.2 2053.10
  5012.9 2053.60  5102.8 2055.83  5123.8 2055.54  5159.5 2057.92  5194.7 2057.07
  5202.1 2058.10  5208.9 2057.75  5216.2 2059.47  5230.4 2060.44  5286.5 2060.31
  5305.1 2061.81  5364.8 2061.35  5438.9 2063.67  5470.9 2064.26  5572.0 2068.93
  5648.6 2073.05  5676.2 2073.85  5690.4 2072.85  5704.6 2075.44  5746.8 2077.18
#Mann=7,-1,0
  4603.9    0.07       0  5008.9    0.07       0  5012.9    0.07       0
  5305.1    0.16       0  5438.9    0.07       0  5572.0    0.16       0
  5648.6   0.035       0
Bank Sta=5008.9,5012.9
Exp/Cntr=0.3,0.1

Type RM Length L Ch R = 1,2380,405,405,405
BEGIN DESCRIPTION:
Plum Creek Trib4_1 4.0
END DESCRIPTION:
XS GIS Cut Line= 3
      1392077.52      6899849.88      1392284.99      6899567.13
      1392444.17      6899228.26
#Sta/Elev= 30
  4649.3 2059.94  4676.5 2060.31  4685.0 2058.66  4691.2 2059.94  4699.6 2060.62
  4705.8 2059.91  4776.8 2056.87  4820.8 2056.02  4857.1 2054.46  4927.3 2052.00
  4949.3 2051.49  4971.3 2052.14  4977.5 2051.44  4994.4 2051.18  4994.6 2050.68
  4998.1 2050.68  4998.4 2051.18  5021.1 2051.98  5036.5 2053.32  5053.8 2055.78
  5082.1 2056.97  5156.1 2059.16  5178.9 2058.88  5196.2 2060.12  5214.3 2059.88
  5247.3 2061.35  5270.1 2059.86  5308.4 2061.46  5321.3 2060.90  5374.4 2062.72
#Mann=5,-1,0
  4649.3    0.07       0  4857.1   0.035       0  4994.4   0.035       0
  4998.4   0.035       0  5214.3    0.07       0
Bank Sta=4994.4,4998.4
Exp/Cntr=0.3,0.1

Type RM Length L Ch R = 1,1975,369,369,369
BEGIN DESCRIPTION:
Mapping XS 12d750e1
END DESCRIPTION:
XS GIS Cut Line= 3
      1392198.93      6900102.44      1392509.72      6899859.63
      1392849.64      6899463.86
#Sta/Elev= 30
  4611.7 2058.44  4711.4 2056.58  4725.9 2057.70  4775.6 2056.09  4806.1 2054.03
  4809.3 2053.80  4854.3 2051.00  4949.9 2049.17  4980.7 2048.30  4981.0 2047.80
  4984.7 2048.30  5010.7 2048.57  5046.9 2050.29  5053.5 2051.56  5067.7 2051.82
  5096.3 2053.94  5110.5 2055.79  5117.1 2057.98  5131.4 2057.71  5139.1 2056.83
  5145.7 2055.06  5174.2 2055.51  5188.4 2056.75  5245.5 2057.22  5252.1 2058.50
  5258.7 2057.91  5278.4 2058.20  5407.7 2059.37  5510.4 2061.08  5527.8 2061.32
#Mann=9,-1,0
  4611.7   0.035       0  4806.1    0.07       0  4809.3   0.035       0
  4949.9    0.07       0  4980.7    0.07       0  4984.7    0.07       0
  5278.4   0.035       0  5407.7    0.07       0  5510.4   0.035       0
Bank Sta=4980.7,4984.7
Exp/Cntr=0.3,0.1

Type RM Length L Ch R = 1,1606,407,407,407
BEGIN DESCRIPTION:
Mapping XS 685fb642
END DESCRIPTION:
XS GIS Cut Line= 4
      1392325.20      6900500.67      1392713.69      6900155.88
      1392859.39      6900010.19      1393101.12      6899761.20
#Sta/Elev= 30
  4473.8 2061.21  4532.5 2058.66  4638.3 2056.73  4664.1 2057.92  4687.7 2055.90
  4709.4 2056.31  4794.4 2052.63  4815.6 2049.89  4829.8 2050.56  4874.7 2048.39
  4900.9 2045.68  4988.8 2045.44  4989.0 2044.94  4992.8 2045.44  5003.2 2045.94
  5112.9 2047.43  5119.9 2049.56  5127.0 2049.20  5148.2 2053.42  5155.3 2057.77
  5162.4 2057.18  5169.4 2060.19  5183.6 2060.75  5204.7 2058.14  5211.9 2058.54
  5218.9 2055.43  5233.0 2054.43  5319.4 2056.40  5416.9 2060.33  5546.3 2060.70
#Mann=8,-1,0
  4473.8    0.07       0  4532.5   0.035       0  4664.1    0.07       0
  4874.7   0.035       0  4988.8   0.035       0  4992.8   0.035       0
  5003.2    0.07       0  5319.4   0.035       0
Bank Sta=4988.8,4992.8
Exp/Cntr=0.3,0.1

Type RM Length L Ch R = 1,1199,335,335,335
BEGIN DESCRIPTION:
Mapping XS d8f20124
END DESCRIPTION:
XS GIS Cut Line= 3
      1392480.55      6900828.53      1392927.38      6900481.27
      1393153.18      6900274.89
#Sta/Elev= 30
  4419.2 2058.16  4493.9 2057.12  4514.8 2058.12  4522.9 2056.89  4551.5 2055.52
  4608.0 2055.48  4707.5 2053.25  4757.3 2050.87  4771.8 2051.26  4779.4 2050.41
  4786.3 2048.34  4800.7 2047.68  4807.1 2048.70  4836.0 2048.78  4865.0 2046.96
  4893.4 2047.02  4929.2 2043.55  4956.8 2043.18  4983.7 2044.23  4993.0 2043.78
  5005.1 2040.80  5005.4 2040.30  5009.2 2040.80  5014.0 2043.19  5021.4 2043.80
  5063.3 2043.79  5105.8 2046.77  5212.2 2051.47  5261.9 2051.30  5291.0 2052.62
#Mann=3,-1,0
  4419.2    0.07       0  5005.1    0.07       0  5009.2    0.07       0
Bank Sta=5005.1,5009.2
Exp/Cntr=0.3,0.1

Type RM Length L Ch R = 1,864,311,311,311
BEGIN DESCRIPTION:
Mapping XS fa50c729
END DESCRIPTION:
XS GIS Cut Line= 3
      1392682.91      6900924.02      1393071.40      6900755.82
      1393239.59      6900467.19
#Sta/Elev= 30
  4576.1 2054.16  4628.2 2053.75  4634.8 2054.82  4680.6 2053.84  4698.2 2052.58
  4709.6 2053.12  4727.6 2051.76  4763.6 2052.32  4796.3 2049.87  4818.1 2049.02
  4827.0 2048.04  4832.4 2046.31  4839.9 2045.46  4872.6 2043.11  4970.7 2041.36
  4992.5 2039.04  5013.4 2037.87  5013.6 2037.37  5017.2 2037.37  5017.5 2037.87
  5031.1 2041.82  5036.9 2041.05  5043.2 2042.32  5101.4 2041.56  5147.4 2043.98
  5197.4 2045.16  5213.1 2046.59  5218.9 2045.52  5256.1 2046.49  5333.5 2047.17
#Mann=4,-1,0
  4576.1   0.035       0  4634.8    0.07       0  5013.4    0.07       0
  5017.5    0.07       0
Bank Sta=5013.4,5017.5
Exp/Cntr=0.3,0.1

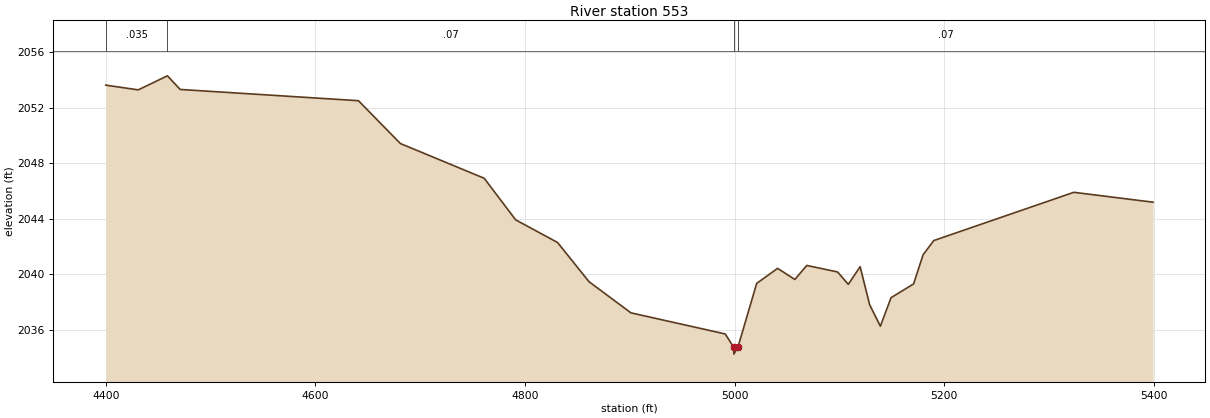
Type RM Length L Ch R = 1,553,0,0,0
BEGIN DESCRIPTION:
Plum Creek Trib4_1 1.0
END DESCRIPTION:
XS GIS Cut Line= 3
      1392703.98      6900957.21      1393353.09      6900946.14
      1393284.37      6900602.86
#Sta/Elev= 30
  4399.9 2053.61  4430.9 2053.27  4458.7 2054.28  4470.9 2053.30  4641.0 2052.49
  4681.0 2049.41  4761.0 2046.91  4791.0 2043.92  4831.0 2042.29  4861.0 2039.47
  4901.0 2037.23  4991.0 2035.71  4999.0 2034.76  4999.2 2034.26  5003.1 2034.76
  5021.0 2039.35  5041.0 2040.43  5057.4 2039.63  5068.8 2040.64  5098.2 2040.17
  5108.4 2039.28  5119.7 2040.55  5128.8 2037.81  5139.0 2036.27  5149.2 2038.32
  5170.7 2039.31  5179.8 2041.41  5190.0 2042.43  5323.6 2045.90  5399.2 2045.19
#Mann=4,-1,0
  4399.9   0.035       0  4458.7    0.07       0  4999.0    0.07       0
  5003.1    0.07       0
Bank Sta=4999,5003.1
Exp/Cntr=0.3,0.1

Chan Stop Cuts=-1