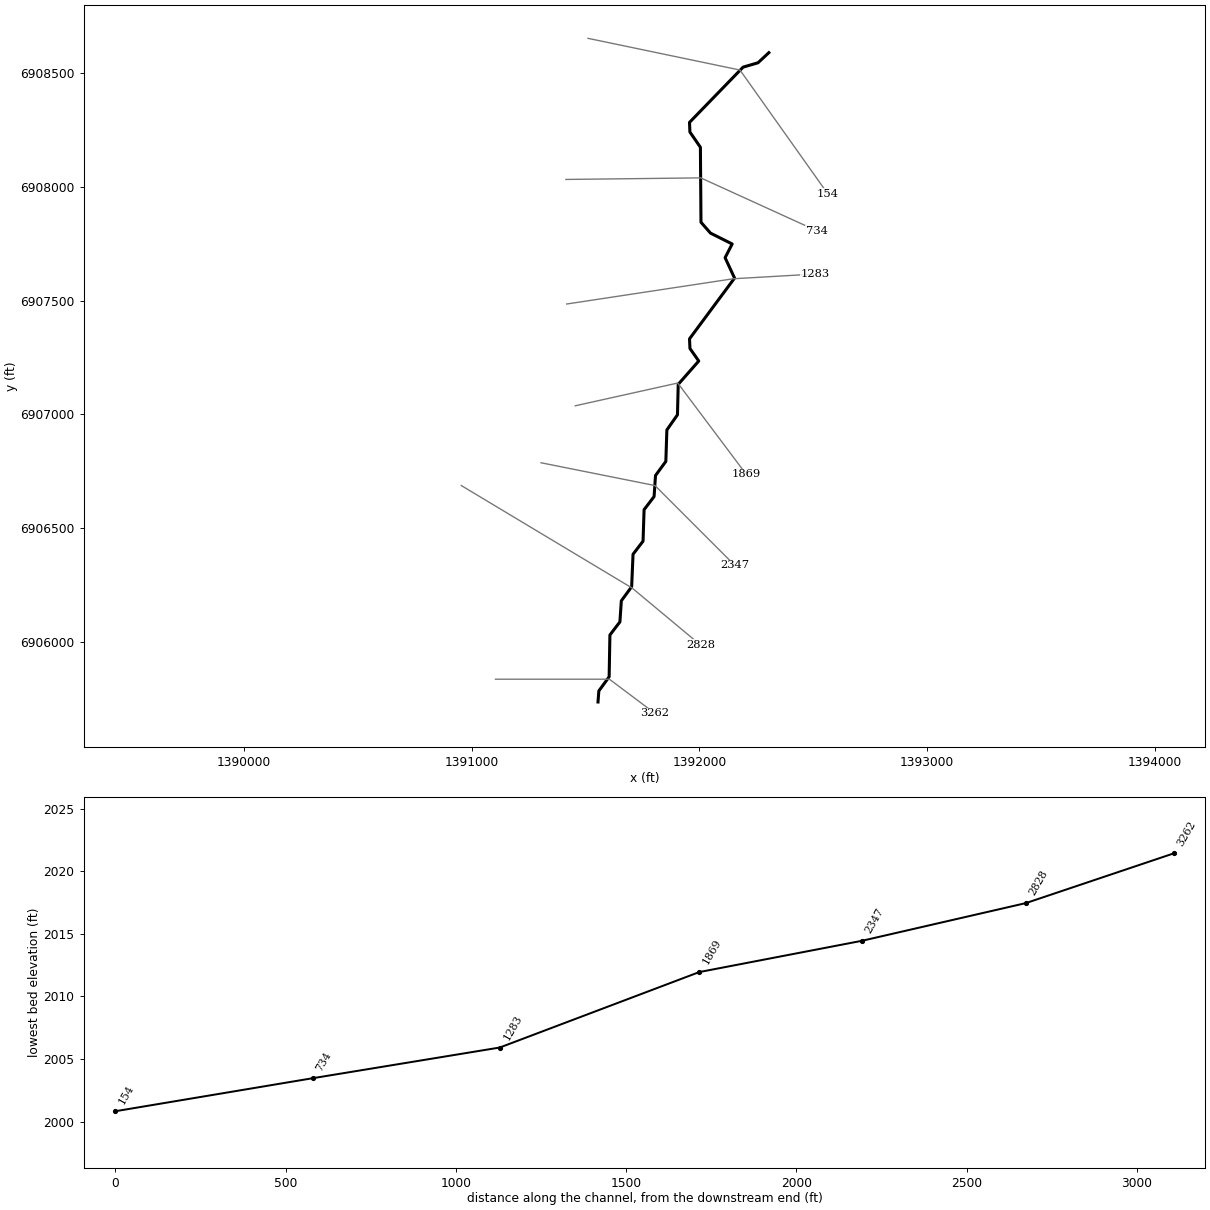
--- Plum Creek Trib4_2.prj (project) ---

Proj Title=Plum Creek Trib4_2 Base Level Engineering
Current Plan=p01
Default Exp/Contr=0.3,0.1
English Units
Geom File=g01
Flow File=f01
Plan File=p01
BEGIN DESCRIPTION:
Plum Creek Trib4_2
END DESCRIPTION:

--- Plum Creek Trib4_2.p01 (plan) ---

Plan Title=Multiple Run
Short Identifier=Multiple
Geom File=g01
Flow File=f01
Subcritical Flow
K Sum by GR= 0
Std Step Tol= 0.01
Critical Tol= 0.01
Num of Std Step Trials= 20
Max Error Tol= 0.3
Flow Tol Ratio= 0.001
Split Flow NTrial= 30
Split Flow Tol= 0.02
Split Flow Ratio= 0.02
Log Output Level= 0
Friction Slope Method= 1
Unsteady Friction Slope Method= 2
Unsteady Bridges Friction Slope Method= 1
Parabolic Critical Depth
Global Vel Dist=  1 , 1 , 1
Global Log Level= 0
CheckData=True
Encroach Param= -1, 0, 0, 0
BEGIN DESCRIPTION:
Multiple Run
END DESCRIPTION:

--- Plum Creek Trib4_2.f01 (steady flow) ---

Flow Title=Multiple
Number of Profiles=7
Profile Names=10-year,25-year,50-year,1pct_min,100-year,1pct_plu,500-year
River Rch & RM= Plum Creek Trib4,Reach-1,3262
     295     417     519     321     641    1279     991
Boundary for River Rch & Prof#=Plum Creek Trib4,Reach-1,1
Up Type=0
Dn Type=3
Dn Slope=0.005
Boundary for River Rch & Prof#=Plum Creek Trib4,Reach-1,2
Up Type=0
Dn Type=3
Dn Slope=0.005
Boundary for River Rch & Prof#=Plum Creek Trib4,Reach-1,3
Up Type=0
Dn Type=3
Dn Slope=0.005
Boundary for River Rch & Prof#=Plum Creek Trib4,Reach-1,4
Up Type=0
Dn Type=3
Dn Slope=0.005
Boundary for River Rch & Prof#=Plum Creek Trib4,Reach-1,5
Up Type=0
Dn Type=3
Dn Slope=0.005
Boundary for River Rch & Prof#=Plum Creek Trib4,Reach-1,6
Up Type=0
Dn Type=3
Dn Slope=0.005
Boundary for River Rch & Prof#=Plum Creek Trib4,Reach-1,7
Up Type=0
Dn Type=3
Dn Slope=0.005

--- Plum Creek Trib4_2.g01 (geometry) ---

Geom Title=Existing Conditions

River Reach=Plum Creek Trib4,Reach-1
Reach XY= 30
      1391555.00      6905738.00      1391558.65      6905786.49
      1391603.88      6905848.46      1391607.26      6906032.06
      1391651.14      6906089.60      1391657.36      6906182.02
      1391702.73      6906243.94      1391708.79      6906386.43
      1391752.73      6906443.94      1391757.27      6906582.06
      1391801.14      6906639.60      1391807.36      6906732.02
      1391852.73      6906793.94      1391857.27      6906932.06
      1391903.77      6906998.51      1391907.08      6907132.14
      1391997.16      6907234.60      1391958.59      6907289.65
      1391956.67      6907331.95      1392154.35      6907598.64
      1392112.84      6907688.10      1392143.89      6907748.32
      1392048.66      6907796.02      1392006.98      6907843.67
      1392004.46      6908172.79      1391958.34      6908239.75
      1391956.62      6908281.97      1392191.77      6908524.43
      1392257.35      6908543.71      1392305.00      6908588.00

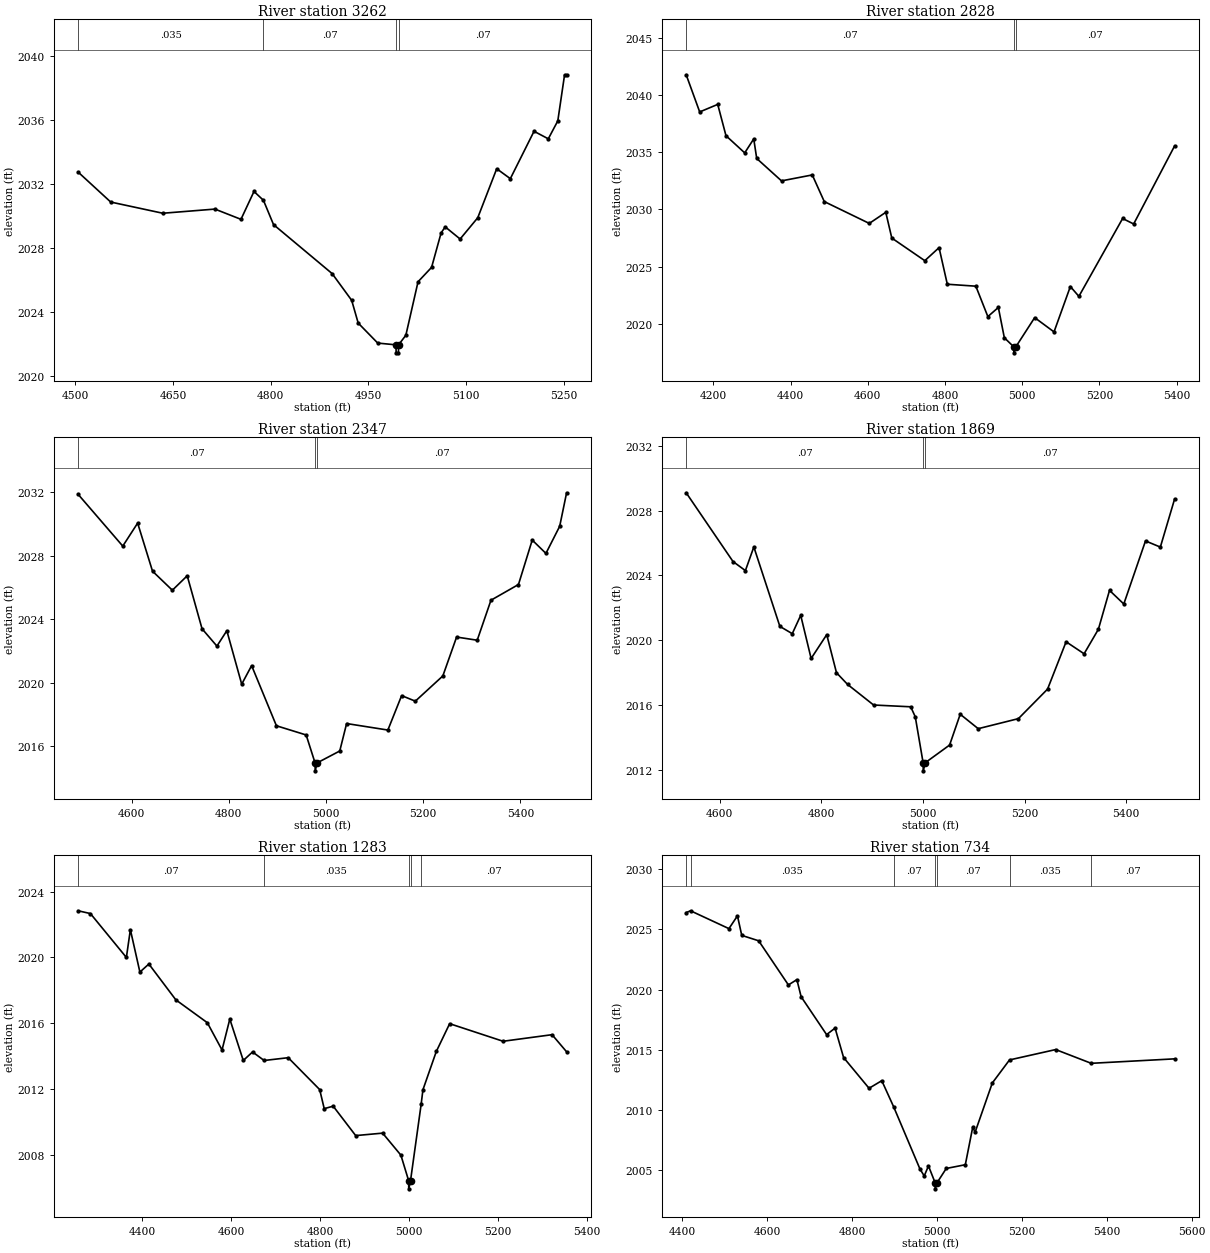
Type RM Length L Ch R = 1,3262,434,434,434
BEGIN DESCRIPTION:
Plum Creek Trib4_2 5.0
END DESCRIPTION:
XS GIS Cut Line= 3
      1391104.96      6905838.00      1391605.00      6905838.00
      1391804.97      6905688.02
#Sta/Elev= 30
  4504.3 2032.72  4554.3 2030.85  4634.3 2030.15  4714.3 2030.41  4754.3 2029.77
  4774.3 2031.51  4788.8 2030.96  4804.3 2029.44  4894.3 2026.38  4924.3 2024.71
  4934.3 2023.29  4964.3 2022.04  4992.3 2021.93  4992.6 2021.43  4996.1 2021.43
  4996.3 2021.93  5007.5 2022.53  5026.2 2025.87  5047.0 2026.77  5061.6 2028.92
  5067.9 2029.30  5090.8 2028.54  5117.9 2029.87  5147.0 2032.93  5167.9 2032.31
  5204.3 2035.27  5226.2 2034.80  5240.8 2035.92  5251.2 2038.80  5254.3 2038.80
#Mann=4,-1,0
  4504.3   0.035       0  4788.8    0.07       0  4992.3    0.07       0
  4996.3    0.07       0
Bank Sta=4992.3,4996.3
Exp/Cntr=0.3,0.1

Type RM Length L Ch R = 1,2828,481,481,481
BEGIN DESCRIPTION:
Plum Creek Trib4_2 4.0
END DESCRIPTION:
XS GIS Cut Line= 3
      1390954.97      6906688.02      1391705.00      6906238.00
      1392005.01      6905987.99
#Sta/Elev= 30
  4129.5 2041.78  4164.5 2038.53  4211.2 2039.19  4232.6 2036.45  4281.1 2034.95
  4304.5 2036.17  4312.2 2034.46  4376.4 2032.50  4456.1 2033.02  4487.2 2030.69
  4603.8 2028.78  4646.5 2029.75  4662.1 2027.50  4747.6 2025.52  4784.5 2026.66
  4805.9 2023.46  4879.8 2023.29  4910.9 2020.63  4938.1 2021.43  4953.6 2018.78
  4978.8 2017.96  4979.1 2017.46  4982.9 2017.96  5032.2 2020.54  5082.3 2019.29
  5124.6 2023.26  5146.7 2022.40  5260.0 2029.21  5288.6 2028.73  5394.7 2035.56
#Mann=3,-1,0
  4129.5    0.07       0  4978.8    0.07       0  4982.9    0.07       0
Bank Sta=4978.8,4982.9
Exp/Cntr=0.3,0.1

Type RM Length L Ch R = 1,2347,478,478,478
BEGIN DESCRIPTION:
Plum Creek Trib4_2 3.0
END DESCRIPTION:
XS GIS Cut Line= 3
      1391305.00      6906788.00      1391805.00      6906688.00
      1392155.02      6906337.98
#Sta/Elev= 30
  4490.1 2031.87  4581.9 2028.61  4612.5 2030.06  4643.1 2027.03  4683.9 2025.83
  4714.5 2026.74  4745.0 2023.40  4775.6 2022.31  4796.0 2023.28  4826.6 2019.91
  4847.0 2021.08  4898.0 2017.29  4959.2 2016.71  4977.5 2014.95  4977.8 2014.45
  4981.7 2014.95  5028.3 2015.70  5042.4 2017.43  5127.3 2017.02  5155.6 2019.19
  5183.8 2018.84  5240.4 2020.43  5268.7 2022.88  5311.1 2022.68  5339.4 2025.20
  5396.0 2026.19  5424.3 2028.99  5452.5 2028.15  5480.8 2029.86  5495.0 2031.97
#Mann=3,-1,0
  4490.1    0.07       0  4977.5    0.07       0  4981.7    0.07       0
Bank Sta=4977.5,4981.7
Exp/Cntr=0.3,0.1

Type RM Length L Ch R = 1,1869,586,586,586
BEGIN DESCRIPTION:
Plum Creek Trib4_2 2.0
END DESCRIPTION:
XS GIS Cut Line= 3
      1391455.05      6907038.01      1391905.00      6907138.00
      1392204.98      6906738.02
#Sta/Elev= 30
  4534.4 2029.10  4626.5 2024.86  4650.9 2024.30  4667.5 2025.76  4718.7 2020.86
  4743.1 2020.41  4759.7 2021.54  4780.2 2018.88  4810.9 2020.35  4830.1 2018.00
  4851.9 2017.28  4903.1 2016.01  4976.1 2015.90  4985.1 2015.28  5000.5 2012.45
  5000.8 2011.95  5004.7 2012.45  5052.6 2013.54  5073.5 2015.44  5108.9 2014.55
  5188.0 2015.17  5245.3 2016.99  5281.8 2019.91  5317.2 2019.17  5345.3 2020.68
  5367.2 2023.08  5395.3 2022.24  5438.0 2026.13  5467.2 2025.75  5495.3 2028.72
#Mann=3,-1,0
  4534.4    0.07       0  5000.5    0.07       0  5004.7    0.07       0
Bank Sta=5000.5,5004.7
Exp/Cntr=0.3,0.1

Type RM Length L Ch R = 1,1283,549,549,549
BEGIN DESCRIPTION:
Mapping XS f88d1361
END DESCRIPTION:
XS GIS Cut Line= 3
      1391417.70      6907484.81      1392147.79      6907595.53
      1392507.65      6907616.29
#Sta/Elev= 30
  4255.6 2022.84  4283.2 2022.67  4364.1 2020.00  4373.1 2021.69  4394.5 2019.11
  4414.7 2019.60  4475.4 2017.42  4546.2 2016.03  4579.3 2014.37  4596.8 2016.25
  4627.1 2013.73  4648.0 2014.25  4674.0 2013.73  4728.2 2013.90  4799.0 2011.96
  4809.2 2010.80  4829.4 2010.95  4880.0 2009.16  4940.6 2009.31  4981.7 2007.97
  4999.1 2006.42  4999.4 2005.92  5003.4 2006.42  5027.3 2011.07  5031.3 2011.95
  5061.4 2014.28  5091.4 2015.97  5211.6 2014.90  5321.8 2015.30  5354.5 2014.26
#Mann=5,-1,0
  4255.6    0.07       0  4674.0   0.035       0  4999.1   0.035       0
  5003.4   0.035       0  5027.3    0.07       0
Bank Sta=4999.1,5003.4
Exp/Cntr=0.3,0.1

Type RM Length L Ch R = 1,734,580,580,580
BEGIN DESCRIPTION:
Mapping XS 48fd8e79
END DESCRIPTION:
XS GIS Cut Line= 3
      1391414.26      6908031.53      1392005.92      6908038.45
      1392514.58      6907806.61
#Sta/Elev= 30
  4409.2 2026.38  4419.4 2026.53  4509.9 2025.05  4530.0 2026.11  4540.1 2024.49
  4580.0 2024.04  4650.0 2020.38  4670.0 2020.82  4680.0 2019.40  4740.0 2016.26
  4760.0 2016.80  4780.0 2014.36  4840.0 2011.81  4870.0 2012.44  4898.0 2010.27
  4960.0 2005.11  4970.0 2004.54  4980.0 2005.37  4995.7 2003.97  4996.0 2003.47
  5000.1 2003.97  5021.9 2005.16  5066.8 2005.47  5084.3 2008.59  5089.8 2008.16
  5130.4 2012.25  5170.9 2014.16  5279.7 2015.02  5363.4 2013.88  5559.9 2014.25
#Mann=7,-1,0
  4409.2    0.07       0  4419.4   0.035       0  4898.0    0.07       0
  4995.7    0.07       0  5000.1    0.07       0  5170.9   0.035       0
  5363.4    0.07       0
Bank Sta=4995.7,5000.1
Exp/Cntr=0.3,0.1

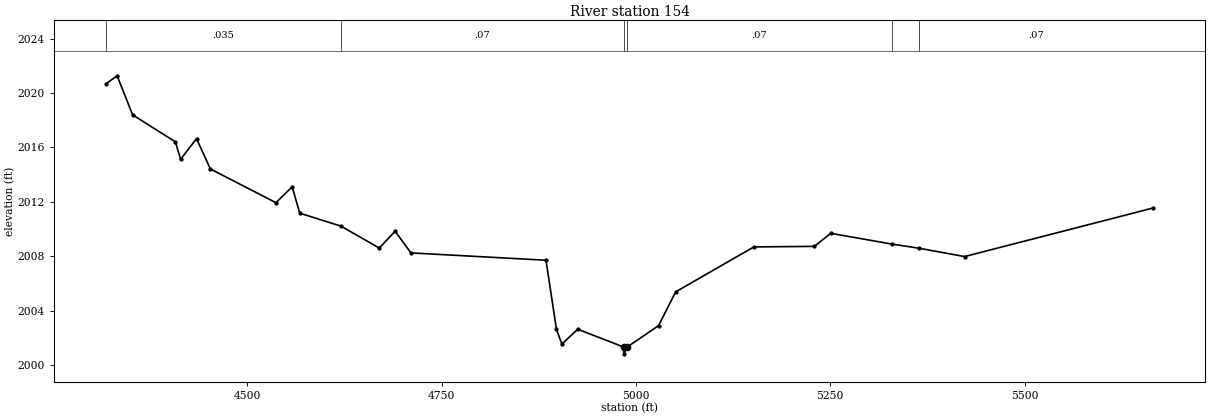
Type RM Length L Ch R = 1,154,0,0,0
BEGIN DESCRIPTION:
Plum Creek Trib4_2 1.0
END DESCRIPTION:
XS GIS Cut Line= 3
      1391511.14      6908650.91      1392178.17      6908511.72
      1392563.01      6907969.26
#Sta/Elev= 30
  4318.6 2020.68  4332.8 2021.27  4352.7 2018.40  4407.8 2016.41  4414.5 2015.13
  4434.9 2016.65  4452.7 2014.42  4537.1 2011.94  4557.9 2013.11  4567.7 2011.17
  4620.6 2010.22  4669.9 2008.61  4690.3 2009.84  4710.7 2008.25  4884.4 2007.71
  4897.8 2002.63  4904.8 2001.55  4925.2 2002.64  4984.3 2001.33  4984.6 2000.83
  4988.7 2001.33  5029.1 2002.90  5051.2 2005.39  5151.7 2008.69  5229.6 2008.73
  5250.5 2009.69  5329.0 2008.90  5364.4 2008.59  5422.7 2007.98  5665.1 2011.55
#Mann=6,-1,0
  4318.6   0.035       0  4620.6    0.07       0  4984.3    0.07       0
  4988.7    0.07       0  5329.0   0.035       0  5364.4    0.07       0
Bank Sta=4984.3,4988.7
Exp/Cntr=0.3,0.1

Chan Stop Cuts=-1