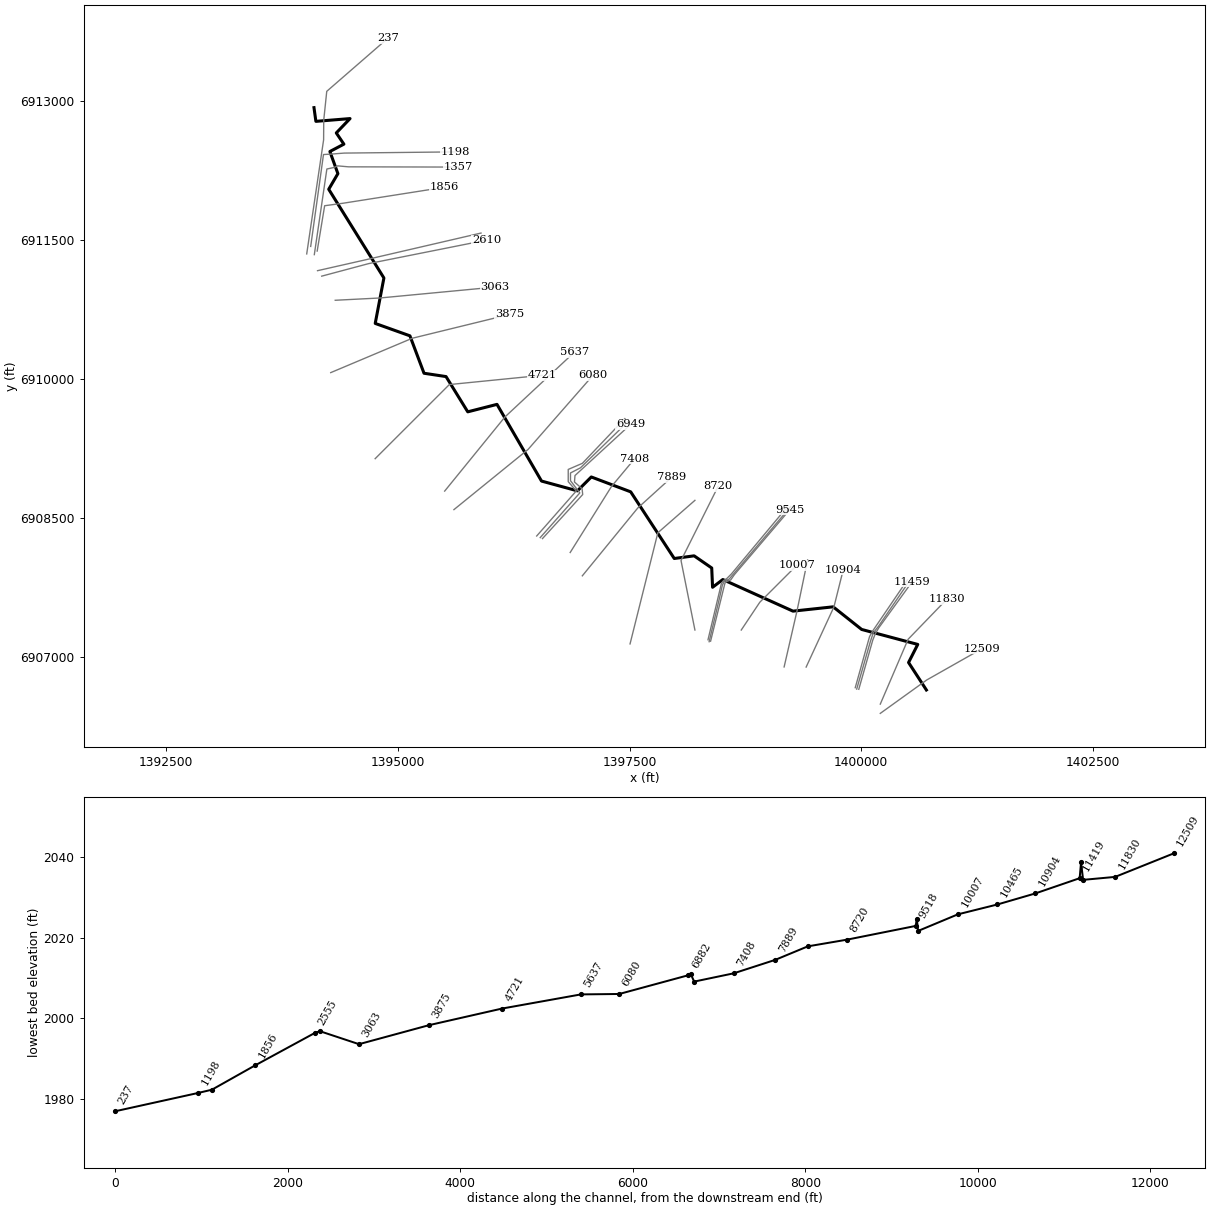
--- Plum Creek Trib4_3.prj (project) ---

Proj Title=Plum Creek Trib4_3 Base Level Engineering
Current Plan=p01
Default Exp/Contr=0.3,0.1
English Units
Geom File=g01
Flow File=f01
Plan File=p01
BEGIN DESCRIPTION:
Plum Creek Trib4_3
END DESCRIPTION:

--- Plum Creek Trib4_3.p01 (plan) ---

Plan Title=Multiple Run
Short Identifier=Multiple
Geom File=g01
Flow File=f01
Subcritical Flow
K Sum by GR= 0
Std Step Tol= 0.01
Critical Tol= 0.01
Num of Std Step Trials= 20
Max Error Tol= 0.3
Flow Tol Ratio= 0.001
Split Flow NTrial= 30
Split Flow Tol= 0.02
Split Flow Ratio= 0.02
Log Output Level= 0
Friction Slope Method= 1
Unsteady Friction Slope Method= 2
Unsteady Bridges Friction Slope Method= 1
Parabolic Critical Depth
Global Vel Dist=  1 , 1 , 1
Global Log Level= 0
CheckData=True
Encroach Param= -1, 0, 0, 0
BEGIN DESCRIPTION:
Multiple Run
END DESCRIPTION:

--- Plum Creek Trib4_3.f01 (steady flow) ---

Flow Title=Multiple
Number of Profiles=7
Profile Names=10-year,25-year,50-year,1pct_min,100-year,1pct_plu,500-year
River Rch & RM= Plum Creek Trib4,Reach-1,12509
     361     517     650     406     809    1614    1272
River Rch & RM= Plum Creek Trib4,Reach-1,8720
     457     662     838     527    1052    2098    1677
River Rch & RM= Plum Creek Trib4,Reach-1,6910
     559     816    1037     654    1305    2604    2096
River Rch & RM= Plum Creek Trib4,Reach-1,1198
     576     842    1072     677    1351    2695    2174
Boundary for River Rch & Prof#=Plum Creek Trib4,Reach-1,1
Up Type=0
Dn Type=3
Dn Slope=0.005
Boundary for River Rch & Prof#=Plum Creek Trib4,Reach-1,2
Up Type=0
Dn Type=3
Dn Slope=0.005
Boundary for River Rch & Prof#=Plum Creek Trib4,Reach-1,3
Up Type=0
Dn Type=3
Dn Slope=0.005
Boundary for River Rch & Prof#=Plum Creek Trib4,Reach-1,4
Up Type=0
Dn Type=3
Dn Slope=0.005
Boundary for River Rch & Prof#=Plum Creek Trib4,Reach-1,5
Up Type=0
Dn Type=3
Dn Slope=0.005
Boundary for River Rch & Prof#=Plum Creek Trib4,Reach-1,6
Up Type=0
Dn Type=3
Dn Slope=0.005
Boundary for River Rch & Prof#=Plum Creek Trib4,Reach-1,7
Up Type=0
Dn Type=3
Dn Slope=0.005

--- Plum Creek Trib4_3.g01 (geometry) ---

Geom Title=Existing Conditions

River Reach=Plum Creek Trib4,Reach-1
Reach XY= 30
      1400702.40      6906640.60      1400509.98      6906937.26
      1400609.12      6907132.46      1400003.89      6907294.22
      1399696.47      6907538.38      1399262.91      6907491.81
      1398505.96      6907833.06      1398395.39      6907749.44
      1398386.26      6907957.69      1398196.36      6908088.98
      1397982.15      6908060.19      1397512.12      6908779.86
      1397087.03      6908940.42      1396937.20      6908790.50
      1396549.81      6908896.32      1396069.53      6909724.33
      1395754.03      6909643.70      1395519.62      6910024.36
      1395282.15      6910060.21      1395130.09      6910464.33
      1394755.56      6910598.21      1394849.27      6911088.97
      1394253.97      6912046.65      1394352.90      6912215.58
      1394266.50      6912454.38      1394417.54      6912533.81
      1394335.51      6912654.90      1394483.94      6912809.85
      1394115.46      6912779.90      1394094.99      6912927.95

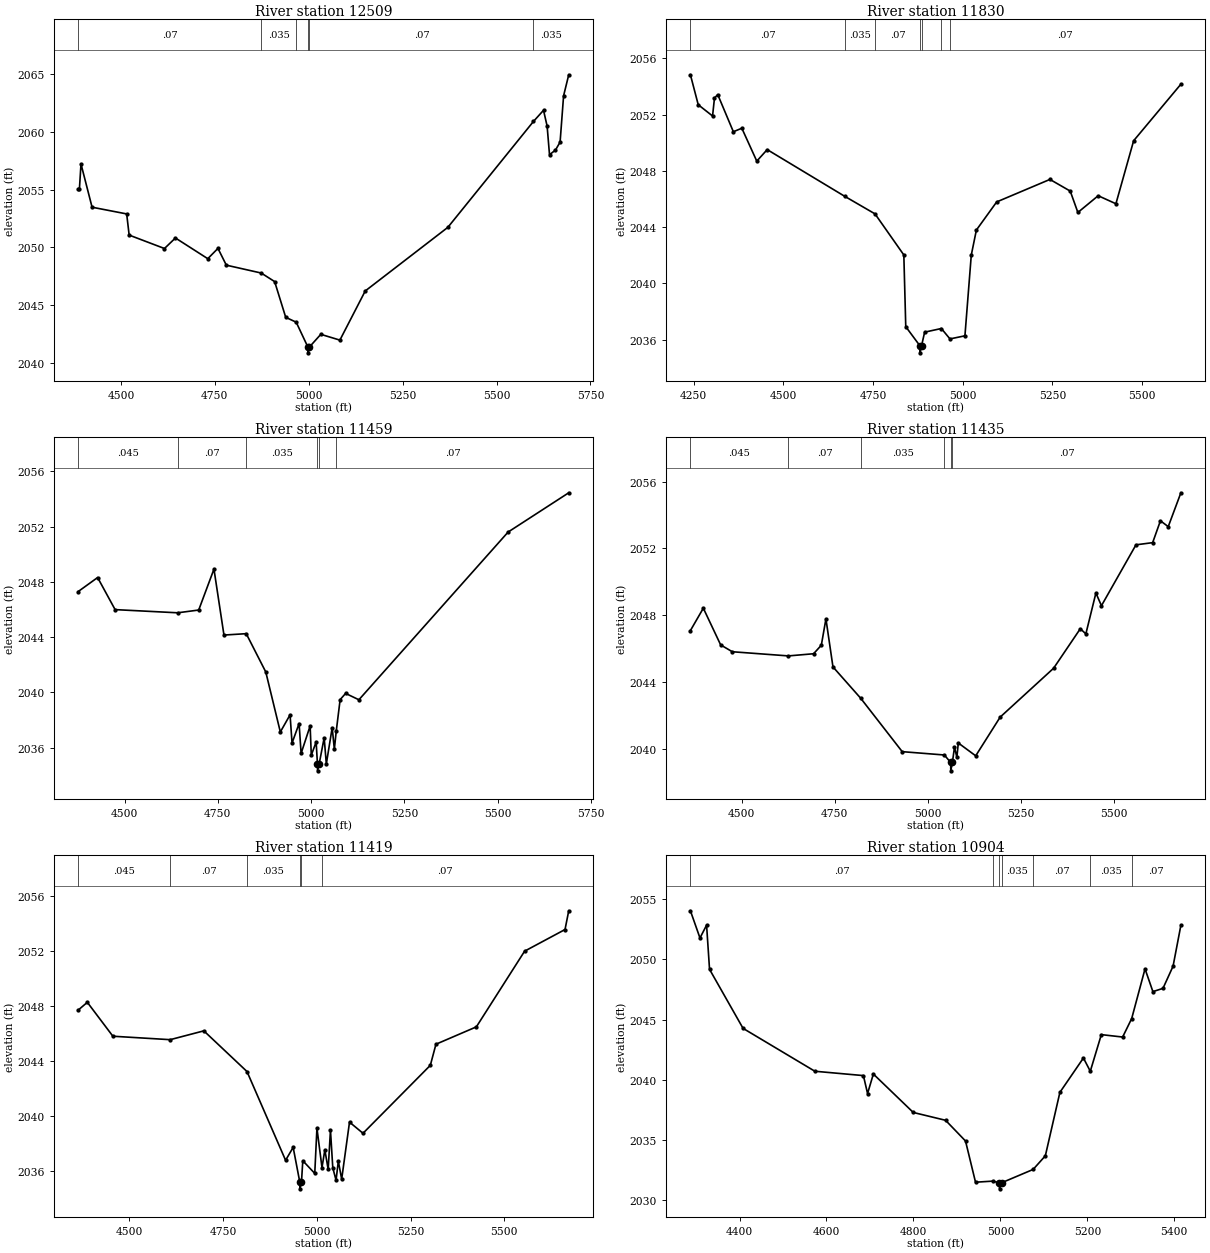
Type RM Length L Ch R = 1,12509,679,679,679
BEGIN DESCRIPTION:
Plum Creek Trib4_3 18.0
END DESCRIPTION:
XS GIS Cut Line= 3
      1400205.02      6906388.02      1400705.61      6906748.29
      1401304.98      6907087.99
#Sta/Elev= 30
  4386.5 2055.05  4389.6 2055.05  4393.8 2057.21  4423.3 2053.47  4515.4 2052.89
  4522.0 2051.06  4616.0 2049.90  4645.2 2050.81  4731.3 2049.02  4758.4 2049.91
  4780.7 2048.46  4873.5 2047.78  4909.3 2047.04  4938.8 2043.95  4966.7 2043.53
  4997.8 2041.38  4998.0 2040.88  5001.8 2041.38  5032.2 2042.48  5083.0 2041.98
  5150.5 2046.23  5370.4 2051.73  5598.4 2060.89  5625.1 2061.85  5634.7 2060.48
  5641.0 2058.01  5656.9 2058.41  5669.2 2059.10  5678.5 2063.10  5692.2 2064.92
#Mann=6,-1,0
  4386.5    0.07       0  4873.5   0.035       0  4966.7    0.07       0
  4997.8    0.07       0  5001.8    0.07       0  5598.4   0.035       0
Bank Sta=4997.8,5001.8
Exp/Cntr=0.3,0.1

Type RM Length L Ch R = 1,11830,371,371,371
BEGIN DESCRIPTION:
Plum Creek Trib4_3 17.0
END DESCRIPTION:
XS GIS Cut Line= 3
      1400204.99      6906487.99      1400505.00      6907188.00
      1400925.67      6907623.38
#Sta/Elev= 30
  4241.3 2054.83  4263.1 2052.70  4303.0 2051.90  4308.4 2053.18  4317.5 2053.42
  4361.0 2050.78  4384.6 2051.03  4426.3 2048.69  4455.3 2049.51  4671.3 2046.19
  4755.8 2044.94  4836.1 2042.02  4841.5 2036.92  4881.0 2035.56  4881.3 2035.06
  4885.5 2035.56  4894.1 2036.53  4940.7 2036.79  4964.7 2036.05  5006.4 2036.27
  5024.1 2042.01  5038.3 2043.79  5094.9 2045.79  5243.3 2047.39  5299.9 2046.56
  5321.2 2045.04  5377.8 2046.23  5427.2 2045.66  5476.6 2050.14  5608.3 2054.16
#Mann=7,-1,0
  4241.3    0.07       0  4671.3   0.035       0  4755.8    0.07       0
  4881.0    0.07       0  4885.5    0.07       0  4940.7   0.035       0
  4964.7    0.07       0
Bank Sta=4881,4885.5
Exp/Cntr=0.3,0.1

Type RM Length L Ch R = 1,11459,24,24,24
BEGIN DESCRIPTION:
Mapping XS 9e2db443
END DESCRIPTION:
XS GIS Cut Line= 5
      1399972.93      6906648.11      1400123.96      6907179.32
      1400151.74      6907248.77      1400188.19      6907311.27
      1400549.32      6907809.55
#Sta/Elev= 30
  4375.8 2047.30  4427.7 2048.31  4474.6 2045.99  4642.4 2045.76  4698.7 2045.96
  4739.6 2048.92  4766.4 2044.15  4826.1 2044.25  4878.5 2041.48  4917.5 2037.14
  4943.6 2038.38  4948.9 2036.34  4967.8 2037.75  4973.2 2035.59  4997.4 2037.58
  5000.5 2035.46  5013.5 2036.42  5017.0 2034.83  5017.3 2034.33  5021.6 2034.83
  5035.0 2036.72  5040.8 2034.83  5056.5 2037.45  5062.3 2035.90  5067.3 2037.18
  5077.8 2039.48  5092.5 2039.93  5128.1 2039.47  5528.1 2051.60  5690.6 2054.44
#Mann=6,-1,0
  4375.8   0.045       0  4642.4    0.07       0  4826.1   0.035       0
  5017.0   0.035       0  5021.6   0.035       0  5067.3    0.07       0
Bank Sta=5017,5021.6
Exp/Cntr=0.3,0.1

Type RM Length L Ch R = 1,11435,16,16,16
BEGIN DESCRIPTION:
Mapping XS 9e70ec49
END DESCRIPTION:
XS GIS Cut Line= 5
      1399950.35      6906649.83      1400097.92      6907163.70
      1400129.17      6907257.45      1400184.72      6907326.89
      1400520.74      6907818.79
#Sta/Elev= 30
  4361.9 2047.08  4396.6 2048.42  4443.2 2046.22  4474.5 2045.81  4625.3 2045.56
  4692.9 2045.69  4713.7 2046.20  4726.1 2047.78  4745.0 2044.90  4819.6 2043.02
  4931.1 2039.82  5044.4 2039.62  5061.3 2039.17  5061.6 2038.67  5065.9 2039.17
  5071.6 2040.09  5078.0 2039.48  5081.8 2040.34  5128.6 2039.57  5194.3 2041.89
  5337.9 2044.82  5409.7 2047.19  5424.6 2046.88  5451.6 2049.33  5466.5 2048.57
  5559.3 2052.22  5604.1 2052.35  5625.0 2053.66  5646.0 2053.31  5680.0 2055.34
#Mann=6,-1,0
  4361.9   0.045       0  4625.3    0.07       0  4819.6   0.035       0
  5044.4    0.07       0  5061.3   0.035       0  5065.9    0.07       0
Bank Sta=5061.3,5065.9
Exp/Cntr=0.3,0.1

Type RM Length L Ch R = 1,11419,515,515,515
BEGIN DESCRIPTION:
Mapping XS 18408d1e
END DESCRIPTION:
XS GIS Cut Line= 4
      1399934.71      6906665.39      1400089.24      6907217.52
      1400122.22      6907276.54      1400497.24      6907828.66
#Sta/Elev= 30
  4363.5 2047.71  4387.7 2048.27  4455.9 2045.81  4608.7 2045.56  4698.5 2046.20
  4813.6 2043.25  4916.6 2036.81  4936.8 2037.75  4954.4 2035.24  4954.7 2034.74
  4959.0 2035.24  4962.5 2036.78  4994.4 2035.86  5000.2 2039.14  5013.7 2036.28
  5021.3 2037.57  5030.2 2036.15  5036.3 2039.00  5042.5 2036.26  5051.2 2035.37
  5057.3 2036.75  5066.2 2035.44  5087.1 2039.58  5123.1 2038.77  5302.7 2043.70
  5317.7 2045.23  5425.5 2046.49  5554.2 2051.98  5662.0 2053.55  5671.9 2054.91
#Mann=6,-1,0
  4363.5   0.045       0  4608.7    0.07       0  4813.6   0.035       0
  4954.4   0.035       0  4959.0   0.035       0  5013.7    0.07       0
Bank Sta=4954.4,4959
Exp/Cntr=0.3,0.1

Type RM Length L Ch R = 1,10904,439,439,439
BEGIN DESCRIPTION:
Plum Creek Trib4_3 15.0
END DESCRIPTION:
XS GIS Cut Line= 3
      1399405.00      6906888.01      1399705.00      6907538.00
      1399805.00      6907938.00
#Sta/Elev= 30
  4287.0 2054.04  4309.0 2051.78  4324.2 2052.85  4331.0 2049.18  4408.1 2044.28
  4573.3 2040.72  4684.9 2040.36  4694.5 2038.87  4707.8 2040.49  4799.6 2037.30
  4873.9 2036.65  4919.8 2034.93  4942.8 2031.51  4982.4 2031.60  4997.7 2031.46
  4998.0 2030.96  5002.6 2031.46  5075.3 2032.57  5103.4 2033.70  5136.9 2038.97
  5191.0 2041.82  5206.8 2040.72  5232.2 2043.76  5281.2 2043.56  5302.0 2045.09
  5332.7 2049.22  5350.8 2047.33  5374.0 2047.60  5397.2 2049.44  5415.2 2052.84
#Mann=7,-1,0
  4287.0    0.07       0  4982.4   0.035       0  4997.7   0.035       0
  5002.6   0.035       0  5075.3    0.07       0  5206.8   0.035       0
  5302.0    0.07       0
Bank Sta=4997.7,5002.6
Exp/Cntr=0.3,0.1

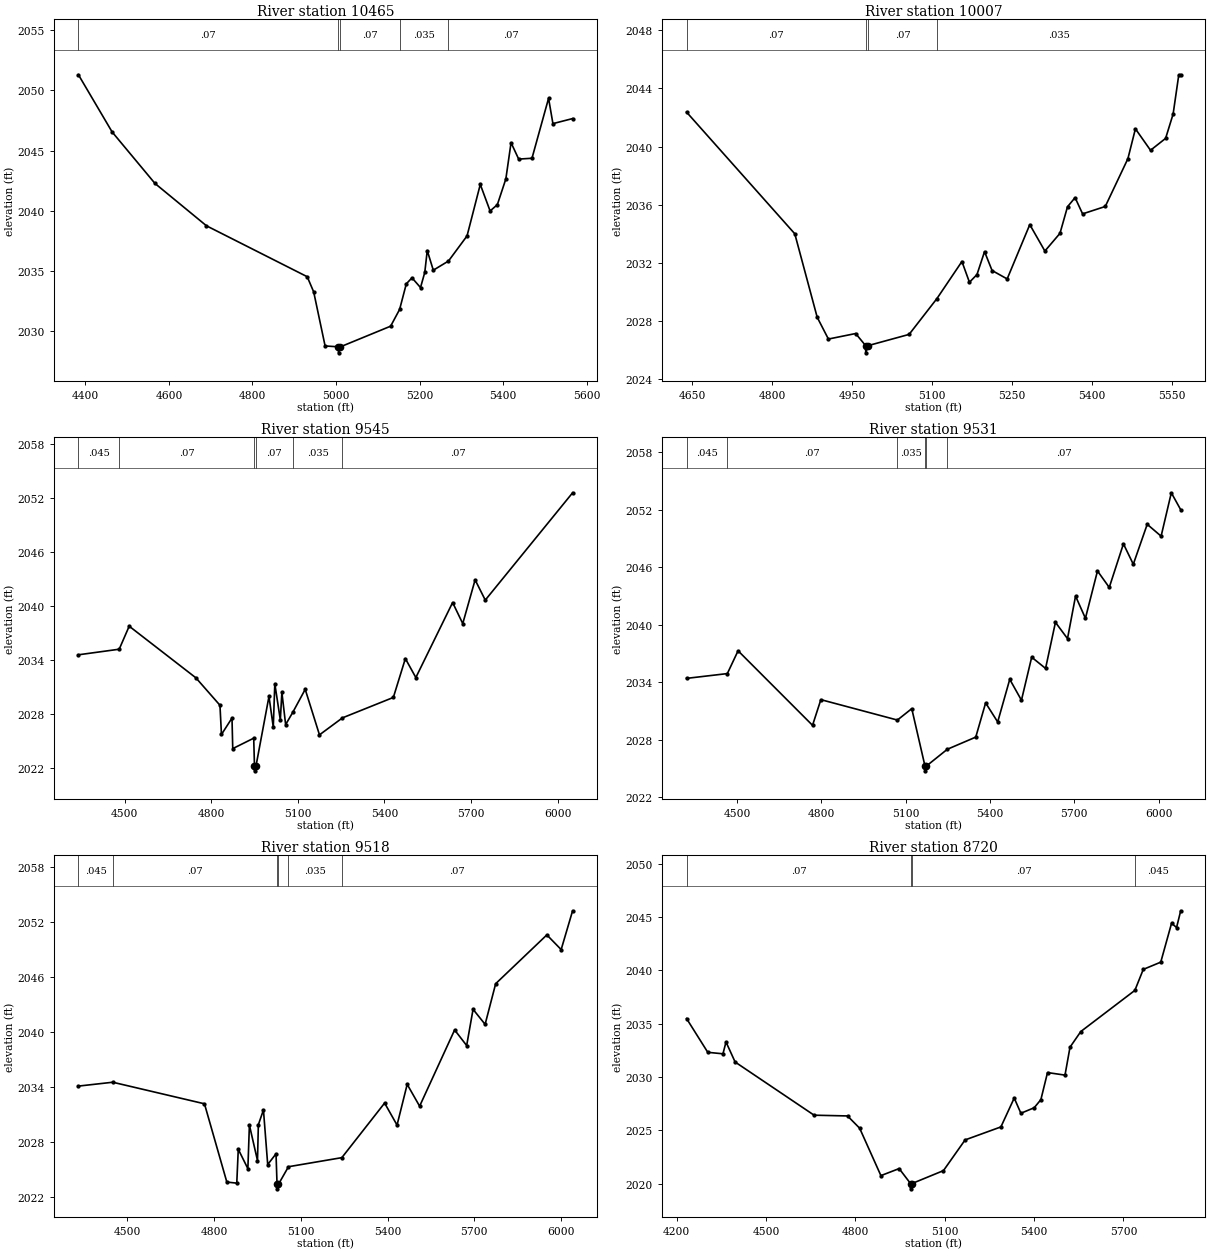
Type RM Length L Ch R = 1,10465,458,458,458
BEGIN DESCRIPTION:
Plum Creek Trib4_3 14.0
END DESCRIPTION:
XS GIS Cut Line= 3
      1399167.36      6906889.41      1399305.00      6907488.00
      1399420.56      6908044.32
#Sta/Elev= 30
  4383.6 2051.28  4464.2 2046.54  4566.8 2042.27  4690.0 2038.76  4931.0 2034.54
  4946.5 2033.28  4973.8 2028.80  5005.5 2028.73  5005.9 2028.23  5010.5 2028.73
  5130.6 2030.44  5152.1 2031.83  5168.1 2033.95  5181.7 2034.45  5202.1 2033.64
  5212.3 2034.90  5218.2 2036.71  5232.7 2035.08  5269.0 2035.84  5313.4 2037.92
  5345.1 2042.19  5368.6 2039.99  5385.9 2040.51  5406.3 2042.65  5418.7 2045.65
  5437.0 2044.29  5468.8 2044.36  5508.5 2049.33  5518.9 2047.23  5566.0 2047.65
#Mann=5,-1,0
  4383.6    0.07       0  5005.5    0.07       0  5010.5    0.07       0
  5152.1   0.035       0  5269.0    0.07       0
Bank Sta=5005.5,5010.5
Exp/Cntr=0.3,0.1

Type RM Length L Ch R = 1,10007,462,462,462
BEGIN DESCRIPTION:
Plum Creek Trib4_3 13.0
END DESCRIPTION:
XS GIS Cut Line= 3
      1398704.98      6907287.97      1398905.00      6907588.00
      1399305.01      6907988.01
#Sta/Elev= 30
  4639.6 2042.37  4842.5 2033.99  4884.5 2028.24  4905.5 2026.74  4956.6 2027.12
  4975.2 2026.29  4975.5 2025.79  4980.2 2026.29  5056.8 2027.06  5109.0 2029.53
  5155.8 2032.08  5169.9 2030.65  5184.0 2031.18  5198.2 2032.76  5212.3 2031.46
  5240.6 2030.88  5283.0 2034.62  5311.3 2032.80  5339.6 2034.02  5353.7 2035.85
  5367.9 2036.48  5382.0 2035.36  5424.5 2035.87  5466.9 2039.16  5481.0 2041.22
  5509.3 2039.74  5537.6 2040.56  5551.7 2042.24  5562.3 2044.94  5565.9 2044.94
#Mann=4,-1,0
  4639.6    0.07       0  4975.2    0.07       0  4980.2    0.07       0
  5109.0   0.035       0
Bank Sta=4975.2,4980.2
Exp/Cntr=0.3,0.1

Type RM Length L Ch R = 1,9545,14,14,14
BEGIN DESCRIPTION:
Mapping XS 9d24b490
END DESCRIPTION:
XS GIS Cut Line= 6
      1398373.97      6907167.21      1398528.47      6907792.17
      1398542.36      6907809.53      1398590.97      6907828.63
      1398630.90      6907885.92      1399229.83      6908589.01
#Sta/Elev= 30
  4340.2 2034.57  4481.4 2035.19  4516.0 2037.75  4747.0 2032.01  4830.4 2028.96
  4835.6 2025.71  4872.1 2027.54  4874.7 2024.14  4947.3 2025.30  4950.0 2022.17
  4950.3 2021.67  4955.0 2022.17  5000.2 2029.94  5015.1 2026.53  5020.4 2031.36
  5039.5 2027.33  5044.9 2030.39  5057.9 2026.81  5082.6 2028.17  5125.7 2030.73
  5175.1 2025.67  5254.8 2027.56  5431.0 2029.83  5472.6 2034.15  5508.9 2032.04
  5636.3 2040.38  5671.4 2038.04  5714.2 2042.90  5749.4 2040.65  6051.9 2052.58
#Mann=6,-1,0
  4340.2   0.045       0  4481.4    0.07       0  4950.0    0.07       0
  4955.0    0.07       0  5082.6   0.035       0  5254.8    0.07       0
Bank Sta=4950,4955
Exp/Cntr=0.3,0.1

Type RM Length L Ch R = 1,9531,13,13,13
BEGIN DESCRIPTION:
Mapping XS 37374494
END DESCRIPTION:
XS GIS Cut Line= 6
      1398358.34      6907162.00      1398469.44      6907630.71
      1398500.69      6907771.33      1398521.53      6907811.27
      1398575.35      6907839.04      1399238.56      6908622.05
#Sta/Elev= 30
  4320.7 2034.39  4465.8 2034.89  4504.0 2037.27  4768.8 2029.49  4798.4 2032.17
  5070.6 2030.04  5121.7 2031.23  5168.7 2025.24  5169.1 2024.74  5173.7 2025.24
  5248.1 2026.99  5349.3 2028.26  5384.4 2031.83  5427.3 2029.84  5470.2 2034.29
  5511.8 2032.11  5548.2 2036.60  5597.6 2035.43  5632.7 2040.24  5675.6 2038.54
  5704.2 2042.98  5739.3 2040.66  5782.2 2045.60  5824.1 2043.88  5874.5 2048.43
  5909.6 2046.30  5959.1 2050.47  6008.5 2049.23  6044.8 2053.76  6078.2 2051.99
#Mann=6,-1,0
  4320.7   0.045       0  4465.8    0.07       0  5070.6   0.035       0
  5168.7    0.07       0  5173.7   0.035       0  5248.1    0.07       0
Bank Sta=5168.7,5173.7
Exp/Cntr=0.3,0.1

Type RM Length L Ch R = 1,9518,798,798,798
BEGIN DESCRIPTION:
Mapping XS 622ea107
END DESCRIPTION:
XS GIS Cut Line= 6
      1398346.19      6907182.82      1398490.28      6907788.70
      1398512.85      6907819.95      1398549.30      6907844.25
      1398599.65      6907894.60      1399196.88      6908611.63
#Sta/Elev= 30
  4330.5 2034.12  4449.3 2034.54  4766.5 2032.19  4843.9 2023.66  4878.3 2023.54
  4883.5 2027.23  4916.7 2025.12  4922.0 2029.87  4950.0 2026.00  4953.0 2029.91
  4970.6 2031.52  4985.3 2025.57  5014.1 2026.74  5017.6 2023.42  5017.9 2022.92
  5022.6 2023.42  5057.1 2025.33  5241.8 2026.32  5389.8 2032.27  5432.8 2029.87
  5467.9 2034.31  5510.9 2031.93  5632.0 2040.24  5673.7 2038.54  5695.8 2042.49
  5737.5 2040.85  5774.0 2045.28  5951.1 2050.60  6000.6 2049.00  6040.2 2053.23
#Mann=6,-1,0
  4330.5   0.045       0  4449.3    0.07       0  5017.6    0.07       0
  5022.6    0.07       0  5057.1   0.035       0  5241.8    0.07       0
Bank Sta=5017.6,5022.6
Exp/Cntr=0.3,0.1

Type RM Length L Ch R = 1,8720,453,453,453
BEGIN DESCRIPTION:
Plum Creek Trib4_3 11.0
END DESCRIPTION:
XS GIS Cut Line= 3
      1398204.99      6907288.04      1398055.00      6908038.00
      1398454.98      6908837.96
#Sta/Elev= 30
  4233.2 2035.49  4304.5 2032.32  4355.5 2032.18  4365.7 2033.29  4396.3 2031.41
  4661.5 2026.42  4773.7 2026.35  4814.4 2025.20  4885.8 2020.75  4947.0 2021.41
  4985.2 2020.01  4985.6 2019.51  4990.4 2020.01  5095.8 2021.22  5168.5 2024.10
  5288.7 2025.32  5333.4 2028.03  5355.8 2026.60  5400.5 2027.12  5422.9 2027.88
  5445.2 2030.42  5503.9 2030.18  5520.7 2032.80  5557.0 2034.27  5738.5 2038.13
  5766.7 2040.10  5825.4 2040.78  5861.7 2044.43  5878.5 2044.03  5892.4 2045.60
#Mann=4,-1,0
  4233.2    0.07       0  4985.2    0.07       0  4990.4    0.07       0
  5738.5   0.045       0
Bank Sta=4985.2,4990.4
Exp/Cntr=0.3,0.1

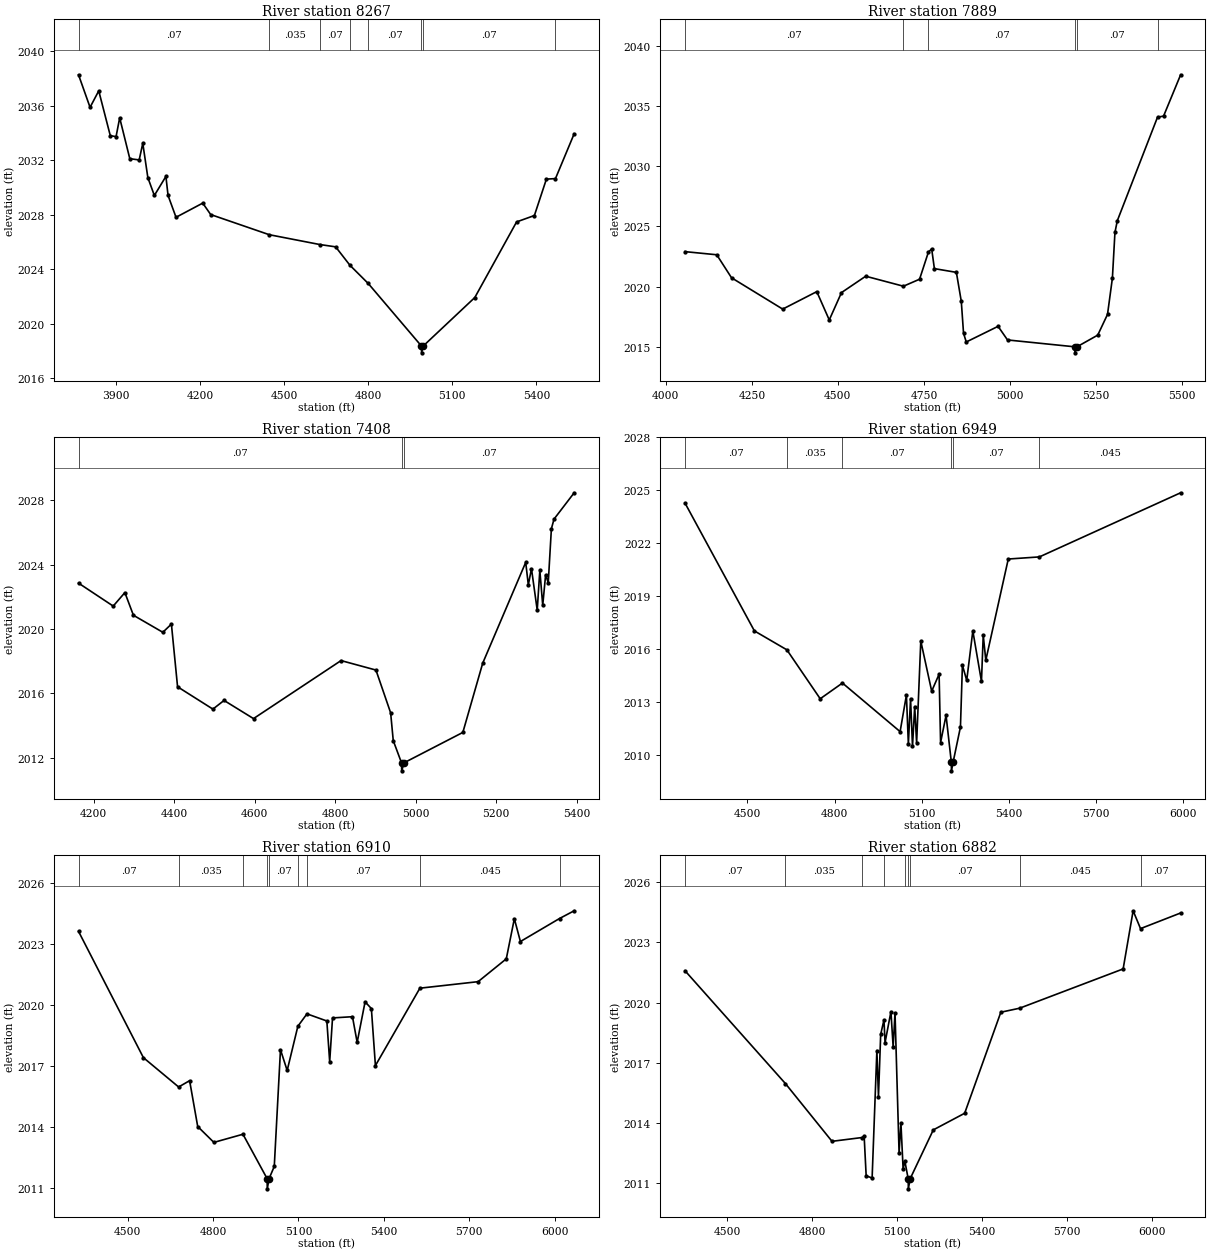
Type RM Length L Ch R = 1,8267,378,378,378
BEGIN DESCRIPTION:
Plum Creek Trib4_3 10.0
END DESCRIPTION:
XS GIS Cut Line= 3
      1397505.00      6907138.00      1397805.00      6908338.00
      1398204.97      6908687.97
#Sta/Elev= 30
  3766.2 2038.27  3807.4 2035.88  3838.4 2037.09  3879.6 2033.80  3900.2 2033.73
  3913.1 2035.11  3949.2 2032.11  3982.7 2032.02  3995.5 2033.24  4013.6 2030.72
  4036.8 2029.41  4078.0 2030.81  4085.7 2029.41  4114.1 2027.81  4209.4 2028.85
  4237.8 2028.01  4446.9 2026.53  4627.1 2025.81  4683.6 2025.64  4734.5 2024.29
  4799.9 2022.95  4989.7 2018.36  4990.2 2017.86  4996.0 2018.36  5180.1 2021.92
  5329.2 2027.47  5392.7 2027.94  5435.5 2030.61  5467.9 2030.65  5534.6 2033.94
#Mann=8,-1,0
  3766.2    0.07       0  4446.9   0.035       0  4627.1    0.07       0
  4734.5   0.035       0  4799.9    0.07       0  4989.7    0.07       0
  4996.0    0.07       0  5467.9   0.045       0
Bank Sta=4989.7,4996
Exp/Cntr=0.3,0.1

Type RM Length L Ch R = 1,7889,481,481,481
BEGIN DESCRIPTION:
Plum Creek Trib4_3 9.0
END DESCRIPTION:
XS GIS Cut Line= 3
      1396990.29      6907873.20      1397587.69      6908604.75
      1397954.97      6908937.97
#Sta/Elev= 30
  4055.7 2022.91  4148.0 2022.65  4191.0 2020.74  4339.7 2018.14  4438.7 2019.59
  4475.0 2017.24  4510.5 2019.51  4580.9 2020.87  4690.5 2020.04  4737.4 2020.62
  4763.1 2022.87  4772.6 2023.14  4780.5 2021.50  4844.4 2021.19  4858.7 2018.78
  4865.2 2016.14  4873.1 2015.41  4965.6 2016.71  4993.0 2015.58  5188.5 2015.01
  5189.0 2014.51  5194.8 2015.01  5255.2 2015.98  5283.6 2017.70  5297.8 2020.71
  5305.2 2024.50  5312.0 2025.47  5428.9 2034.07  5446.5 2034.16  5496.1 2037.59
#Mann=6,-1,0
  4055.7    0.07       0  4690.5   0.035       0  4763.1    0.07       0
  5188.5    0.07       0  5194.8    0.07       0  5428.9   0.045       0
Bank Sta=5188.5,5194.8
Exp/Cntr=0.3,0.1

Type RM Length L Ch R = 1,7408,459,459,459
BEGIN DESCRIPTION:
Plum Creek Trib4_3 8.0
END DESCRIPTION:
XS GIS Cut Line= 3
      1396859.19      6908124.90      1397305.00      6908838.00
      1397555.00      6909138.00
#Sta/Elev= 30
  4162.2 2022.86  4248.4 2021.43  4277.4 2022.27  4298.6 2020.86  4371.7 2019.80
  4393.0 2020.31  4408.3 2016.41  4496.1 2015.02  4523.8 2015.56  4597.0 2014.43
  4814.5 2018.04  4901.2 2017.45  4937.7 2014.79  4944.2 2013.06  4964.7 2011.68
  4965.2 2011.18  4971.0 2011.68  5117.1 2013.57  5166.5 2017.88  5273.3 2024.15
  5279.8 2022.75  5287.6 2023.76  5301.9 2021.18  5308.4 2023.65  5315.6 2021.48
  5322.8 2023.38  5329.3 2022.88  5337.1 2026.24  5343.6 2026.84  5393.7 2028.48
#Mann=3,-1,0
  4162.2    0.07       0  4964.7    0.07       0  4971.0    0.07       0
Bank Sta=4964.7,4971
Exp/Cntr=0.3,0.1

Type RM Length L Ch R = 1,6949,39,39,39
BEGIN DESCRIPTION:
Mapping XS 23e333ce
END DESCRIPTION:
XS GIS Cut Line= 6
      1396560.27      6908275.29      1396994.33      6908751.02
      1396987.38      6908813.52      1396905.21      6908886.21
      1396910.99      6908955.88      1397510.87      6909507.97
#Sta/Elev= 30
  4285.5 2024.29  4524.3 2017.05  4635.9 2015.98  4750.6 2013.21  4827.1 2014.10
  5025.4 2011.35  5047.1 2013.42  5053.8 2010.64  5061.3 2013.22  5068.0 2010.52
  5075.6 2012.77  5082.2 2010.71  5096.5 2016.48  5134.0 2013.64  5159.5 2014.60
  5164.6 2010.73  5183.4 2012.27  5201.5 2009.63  5202.0 2009.13  5207.8 2009.63
  5232.9 2011.61  5239.7 2015.11  5254.5 2014.25  5275.5 2017.05  5305.2 2014.19
  5311.3 2016.81  5320.1 2015.39  5397.4 2021.12  5504.4 2021.24  5990.2 2024.87
#Mann=6,-1,0
  4285.5    0.07       0  4635.9   0.035       0  4827.1    0.07       0
  5201.5    0.07       0  5207.8    0.07       0  5504.4   0.045       0
Bank Sta=5201.5,5207.8
Exp/Cntr=0.3,0.1

Type RM Length L Ch R = 1,6910,28,28,28
BEGIN DESCRIPTION:
Mapping XS 62ff7d00
END DESCRIPTION:
XS GIS Cut Line= 6
      1396536.00      6908285.75      1396963.08      6908768.38
      1396862.38      6908900.33      1396862.38      6908983.66
      1396970.02      6909039.22      1397487.35      6909542.65
#Sta/Elev= 30
  4327.5 2023.62  4555.4 2017.42  4679.1 2015.98  4717.7 2016.29  4746.1 2014.04
  4802.9 2013.26  4905.0 2013.66  4989.9 2011.48  4990.4 2010.98  4996.7 2011.48
  5015.0 2012.08  5036.8 2017.81  5060.3 2016.79  5097.8 2018.96  5129.8 2019.57
  5199.6 2019.22  5209.6 2017.22  5219.6 2019.37  5289.6 2019.43  5306.1 2018.17
  5333.9 2020.16  5356.0 2019.83  5370.2 2017.03  5526.4 2020.83  5730.8 2021.15
  5829.8 2022.27  5858.1 2024.24  5879.4 2023.12  6016.7 2024.25  6068.2 2024.63
#Mann=9,-1,0
  4327.5    0.07       0  4679.1   0.035       0  4905.0    0.07       0
  4989.9    0.07       0  4996.7    0.07       0  5097.8   0.035       0
  5129.8    0.07       0  5526.4   0.045       0  6016.7    0.07       0
Bank Sta=4989.9,4996.7
Exp/Cntr=0.3,0.1

Type RM Length L Ch R = 1,6882,802,802,802
BEGIN DESCRIPTION:
Mapping XS 17c3e775
END DESCRIPTION:
XS GIS Cut Line= 6
      1396497.82      6908303.13      1396924.88      6908789.22
      1396838.08      6908889.91      1396838.08      6909021.86
      1396990.86      6909087.83      1397449.20      6909570.48
#Sta/Elev= 30
  4351.9 2021.59  4706.3 2015.96  4870.6 2013.08  4976.8 2013.27  4984.0 2013.34
  4991.1 2011.36  5012.1 2011.25  5028.9 2017.61  5034.5 2015.31  5042.3 2018.41
  5053.9 2019.14  5057.7 2018.00  5078.5 2019.55  5086.3 2017.79  5092.9 2019.49
  5107.2 2012.52  5113.7 2014.00  5121.5 2011.69  5127.3 2012.11  5139.4 2011.21
  5139.9 2010.71  5146.2 2011.21  5227.9 2013.65  5338.6 2014.48  5466.2 2019.52
  5532.5 2019.72  5897.7 2021.68  5932.9 2024.58  5959.0 2023.69  6100.5 2024.47
#Mann=9,-1,0
  4351.9    0.07       0  4706.3   0.035       0  4976.8    0.07       0
  5053.9   0.035       0  5127.3    0.07       0  5139.4    0.07       0
  5146.2    0.07       0  5532.5   0.045       0  5959.0    0.07       0
Bank Sta=5139.4,5146.2
Exp/Cntr=0.3,0.1

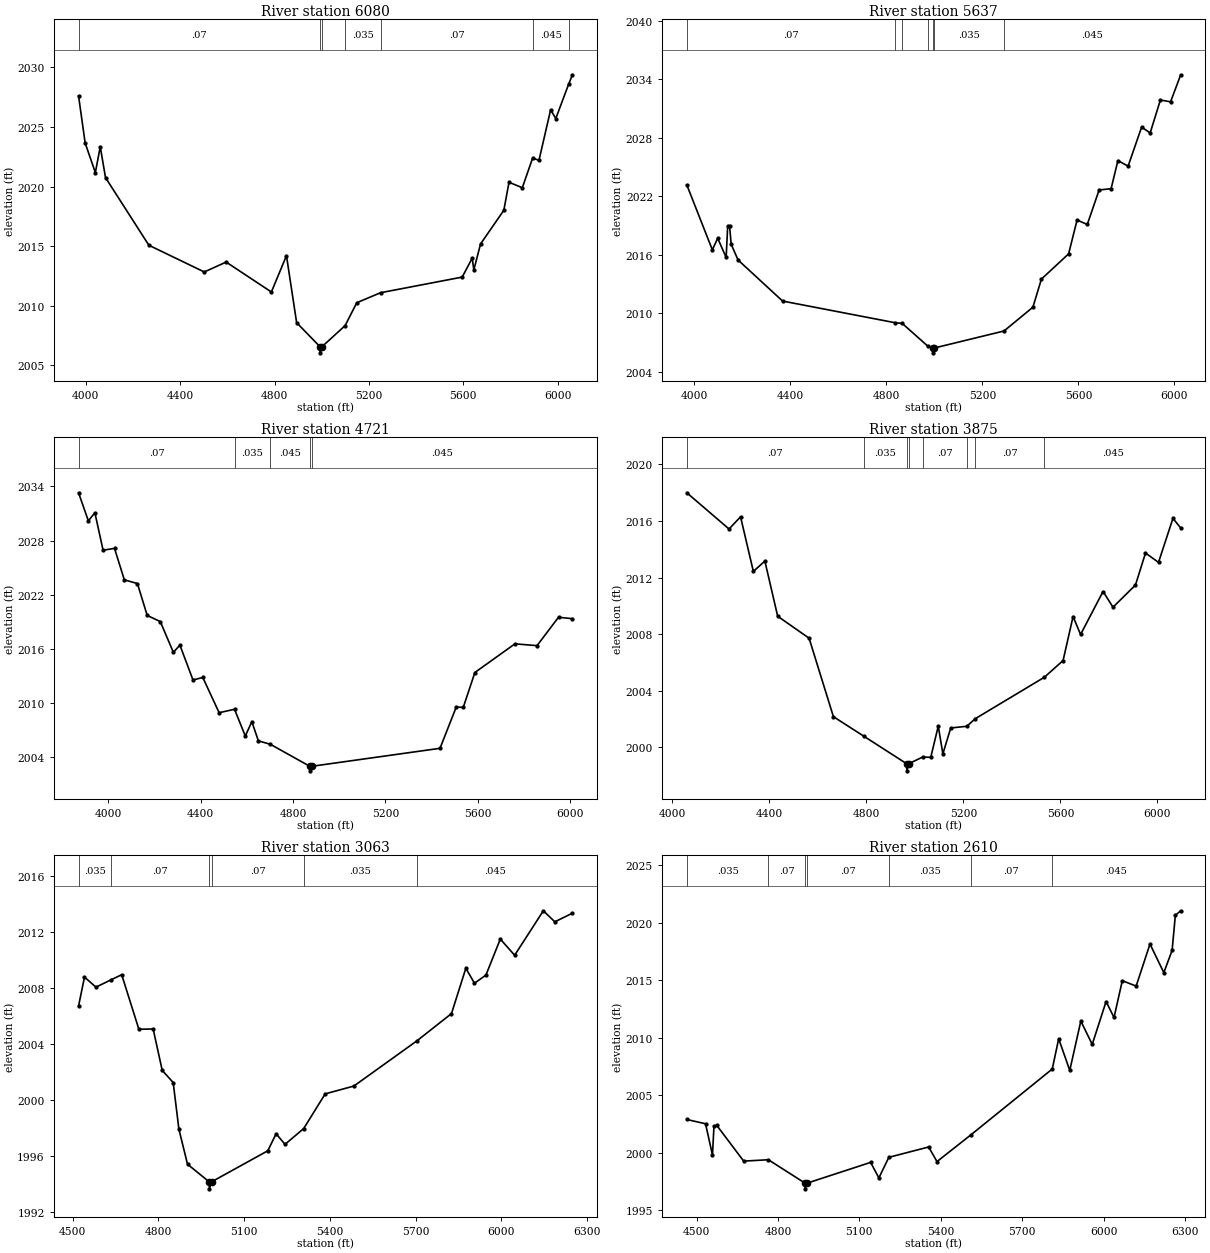
Type RM Length L Ch R = 1,6080,443,443,443
BEGIN DESCRIPTION:
Plum Creek Trib4_3 6.0
END DESCRIPTION:
XS GIS Cut Line= 3
      1395604.96      6908587.97      1396405.00      6909238.00
      1397104.97      6910037.97
#Sta/Elev= 30
  3969.1 2027.60  3997.1 2023.65  4040.3 2021.17  4061.1 2023.34  4083.4 2020.75
  4267.2 2015.08  4502.1 2012.84  4594.8 2013.67  4786.6 2011.16  4850.5 2014.21
  4893.6 2008.59  4993.3 2006.56  4993.8 2006.06  5000.2 2006.56  5099.1 2008.34
  5148.5 2010.26  5249.5 2011.10  5595.5 2012.41  5637.7 2013.99  5644.9 2013.02
  5673.3 2015.19  5772.0 2018.01  5793.9 2020.36  5850.3 2019.90  5894.1 2022.39
  5921.0 2022.20  5970.4 2026.44  5992.2 2025.70  6046.9 2028.59  6062.9 2029.37
#Mann=7,-1,0
  3969.1    0.07       0  4993.3    0.07       0  5000.2    0.07       0
  5099.1   0.035       0  5249.5    0.07       0  5894.1   0.045       0
  6046.9    0.07       0
Bank Sta=4993.3,5000.2
Exp/Cntr=0.3,0.1

Type RM Length L Ch R = 1,5637,916,916,916
BEGIN DESCRIPTION:
Plum Creek Trib4_3 5.0
END DESCRIPTION:
XS GIS Cut Line= 3
      1395504.98      6908787.98      1396155.00      6909588.00
      1396904.99      6910287.99
#Sta/Elev= 30
  3969.4 2023.18  4075.7 2016.52  4098.0 2017.71  4133.2 2015.74  4139.7 2018.99
  4147.6 2018.95  4154.0 2017.10  4182.8 2015.48  4368.1 2011.27  4836.3 2009.05
  4866.3 2008.98  4974.2 2006.62  4993.4 2006.46  4993.9 2005.96  5000.5 2006.46
  5290.3 2008.20  5410.6 2010.64  5446.0 2013.52  5559.3 2016.11  5594.5 2019.58
  5637.0 2019.12  5686.3 2022.66  5736.2 2022.79  5764.5 2025.67  5807.0 2025.10
  5863.2 2029.10  5898.9 2028.51  5941.4 2031.88  5983.9 2031.70  6026.1 2034.47
#Mann=7,-1,0
  3969.4    0.07       0  4836.3   0.035       0  4866.3    0.07       0
  4974.2   0.035       0  4993.4   0.035       0  5000.5   0.035       0
  5290.3   0.045       0
Bank Sta=4993.4,5000.5
Exp/Cntr=0.3,0.1

Type RM Length L Ch R = 1,4721,846,846,846
BEGIN DESCRIPTION:
Plum Creek Trib4_3 4.0
END DESCRIPTION:
XS GIS Cut Line= 3
      1394754.99      6909137.99      1395555.00      6909938.00
      1396555.03      6910038.00
#Sta/Elev= 30
  3872.4 2033.30  3914.8 2030.19  3943.1 2031.08  3978.5 2026.93  4028.0 2027.13
  4070.4 2023.64  4127.0 2023.23  4169.4 2019.69  4226.0 2019.01  4282.5 2015.60
  4310.8 2016.40  4367.4 2012.53  4409.8 2012.81  4480.5 2008.90  4547.1 2009.28
  4593.7 2006.31  4621.9 2007.91  4650.2 2005.78  4702.5 2005.39  4873.0 2002.95
  4873.5 2002.45  4880.1 2002.95  5435.9 2004.95  5506.3 2009.54  5536.4 2009.48
  5586.7 2013.36  5760.0 2016.54  5855.5 2016.34  5948.5 2019.49  6008.8 2019.33
#Mann=5,-1,0
  3872.4    0.07       0  4547.1   0.035       0  4702.5   0.045       0
  4873.0   0.045       0  4880.1   0.045       0
Bank Sta=4873,4880.1
Exp/Cntr=0.3,0.1

Type RM Length L Ch R = 1,3875,812,812,812
BEGIN DESCRIPTION:
Plum Creek Trib4_3 3.0
END DESCRIPTION:
XS GIS Cut Line= 3
      1394275.57      6910066.99      1395155.00      6910438.00
      1396206.14      6910695.47
#Sta/Elev= 30
  4059.5 2018.00  4233.6 2015.44  4281.1 2016.30  4333.9 2012.44  4381.4 2013.17
  4434.2 2009.27  4563.7 2007.72  4664.0 2002.17  4790.3 2000.78  4966.3 1998.84
  4966.8 1998.34  4974.2 1998.84  5031.4 1999.31  5065.5 1999.30  5096.4 2001.50
  5115.4 1999.54  5147.8 2001.37  5213.9 2001.49  5249.3 2002.03  5534.2 2004.96
  5611.1 2006.14  5652.3 2009.25  5683.2 2007.98  5775.9 2011.02  5817.0 2009.91
  5909.7 2011.48  5950.9 2013.74  6004.6 2013.08  6064.1 2016.19  6096.2 2015.51
#Mann=8,-1,0
  4059.5    0.07       0  4790.3   0.035       0  4966.3   0.035       0
  4974.2   0.035       0  5031.4    0.07       0  5213.9   0.035       0
  5249.3    0.07       0  5534.2   0.045       0
Bank Sta=4966.3,4974.2
Exp/Cntr=0.3,0.1

Type RM Length L Ch R = 1,3063,453,453,453
BEGIN DESCRIPTION:
Plum Creek Trib4_3 2.0
END DESCRIPTION:
XS GIS Cut Line= 3
      1394324.22      6910848.25      1394805.45      6910872.81
      1396046.41      6910990.61
#Sta/Elev= 30
  4520.8 2006.70  4541.6 2008.77  4581.7 2008.05  4636.1 2008.59  4671.8 2008.94
  4731.9 2005.04  4781.9 2005.06  4813.6 2002.10  4852.0 2001.23  4872.0 1997.89
  4902.1 1995.39  4978.1 1994.13  4978.6 1993.63  4986.3 1994.13  5183.0 1996.35
  5212.2 1997.57  5243.3 1996.81  5308.7 1997.94  5383.9 2000.42  5484.4 2000.98
  5705.5 2004.22  5825.9 2006.16  5876.1 2009.40  5906.3 2008.33  5946.4 2008.91
  5996.7 2011.49  6046.9 2010.33  6147.3 2013.51  6187.5 2012.72  6249.2 2013.34
#Mann=6,-1,0
  4520.8   0.035       0  4636.1    0.07       0  4978.1    0.07       0
  4986.3    0.07       0  5308.7   0.035       0  5705.5   0.045       0
Bank Sta=4978.1,4986.3
Exp/Cntr=0.3,0.1

Type RM Length L Ch R = 1,2610,55,55,55
BEGIN DESCRIPTION:
Mapping XS c86e2c98
END DESCRIPTION:
XS GIS Cut Line= 3
      1394178.33      6911108.65      1394685.30      6911244.08
      1395956.12      6911497.55
#Sta/Elev= 30
  4464.0 2002.87  4533.0 2002.50  4558.6 1999.78  4564.1 2002.29  4574.4 2002.36
  4673.7 1999.25  4764.5 1999.37  4899.6 1997.34  4900.1 1996.84  4908.0 1997.34
  5141.6 1999.14  5172.0 1997.79  5208.7 1999.58  5355.5 2000.48  5386.1 1999.21
  5509.9 2001.51  5811.1 2007.26  5834.8 2009.89  5875.6 2007.14  5916.4 2011.43
  5958.4 2009.40  6009.5 2013.13  6038.7 2011.74  6069.3 2014.94  6120.3 2014.47
  6171.3 2018.13  6222.3 2015.64  6252.9 2017.58  6264.8 2020.63  6284.6 2021.02
#Mann=7,-1,0
  4464.0   0.035       0  4764.5    0.07       0  4899.6    0.07       0
  4908.0    0.07       0  5208.7   0.035       0  5509.9    0.07       0
  5811.1   0.045       0
Bank Sta=4899.6,4908
Exp/Cntr=0.3,0.1

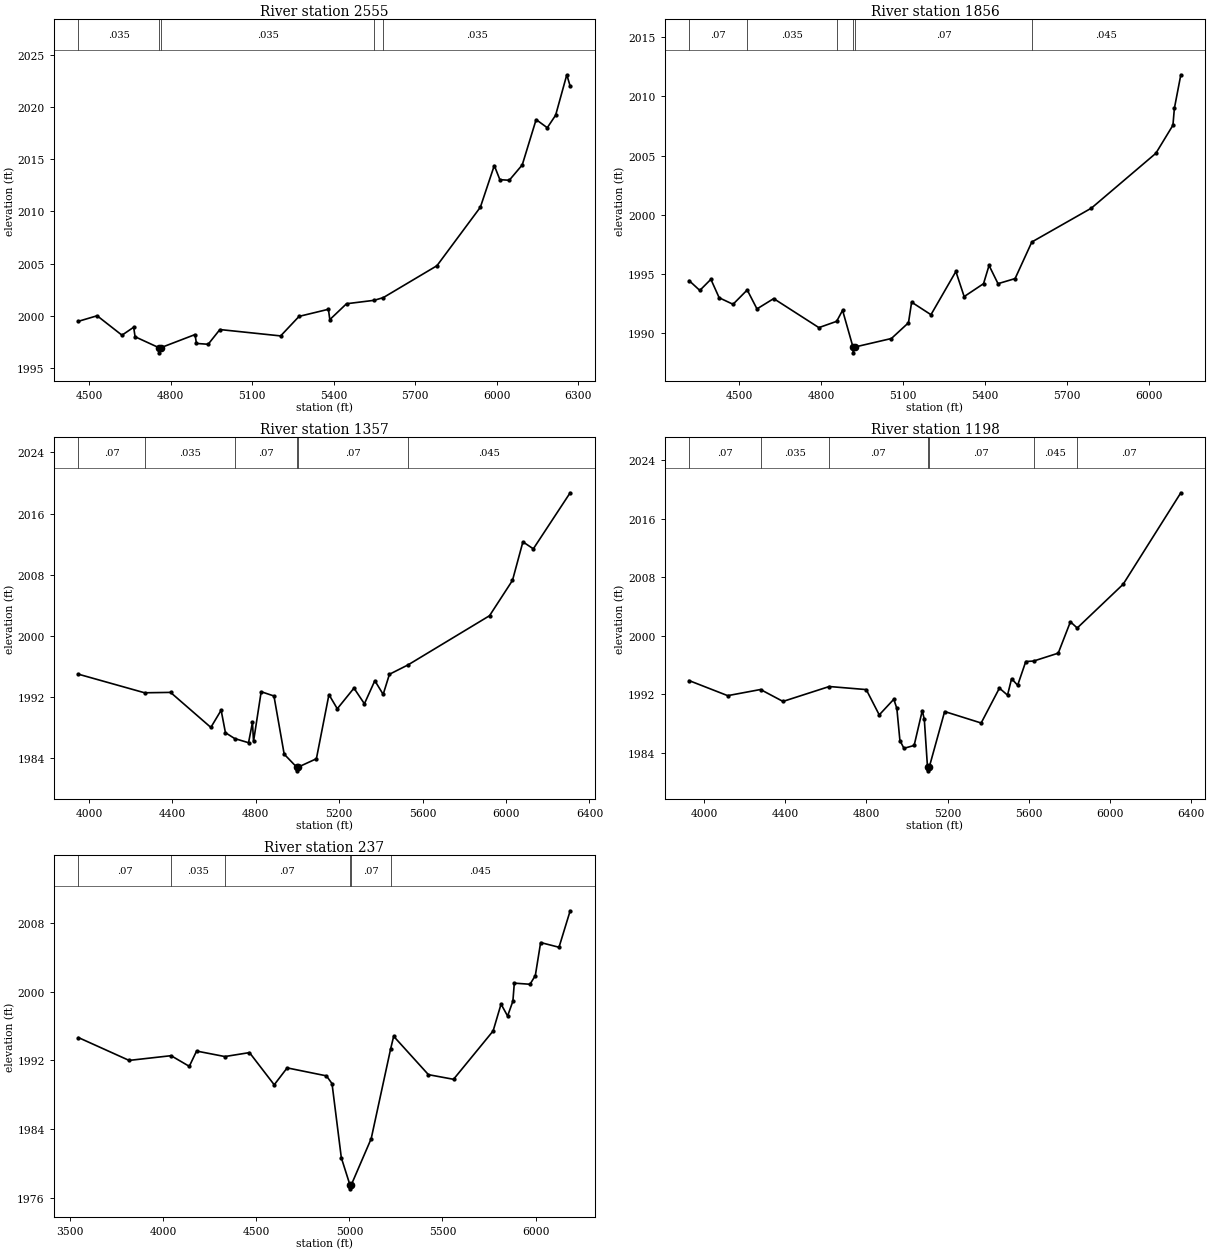
Type RM Length L Ch R = 1,2555,699,699,699
BEGIN DESCRIPTION:
Mapping XS 8bef66a3
END DESCRIPTION:
XS GIS Cut Line= 3
      1394133.25      6911167.70      1394654.05      6911285.74
      1395897.07      6911573.93
#Sta/Elev= 30
  4460.8 1999.48  4529.6 2000.01  4621.0 1998.15  4664.1 1998.91  4669.3 1998.00
  4756.4 1996.96  4756.9 1996.46  4764.8 1996.96  4890.0 1998.21  4895.1 1997.36
  4938.3 1997.28  4981.4 1998.69  5205.1 1998.08  5272.9 1999.95  5380.9 2000.63
  5386.1 1999.64  5447.5 2001.16  5549.6 2001.49  5583.1 2001.75  5780.4 2004.80
  5940.2 2010.40  5991.5 2014.39  6012.0 2013.04  6046.6 2012.98  6094.4 2014.45
  6145.5 2018.79  6186.5 2018.01  6217.3 2019.21  6258.4 2023.08  6270.8 2021.99
#Mann=5,-1,0
  4460.8   0.035       0  4756.4   0.035       0  4764.8   0.035       0
  5549.6    0.07       0  5583.1   0.035       0
Bank Sta=4756.4,4764.8
Exp/Cntr=0.3,0.1

Type RM Length L Ch R = 1,1856,499,499,499
BEGIN DESCRIPTION:
Mapping XS 1b4e20ae
END DESCRIPTION:
XS GIS Cut Line= 4
      1394129.33      6911379.37      1394210.06      6911868.96
      1394407.12      6911895.64      1395498.31      6912067.52
#Sta/Elev= 30
  4316.0 1994.45  4355.2 1993.62  4395.7 1994.56  4426.1 1993.00  4476.8 1992.45
  4528.7 1993.66  4564.4 1992.06  4625.6 1992.93  4791.0 1990.48  4856.0 1991.01
  4877.7 1991.94  4915.7 1988.85  4916.2 1988.35  4924.2 1988.85  5056.4 1989.56
  5118.9 1990.89  5130.4 1992.63  5201.2 1991.57  5292.4 1995.22  5322.7 1993.10
  5393.6 1994.19  5413.8 1995.73  5446.6 1994.19  5509.1 1994.62  5570.4 1997.71
  5788.4 2000.57  6024.3 2005.20  6086.8 2007.57  6092.1 2009.00  6115.7 2011.83
#Mann=6,-1,0
  4316.0    0.07       0  4528.7   0.035       0  4856.0    0.07       0
  4915.7    0.07       0  4924.2    0.07       0  5570.4   0.045       0
Bank Sta=4915.7,4924.2
Exp/Cntr=0.3,0.1

Type RM Length L Ch R = 1,1357,159,159,159
BEGIN DESCRIPTION:
Mapping XS 7e2dd905
END DESCRIPTION:
XS GIS Cut Line= 6
      1394098.53      6911341.00      1394233.94      6912265.43
      1394306.86      6912281.06      1394351.13      6912299.29
      1394468.32      6912288.87      1395651.62      6912286.27
#Sta/Elev= 30
  3949.9 1994.99  4267.1 1992.56  4391.6 1992.61  4584.8 1988.03  4634.1 1990.28
  4654.7 1987.34  4699.2 1986.57  4765.5 1986.03  4784.3 1988.68  4789.4 1986.20
  4826.1 1992.70  4887.3 1992.14  4936.4 1984.53  4995.7 1982.85  4996.2 1982.35
  5004.3 1982.85  5090.8 1983.93  5151.0 1992.32  5191.0 1990.47  5271.0 1993.17
  5321.0 1991.12  5371.0 1994.14  5411.0 1992.35  5441.0 1994.98  5530.5 1996.21
  5921.0 2002.64  6031.0 2007.26  6081.0 2012.30  6131.0 2011.39  6307.6 2018.72
#Mann=6,-1,0
  3949.9    0.07       0  4267.1   0.035       0  4699.2    0.07       0
  4995.7    0.07       0  5004.3    0.07       0  5530.5   0.045       0
Bank Sta=4995.7,5004.3
Exp/Cntr=0.3,0.1

Type RM Length L Ch R = 1,1198,961,961,961
BEGIN DESCRIPTION:
Mapping XS 1d248222
END DESCRIPTION:
XS GIS Cut Line= 5
      1394059.47      6911429.52      1394197.49      6912421.68
      1394286.03      6912426.89      1394421.44      6912437.31
      1395619.34      6912450.33
#Sta/Elev= 30
  3925.8 1993.89  4116.1 1991.83  4277.9 1992.67  4388.7 1991.04  4616.8 1993.08
  4799.1 1992.66  4863.2 1989.20  4935.0 1991.34  4950.0 1990.08  4965.1 1985.69
  4985.1 1984.63  5035.2 1985.02  5075.4 1989.79  5085.4 1988.58  5101.1 1982.05
  5101.6 1981.55  5109.7 1982.05  5185.6 1989.66  5365.6 1988.09  5455.6 1992.86
  5495.6 1991.90  5515.6 1994.15  5545.6 1993.25  5585.6 1996.50  5624.0 1996.56
  5745.6 1997.64  5805.6 2001.93  5839.2 2001.08  6065.6 2007.06  6350.0 2019.57
#Mann=7,-1,0
  3925.8    0.07       0  4277.9   0.035       0  4616.8    0.07       0
  5101.1    0.07       0  5109.7    0.07       0  5624.0   0.045       0
  5839.2    0.07       0
Bank Sta=5101.1,5109.7
Exp/Cntr=0.3,0.1

Type RM Length L Ch R = 1,237,0,0,0
BEGIN DESCRIPTION:
Plum Creek Trib4_3 1.0
END DESCRIPTION:
XS GIS Cut Line= 5
      1394016.49      6911348.74      1394198.79      6912580.54
      1394200.09      6912791.62      1394232.64      6913103.98
      1394890.77      6913676.26
#Sta/Elev= 30
  3543.7 1994.64  3815.9 1991.98  4041.5 1992.53  4139.4 1991.29  4178.6 1993.07
  4330.5 1992.43  4462.9 1992.89  4595.8 1989.14  4665.3 1991.11  4876.4 1990.18
  4906.4 1989.28  4956.4 1980.64  5002.1 1977.52  5002.6 1977.02  5010.7 1977.52
  5117.0 1982.87  5221.2 1993.30  5237.7 1994.79  5424.5 1990.32  5559.4 1989.78
  5772.1 1995.41  5814.8 1998.54  5849.9 1997.15  5878.4 1998.88  5886.0 2000.98
  5970.5 2000.85  5999.0 2001.87  6027.5 2005.71  6126.2 2005.16  6186.2 2009.41
#Mann=6,-1,0
  3543.7    0.07       0  4041.5   0.035       0  4330.5    0.07       0
  5002.1    0.07       0  5010.7    0.07       0  5221.2   0.045       0
Bank Sta=5002.1,5010.7
Exp/Cntr=0.3,0.1

Chan Stop Cuts=-1