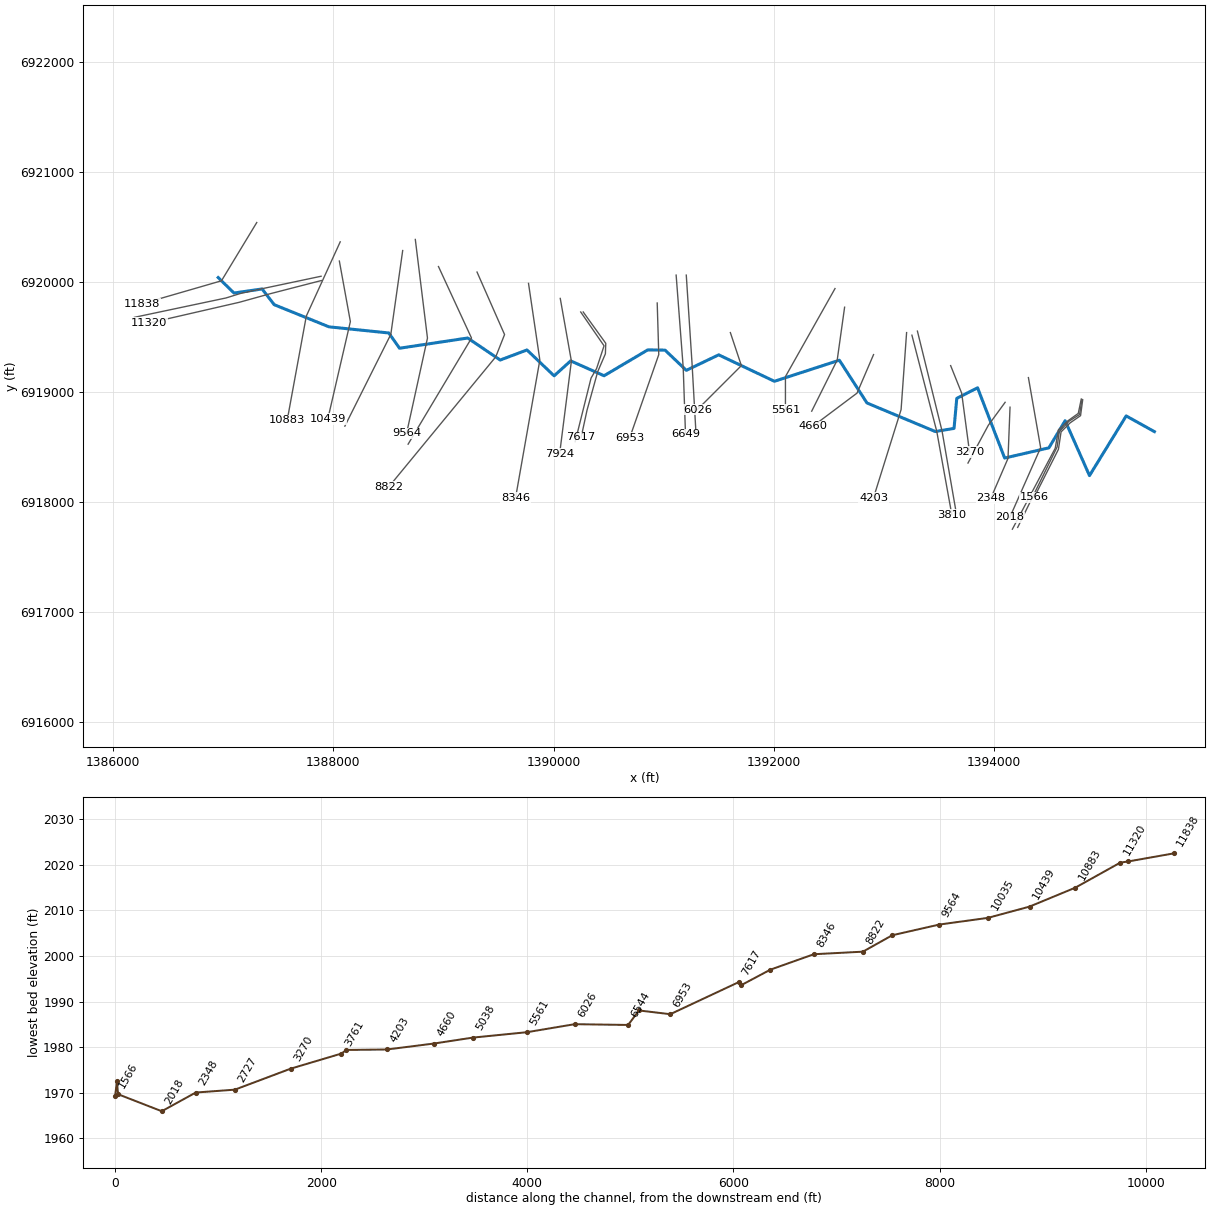
--- Plum Creek Trib5.prj (project) ---

Proj Title=Plum Creek Trib5 Base Level Engineering
Current Plan=p01
Default Exp/Contr=0.3,0.1
English Units
Geom File=g01
Flow File=f01
Plan File=p01
BEGIN DESCRIPTION:
Plum Creek Trib5
END DESCRIPTION:

--- Plum Creek Trib5.p01 (plan) ---

Plan Title=Multiple Run
Short Identifier=Multiple
Geom File=g01
Flow File=f01
Subcritical Flow
K Sum by GR= 0
Std Step Tol= 0.01
Critical Tol= 0.01
Num of Std Step Trials= 20
Max Error Tol= 0.3
Flow Tol Ratio= 0.001
Split Flow NTrial= 30
Split Flow Tol= 0.02
Split Flow Ratio= 0.02
Log Output Level= 0
Friction Slope Method= 1
Unsteady Friction Slope Method= 2
Unsteady Bridges Friction Slope Method= 1
Parabolic Critical Depth
Global Vel Dist=  1 , 1 , 1
Global Log Level= 0
CheckData=True
Encroach Param= -1, 0, 0, 0
BEGIN DESCRIPTION:
Multiple Run
END DESCRIPTION:

--- Plum Creek Trib5.f01 (steady flow) ---

Flow Title=Multiple
Number of Profiles=7
Profile Names=10-year,25-year,50-year,1pct_min,100-year,1pct_plu,500-year
River Rch & RM= Plum Creek Trib5,Reach-1,11838
     290     412     515     320     639    1276     998
River Rch & RM= Plum Creek Trib5,Reach-1,10439
     359     514     647     404     807    1609    1271
River Rch & RM= Plum Creek Trib5,Reach-1,6649
     510     744     945     597    1191    2376    1914
River Rch & RM= Plum Creek Trib5,Reach-1,4203
     521     759     964     608    1213    2420    1946
Boundary for River Rch & Prof#=Plum Creek Trib5,Reach-1,1
Up Type=0
Dn Type=3
Dn Slope=0.005
Boundary for River Rch & Prof#=Plum Creek Trib5,Reach-1,2
Up Type=0
Dn Type=3
Dn Slope=0.005
Boundary for River Rch & Prof#=Plum Creek Trib5,Reach-1,3
Up Type=0
Dn Type=3
Dn Slope=0.005
Boundary for River Rch & Prof#=Plum Creek Trib5,Reach-1,4
Up Type=0
Dn Type=3
Dn Slope=0.005
Boundary for River Rch & Prof#=Plum Creek Trib5,Reach-1,5
Up Type=0
Dn Type=3
Dn Slope=0.005
Boundary for River Rch & Prof#=Plum Creek Trib5,Reach-1,6
Up Type=0
Dn Type=3
Dn Slope=0.005
Boundary for River Rch & Prof#=Plum Creek Trib5,Reach-1,7
Up Type=0
Dn Type=3
Dn Slope=0.005

--- Plum Creek Trib5.g01 (geometry) ---

Geom Title=Existing Conditions

River Reach=Plum Creek Trib5,Reach-1
Reach XY= 30
      1386955.00      6920038.00      1387098.33      6919897.39
      1387353.55      6919934.47      1387463.48      6919791.51
      1387960.93      6919590.23      1388503.72      6919534.47
      1388601.42      6919395.89      1389220.06      6919488.70
      1389515.62      6919288.60      1389758.41      6919380.19
      1390004.79      6919144.98      1390155.00      6919280.90
      1390458.23      6919145.85      1390854.92      6919380.64
      1391011.73      6919378.85      1391205.00      6919195.07
      1391499.07      6919335.77      1392005.00      6919095.56
      1392594.53      6919287.07      1392845.17      6918898.47
      1393465.44      6918639.04      1393635.77      6918667.42
      1393660.51      6918940.44      1393849.31      6919036.13
      1394095.29      6918398.18      1394497.08      6918490.92
      1394644.51      6918737.52      1394865.53      6918238.47
      1395198.67      6918780.66      1395455.00      6918638.00

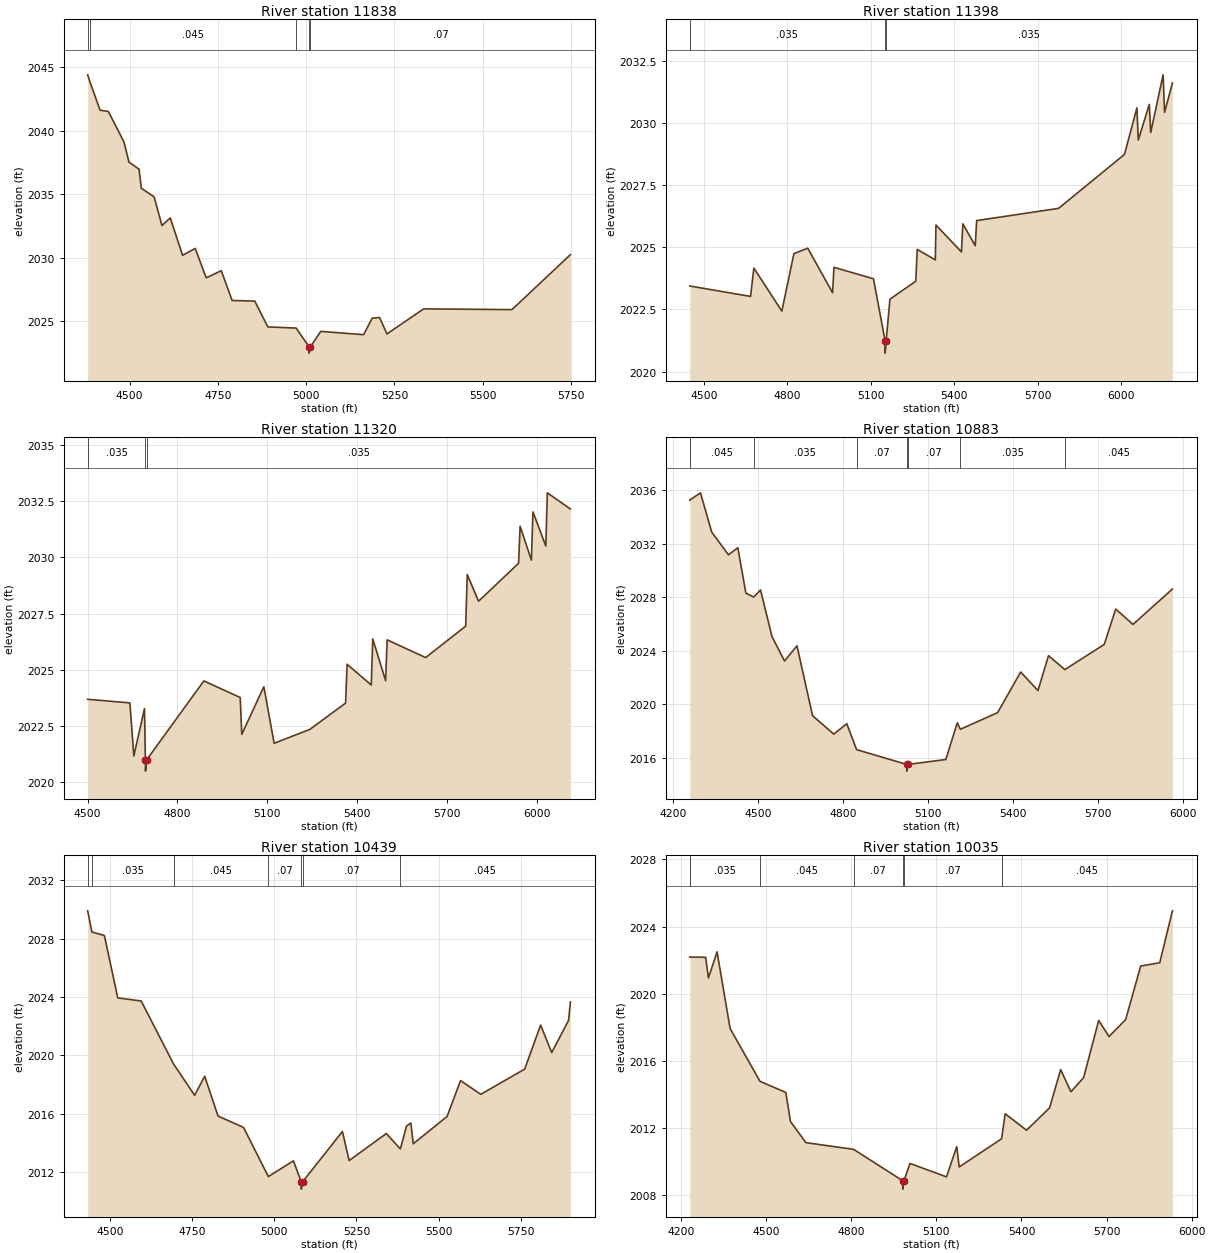
Type RM Length L Ch R = 1,11838,440,440,440
BEGIN DESCRIPTION:
Plum Creek Trib5 21.0
END DESCRIPTION:
XS GIS Cut Line= 3
      1387305.01      6920538.02      1386984.75      6920008.66
      1386266.01      6919800.41
#Sta/Elev= 30
  4381.3 2044.38  4386.9 2043.89  4416.4 2041.60  4439.8 2041.50  4484.1 2039.11
  4498.2 2037.52  4526.8 2036.96  4533.3 2035.46  4569.5 2034.79  4591.7 2032.53
  4615.1 2033.13  4650.1 2030.19  4685.9 2030.73  4716.9 2028.42  4759.6 2028.98
  4790.4 2026.64  4854.6 2026.59  4891.5 2024.56  4971.7 2024.47  5008.1 2023.00
  5008.4 2022.50  5012.1 2023.00  5041.4 2024.21  5162.6 2023.95  5187.1 2025.25
  5208.0 2025.30  5228.8 2024.01  5332.9 2025.98  5582.8 2025.92  5748.3 2030.24
#Mann=5,-1,0
  4381.3   0.035       0  4386.9   0.045       0  4971.7    0.07       0
  5008.1    0.07       0  5012.1    0.07       0
Bank Sta=5008.1,5012.1
Exp/Cntr=0.3,0.1

Type RM Length L Ch R = 1,11398,78,78,78
BEGIN DESCRIPTION:
Mapping XS b9c452b6
END DESCRIPTION:
XS GIS Cut Line= 5
      1387889.18      6920049.95      1387355.37      6919937.11
      1387157.89      6919893.71      1387025.51      6919852.48
      1386194.35      6919676.70
#Sta/Elev= 30
  4448.4 2023.44  4667.3 2023.02  4679.0 2024.16  4779.7 2022.43  4823.1 2024.74
  4872.8 2024.96  4962.1 2023.17  4967.2 2024.19  5109.2 2023.73  5151.0 2021.24
  5151.3 2020.74  5155.0 2021.24  5168.4 2022.91  5261.3 2023.63  5266.6 2024.91
  5331.6 2024.49  5334.0 2025.89  5425.6 2024.81  5430.7 2025.94  5475.3 2025.06
  5480.4 2026.07  5774.9 2026.56  6012.0 2028.73  6056.6 2030.60  6061.7 2029.31
  6101.2 2030.74  6106.3 2029.61  6150.9 2031.93  6156.1 2030.42  6184.4 2031.60
#Mann=3,-1,0
  4448.4   0.035       0  5151.0   0.035       0  5155.0   0.035       0
Bank Sta=5151,5155
Exp/Cntr=0.3,0.1

Type RM Length L Ch R = 1,11320,437,437,437
BEGIN DESCRIPTION:
Mapping XS febfabb6
END DESCRIPTION:
XS GIS Cut Line= 4
      1387891.37      6920010.89      1387420.48      6919889.37
      1387147.04      6919813.41      1386328.35      6919624.99
#Sta/Elev= 30
  4500.5 2023.68  4641.3 2023.52  4654.5 2021.16  4690.0 2023.27  4693.1 2020.98
  4693.4 2020.48  4697.1 2020.98  4888.1 2024.50  5009.3 2023.76  5014.5 2022.12
  5088.2 2024.24  5122.5 2021.72  5241.6 2022.34  5360.8 2023.51  5365.9 2025.24
  5446.4 2024.32  5451.5 2026.37  5494.3 2024.51  5499.5 2026.33  5627.9 2025.54
  5761.5 2026.94  5766.6 2029.24  5804.3 2028.05  5937.9 2029.74  5943.0 2031.39
  5980.7 2029.88  5985.8 2032.03  6028.7 2030.51  6033.8 2032.88  6110.7 2032.16
#Mann=3,-1,0
  4500.5   0.035       0  4693.1   0.035       0  4697.1   0.035       0
Bank Sta=4693.1,4697.1
Exp/Cntr=0.3,0.1

Type RM Length L Ch R = 1,10883,444,444,444
BEGIN DESCRIPTION:
Plum Creek Trib5 19.0
END DESCRIPTION:
XS GIS Cut Line= 3
      1388062.84      6920362.47      1387755.00      6919688.00
      1387581.41      6918741.08
#Sta/Elev= 30
  4258.6 2035.26  4296.5 2035.81  4336.3 2032.87  4395.4 2031.17  4428.4 2031.70
  4457.0 2028.30  4484.6 2028.01  4508.6 2028.54  4549.1 2025.05  4593.3 2023.22
  4637.3 2024.36  4692.2 2019.13  4767.4 2017.75  4813.1 2018.53  4847.6 2016.59
  5024.6 2015.48  5024.8 2014.98  5028.6 2015.48  5162.7 2015.85  5203.3 2018.60
  5214.0 2018.11  5345.7 2019.36  5427.0 2022.40  5488.0 2021.01  5525.2 2023.62
  5583.0 2022.58  5721.8 2024.46  5762.5 2027.11  5823.5 2025.96  5962.7 2028.61
#Mann=7,-1,0
  4258.6   0.045       0  4484.6   0.035       0  4847.6    0.07       0
  5024.6    0.07       0  5028.6    0.07       0  5214.0   0.035       0
  5583.0   0.045       0
Bank Sta=5024.6,5028.6
Exp/Cntr=0.3,0.1

Type RM Length L Ch R = 1,10439,404,404,404
BEGIN DESCRIPTION:
Plum Creek Trib5 18.0
END DESCRIPTION:
XS GIS Cut Line= 3
      1388054.99      6920188.03      1388155.00      6919638.00
      1387950.09      6918752.65
#Sta/Elev= 30
  4432.9 2029.91  4445.7 2028.46  4483.7 2028.22  4524.4 2023.94  4595.6 2023.73
  4694.1 2019.41  4758.2 2017.26  4788.7 2018.57  4829.3 2015.84  4906.8 2015.06
  4982.3 2011.69  5058.6 2012.77  5082.3 2011.33  5082.6 2010.83  5086.3 2011.33
  5207.5 2014.78  5228.0 2012.79  5340.9 2014.64  5383.7 2013.59  5402.5 2015.16
  5415.6 2015.36  5423.0 2013.94  5525.7 2015.81  5566.7 2018.27  5628.3 2017.33
  5761.8 2019.06  5810.2 2022.08  5843.9 2020.19  5895.2 2022.40  5900.7 2023.66
#Mann=7,-1,0
  4432.9   0.045       0  4445.7   0.035       0  4694.1   0.045       0
  4982.3    0.07       0  5082.3    0.07       0  5086.3    0.07       0
  5383.7   0.045       0
Bank Sta=5082.3,5086.3
Exp/Cntr=0.3,0.1

Type RM Length L Ch R = 1,10035,471,471,471
BEGIN DESCRIPTION:
Plum Creek Trib5 17.0
END DESCRIPTION:
XS GIS Cut Line= 3
      1388630.04      6920283.49      1388522.13      6919521.69
      1388105.01      6918688.02
#Sta/Elev= 30
  4230.6 2022.19  4286.6 2022.17  4296.7 2020.94  4327.0 2022.50  4373.0 2017.93
  4478.4 2014.78  4569.4 2014.12  4586.0 2012.38  4640.1 2011.13  4808.4 2010.73
  4981.5 2008.86  4981.8 2008.36  4985.6 2008.86  5007.2 2009.89  5135.8 2009.09
  5171.9 2010.89  5180.5 2009.68  5330.0 2011.36  5342.6 2012.85  5417.9 2011.87
  5499.1 2013.20  5538.2 2015.48  5574.4 2014.16  5619.1 2015.00  5672.3 2018.41
  5708.6 2017.45  5767.3 2018.46  5820.4 2021.65  5887.5 2021.85  5932.2 2024.94
#Mann=6,-1,0
  4230.6   0.035       0  4478.4   0.045       0  4808.4    0.07       0
  4981.5    0.07       0  4985.6    0.07       0  5330.0   0.045       0
Bank Sta=4981.5,4985.6
Exp/Cntr=0.3,0.1

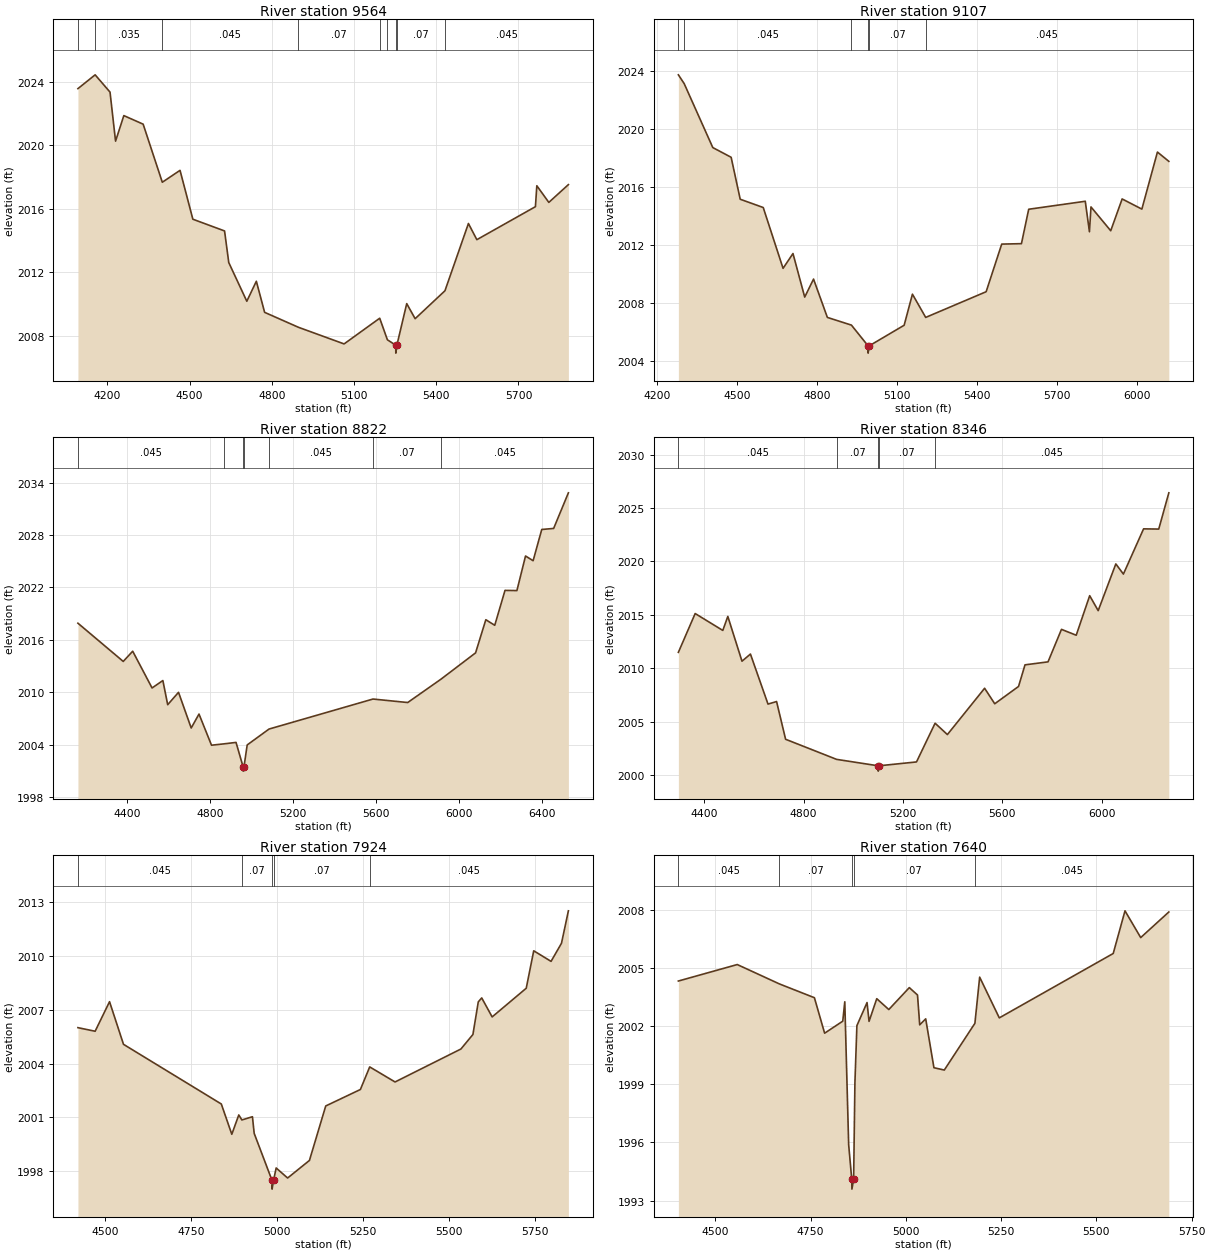
Type RM Length L Ch R = 1,9564,457,457,457
BEGIN DESCRIPTION:
Plum Creek Trib5 16.0
END DESCRIPTION:
XS GIS Cut Line= 3
      1388744.62      6920384.24      1388855.00      6919488.00
      1388665.06      6918621.69
#Sta/Elev= 30
  4092.4 2023.57  4155.2 2024.44  4209.5 2023.35  4229.7 2020.26  4259.9 2021.87
  4330.4 2021.33  4400.3 2017.67  4465.0 2018.42  4511.8 2015.34  4627.5 2014.60
  4642.8 2012.61  4708.7 2010.17  4743.5 2011.43  4773.7 2009.47  4896.9 2008.53
  5063.7 2007.48  5193.7 2009.10  5221.8 2007.74  5252.2 2007.40  5252.5 2006.90
  5256.4 2007.40  5292.3 2010.02  5323.0 2009.07  5431.8 2010.83  5517.5 2015.07
  5548.2 2014.05  5762.0 2016.13  5767.1 2017.45  5810.9 2016.40  5882.3 2017.52
#Mann=9,-1,0
  4092.4   0.045       0  4155.2   0.035       0  4400.3   0.045       0
  4896.9    0.07       0  5193.7   0.045       0  5221.8    0.07       0
  5252.2    0.07       0  5256.4    0.07       0  5431.8   0.045       0
Bank Sta=5252.2,5256.4
Exp/Cntr=0.3,0.1

Type RM Length L Ch R = 1,9107,285,285,285
BEGIN DESCRIPTION:
Plum Creek Trib5 15.0
END DESCRIPTION:
XS GIS Cut Line= 3
      1388954.99      6920138.03      1389255.00      6919488.00
      1388679.34      6918524.26
#Sta/Elev= 30
  4280.0 2023.72  4301.9 2023.11  4409.0 2018.71  4477.8 2018.04  4511.8 2015.15
  4598.1 2014.58  4672.4 2010.39  4709.6 2011.41  4753.6 2008.41  4786.7 2009.65
  4838.5 2007.01  4928.7 2006.48  4991.1 2005.05  4991.3 2004.55  4995.3 2005.05
  5126.3 2006.47  5157.4 2008.61  5207.1 2007.01  5433.7 2008.78  5492.1 2012.06
  5566.0 2012.09  5593.2 2014.46  5805.3 2015.01  5820.9 2012.91  5826.7 2014.62
  5900.7 2012.98  5943.5 2015.17  6017.4 2014.47  6075.8 2018.40  6118.5 2017.76
#Mann=6,-1,0
  4280.0   0.035       0  4301.9   0.045       0  4928.7    0.07       0
  4991.1    0.07       0  4995.3    0.07       0  5207.1   0.045       0
Bank Sta=4991.1,4995.3
Exp/Cntr=0.3,0.1

Type RM Length L Ch R = 1,8822,476,476,476
BEGIN DESCRIPTION:
Plum Creek Trib5 14.0
END DESCRIPTION:
XS GIS Cut Line= 4
      1389305.01      6920087.97      1389554.96      6919520.22
      1389474.84      6919317.41      1388504.97      6918137.96
#Sta/Elev= 30
  4161.6 2017.90  4380.1 2013.52  4425.7 2014.69  4519.1 2010.48  4571.2 2011.33
  4594.5 2008.56  4646.7 2009.98  4707.9 2005.89  4745.5 2007.49  4805.8 2003.92
  4864.0 2004.07  4924.1 2004.24  4958.1 2001.45  4958.4 2000.95  4962.4 2001.45
  4977.9 2003.95  5083.1 2005.77  5584.6 2009.21  5752.1 2008.81  5912.7 2011.49
  6079.3 2014.50  6128.8 2018.30  6171.8 2017.66  6221.3 2021.66  6278.7 2021.64
  6320.3 2025.60  6356.9 2025.06  6398.5 2028.64  6455.9 2028.76  6527.0 2032.84
#Mann=7,-1,0
  4161.6   0.045       0  4864.0    0.07       0  4958.1    0.07       0
  4962.4    0.07       0  5083.1   0.045       0  5584.6    0.07       0
  5912.7   0.045       0
Bank Sta=4958.1,4962.4
Exp/Cntr=0.3,0.1

Type RM Length L Ch R = 1,8346,422,422,422
BEGIN DESCRIPTION:
Plum Creek Trib5 13.0
END DESCRIPTION:
XS GIS Cut Line= 3
      1389772.41      6919984.88      1389875.23      6919288.43
      1389655.00      6918037.97
#Sta/Elev= 30
  4296.0 2011.50  4363.6 2015.13  4474.8 2013.55  4495.0 2014.86  4552.0 2010.67
  4586.0 2011.34  4656.7 2006.66  4691.2 2006.90  4727.5 2003.37  4932.7 2001.49
  5099.8 2000.89  5100.1 2000.39  5104.1 2000.89  5254.3 2001.25  5329.1 2004.87
  5378.6 2003.81  5528.4 2008.14  5569.1 2006.69  5664.9 2008.31  5690.9 2010.33
  5783.5 2010.61  5837.7 2013.65  5897.0 2013.10  5951.2 2016.80  5985.4 2015.40
  6056.4 2019.77  6086.9 2018.82  6168.1 2023.05  6229.1 2023.03  6269.7 2026.42
#Mann=5,-1,0
  4296.0   0.045       0  4932.7    0.07       0  5099.8    0.07       0
  5104.1    0.07       0  5329.1   0.045       0
Bank Sta=5099.8,5104.1
Exp/Cntr=0.3,0.1

Type RM Length L Ch R = 1,7924,284,284,284
BEGIN DESCRIPTION:
Plum Creek Trib5 12.0
END DESCRIPTION:
XS GIS Cut Line= 3
      1390060.59      6919848.51      1390161.67      6919279.01
      1390055.01      6918438.05
#Sta/Elev= 30
  4421.6 2006.01  4471.6 2005.81  4513.5 2007.46  4554.1 2005.08  4838.5 2001.75
  4869.0 2000.06  4889.3 2001.14  4898.3 2000.86  4929.0 2001.04  4934.1 2000.11
  4985.7 1997.50  4986.1 1997.00  4990.5 1997.50  4998.0 1998.18  5031.3 1997.62
  5094.7 1998.60  5142.1 2001.64  5242.9 2002.56  5270.0 2003.82  5343.7 2002.98
  5535.3 2004.82  5570.1 2005.63  5585.7 2007.45  5595.7 2007.67  5626.0 2006.61
  5725.1 2008.21  5746.9 2010.30  5797.3 2009.71  5827.6 2010.72  5847.7 2012.53
#Mann=5,-1,0
  4421.6   0.045       0  4898.3    0.07       0  4985.7    0.07       0
  4990.5    0.07       0  5270.0   0.045       0
Bank Sta=4985.7,4990.5
Exp/Cntr=0.3,0.1

Type RM Length L Ch R = 1,7640,23,23,23
BEGIN DESCRIPTION:
Mapping XS 0b31d00d
END DESCRIPTION:
XS GIS Cut Line= 5
      1390246.34      6919725.23      1390458.17      6919417.91
      1390390.46      6919211.31      1390340.11      6919124.50
      1390196.02      6918546.41
#Sta/Elev= 30
  4403.3 2004.32  4557.8 2005.17  4668.5 2004.17  4760.2 2003.46  4787.0 2001.63
  4834.6 2002.25  4839.9 2003.25  4850.1 1995.88  4858.2 1994.09  4858.6 1993.59
  4863.1 1994.09  4866.5 1999.08  4871.7 2002.02  4898.3 2003.21  4903.6 2002.24
  4923.8 2003.41  4955.4 2002.85  5009.2 2003.98  5030.7 2003.60  5036.5 2002.06
  5052.2 2002.37  5073.8 1999.85  5101.0 1999.73  5181.3 2002.14  5193.8 2004.52
  5245.3 2002.42  5544.2 2005.74  5575.1 2007.94  5616.3 2006.56  5690.1 2007.88
#Mann=5,-1,0
  4403.3   0.045       0  4668.5    0.07       0  4858.2    0.07       0
  4863.1    0.07       0  5181.3   0.045       0
Bank Sta=4858.2,4863.1
Exp/Cntr=0.3,0.1

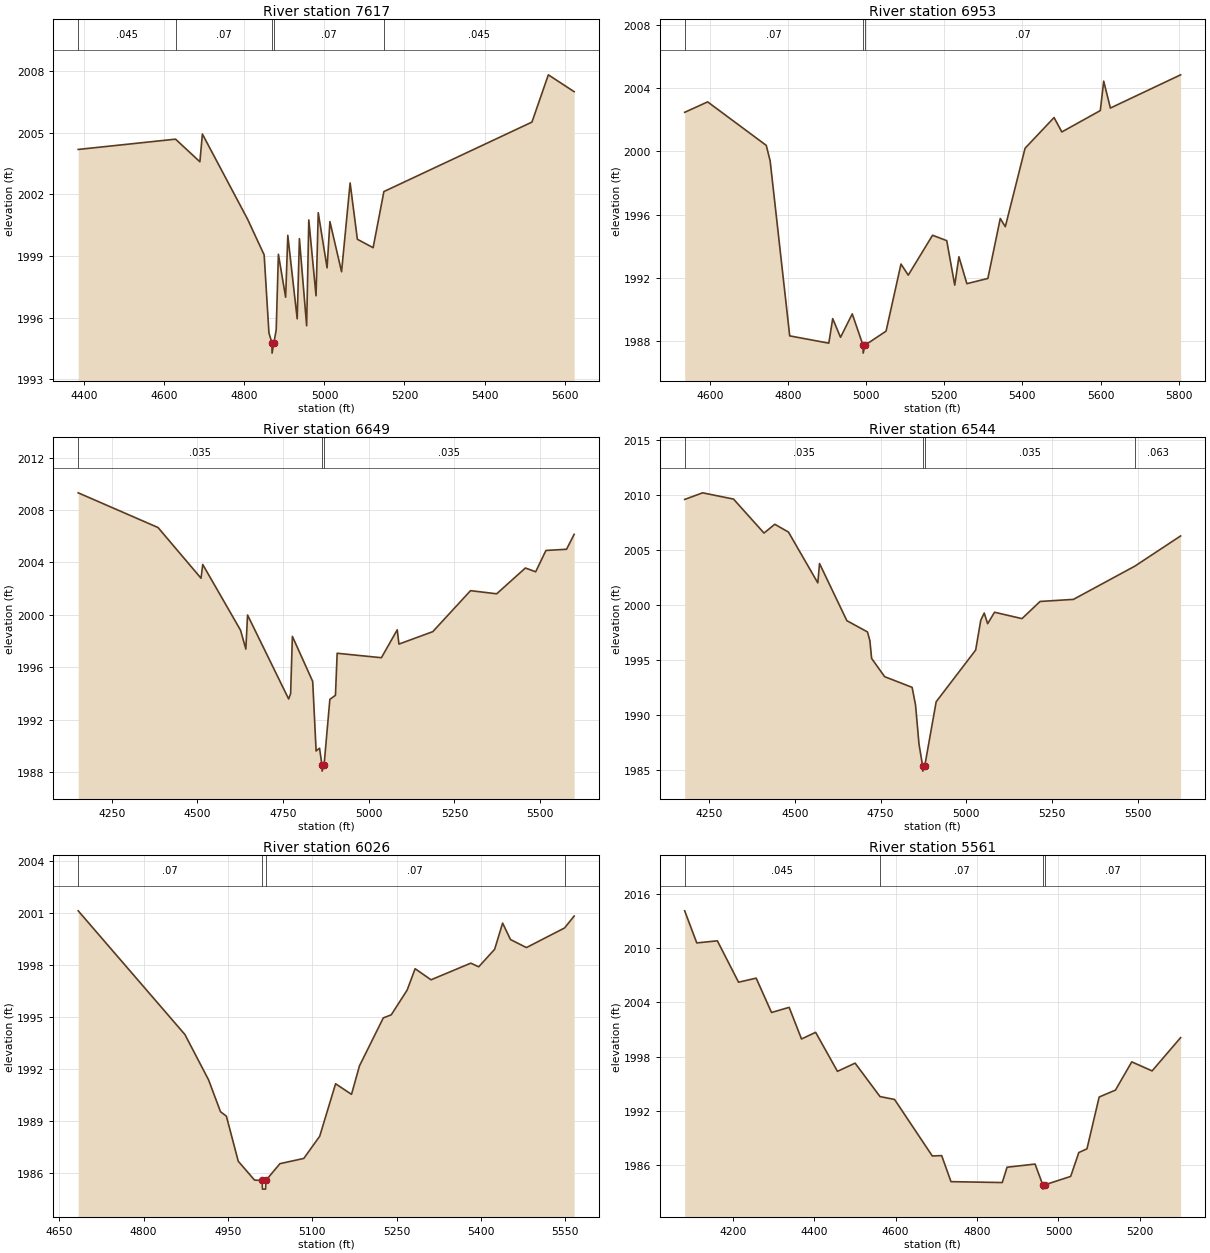
Type RM Length L Ch R = 1,7617,664,664,664
BEGIN DESCRIPTION:
Mapping XS 38271cb0
END DESCRIPTION:
XS GIS Cut Line= 6
      1390268.91      6919725.22      1390473.79      6919440.47
      1390470.32      6919344.99      1390400.88      6919183.53
      1390303.65      6918832.84      1390249.91      6918584.92
#Sta/Elev= 30
  4384.4 2004.18  4627.7 2004.68  4688.6 2003.58  4694.8 2004.93  4807.7 2000.79
  4849.2 1999.05  4861.2 1995.25  4868.6 1994.77  4869.0 1994.27  4873.5 1994.77
  4879.3 1995.40  4884.8 1999.08  4902.9 1996.99  4908.3 2000.00  4931.8 1995.94
  4937.3 1999.84  4955.4 1995.60  4960.8 2000.75  4978.9 1997.06  4984.4 2001.10
  5006.5 1998.42  5013.6 2000.67  5042.7 1998.23  5064.1 2002.55  5082.2 1999.81
  5121.6 1999.40  5148.5 2002.13  5518.6 2005.51  5559.6 2007.81  5624.1 2006.99
#Mann=5,-1,0
  4384.4   0.045       0  4627.7    0.07       0  4868.6    0.07       0
  4873.5    0.07       0  5148.5   0.045       0
Bank Sta=4868.6,4873.5
Exp/Cntr=0.3,0.1

Type RM Length L Ch R = 1,6953,304,304,304
BEGIN DESCRIPTION:
Plum Creek Trib5 10.0
END DESCRIPTION:
XS GIS Cut Line= 3
      1390940.81      6919806.82      1390955.00      6919338.00
      1390691.14      6918582.06
#Sta/Elev= 30
  4535.4 2002.46  4594.2 2003.12  4744.3 2000.37  4754.3 1999.38  4804.3 1988.33
  4904.4 1987.87  4914.4 1989.42  4934.4 1988.24  4964.4 1989.72  4992.0 1987.74
  4992.4 1987.24  4996.9 1987.74  5051.0 1988.63  5089.2 1992.87  5107.8 1992.17
  5170.0 1994.69  5206.3 1994.35  5226.8 1991.54  5237.5 1993.33  5257.9 1991.63
  5311.6 1991.96  5343.4 1995.75  5356.3 1995.23  5406.9 2000.19  5481.1 2002.13
  5501.0 2001.22  5599.5 2002.57  5608.2 2004.43  5625.3 2002.73  5805.1 2004.83
#Mann=3,-1,0
  4535.4    0.07       0  4992.0    0.07       0  4996.9    0.07       0
Bank Sta=4992,4996.9
Exp/Cntr=0.3,0.1

Type RM Length L Ch R = 1,6649,105,105,105
BEGIN DESCRIPTION:
Mapping XS f026eadf
END DESCRIPTION:
XS GIS Cut Line= 3
      1391112.68      6920060.28      1391176.92      6919219.99
      1391197.75      6918615.79
#Sta/Elev= 30
  4152.2 2009.31  4385.2 2006.66  4510.6 2002.79  4515.6 2003.84  4625.9 1998.82
  4641.4 1997.38  4646.4 1999.98  4766.3 1993.57  4772.1 1993.98  4777.2 1998.35
  4836.5 1994.91  4846.5 1989.60  4856.5 1989.81  4863.4 1988.56  4863.9 1988.06
  4869.8 1988.56  4886.6 1993.54  4902.9 1993.85  4907.9 1997.06  5037.0 1996.72
  5083.2 1998.85  5088.2 1997.76  5187.0 1998.71  5297.1 2001.84  5373.4 2001.60
  5457.2 2003.57  5487.2 2003.28  5517.2 2004.91  5577.3 2005.00  5599.5 2006.14
#Mann=3,-1,0
  4152.2   0.035       0  4863.4   0.035       0  4869.8   0.035       0
Bank Sta=4863.4,4869.8
Exp/Cntr=0.3,0.1

Type RM Length L Ch R = 1,6544,518,518,518
BEGIN DESCRIPTION:
Mapping XS f8ff3313
END DESCRIPTION:
XS GIS Cut Line= 3
      1391204.69      6920060.30      1391256.78      6919261.66
      1391293.24      6918615.82
#Sta/Elev= 30
  4178.5 2009.59  4230.9 2010.19  4321.1 2009.62  4410.0 2006.53  4441.4 2007.33
  4481.4 2006.62  4567.0 2002.00  4572.0 2003.76  4651.8 1998.56  4711.9 1997.54
  4719.0 1996.74  4724.0 1995.13  4762.0 1993.47  4842.2 1992.50  4852.2 1990.89
  4862.2 1987.36  4872.7 1985.38  4873.2 1984.88  4879.2 1985.38  4912.4 1991.19
  5027.6 1995.89  5042.6 1998.61  5052.6 1999.26  5062.6 1998.29  5082.7 1999.33
  5162.8 1998.75  5215.6 2000.31  5313.0 2000.50  5492.0 2003.52  5625.7 2006.27
#Mann=4,-1,0
  4178.5   0.035       0  4872.7   0.035       0  4879.2   0.035       0
  5492.0   0.063       0
Bank Sta=4872.7,4879.2
Exp/Cntr=0.3,0.1

Type RM Length L Ch R = 1,6026,465,465,465
BEGIN DESCRIPTION:
Plum Creek Trib5 8.0
END DESCRIPTION:
XS GIS Cut Line= 3
      1391604.99      6919538.02      1391705.00      6919238.00
      1391305.02      6918838.02
#Sta/Elev= 30
  4683.8 2001.11  4873.6 1993.97  4915.7 1991.35  4936.8 1989.52  4947.3 1989.26
  4968.4 1986.66  4997.4 1985.57  5010.9 1985.55  5011.4 1985.05  5017.0 1985.05
  5017.5 1985.55  5042.5 1986.52  5084.9 1986.82  5113.2 1988.10  5141.5 1991.13
  5169.8 1990.52  5183.9 1992.16  5226.3 1994.93  5240.5 1995.11  5268.8 1996.54
  5282.9 1997.77  5311.2 1997.13  5381.9 1998.09  5396.0 1997.88  5424.3 1998.89
  5438.5 2000.40  5452.6 1999.45  5480.9 1998.99  5548.6 2000.12  5565.7 2000.81
#Mann=4,-1,0
  4683.8    0.07       0  5010.9    0.07       0  5017.5    0.07       0
  5548.6   0.035       0
Bank Sta=5010.9,5017.5
Exp/Cntr=0.3,0.1

Type RM Length L Ch R = 1,5561,523,523,523
BEGIN DESCRIPTION:
Plum Creek Trib5 7.0
END DESCRIPTION:
XS GIS Cut Line= 3
      1392555.02      6919938.03      1392105.00      6919138.00
      1392105.00      6918838.01
#Sta/Elev= 30
  4082.0 2014.17  4111.7 2010.61  4162.3 2010.84  4214.3 2006.25  4257.6 2006.70
  4295.3 2002.89  4338.6 2003.46  4368.9 1999.95  4403.6 2000.69  4457.2 1996.36
  4500.5 1997.27  4561.7 1993.56  4597.4 1993.24  4690.1 1986.97  4713.1 1987.01
  4736.0 1984.12  4861.9 1984.02  4873.7 1985.72  4942.5 1986.07  4961.2 1983.79
  4961.7 1983.29  4967.8 1983.79  5029.9 1984.70  5049.9 1987.35  5069.9 1987.76
  5099.9 1993.51  5139.9 1994.28  5179.9 1997.41  5229.9 1996.41  5299.9 2000.10
#Mann=4,-1,0
  4082.0   0.045       0  4561.7    0.07       0  4961.2    0.07       0
  4967.8    0.07       0
Bank Sta=4961.2,4967.8
Exp/Cntr=0.3,0.1

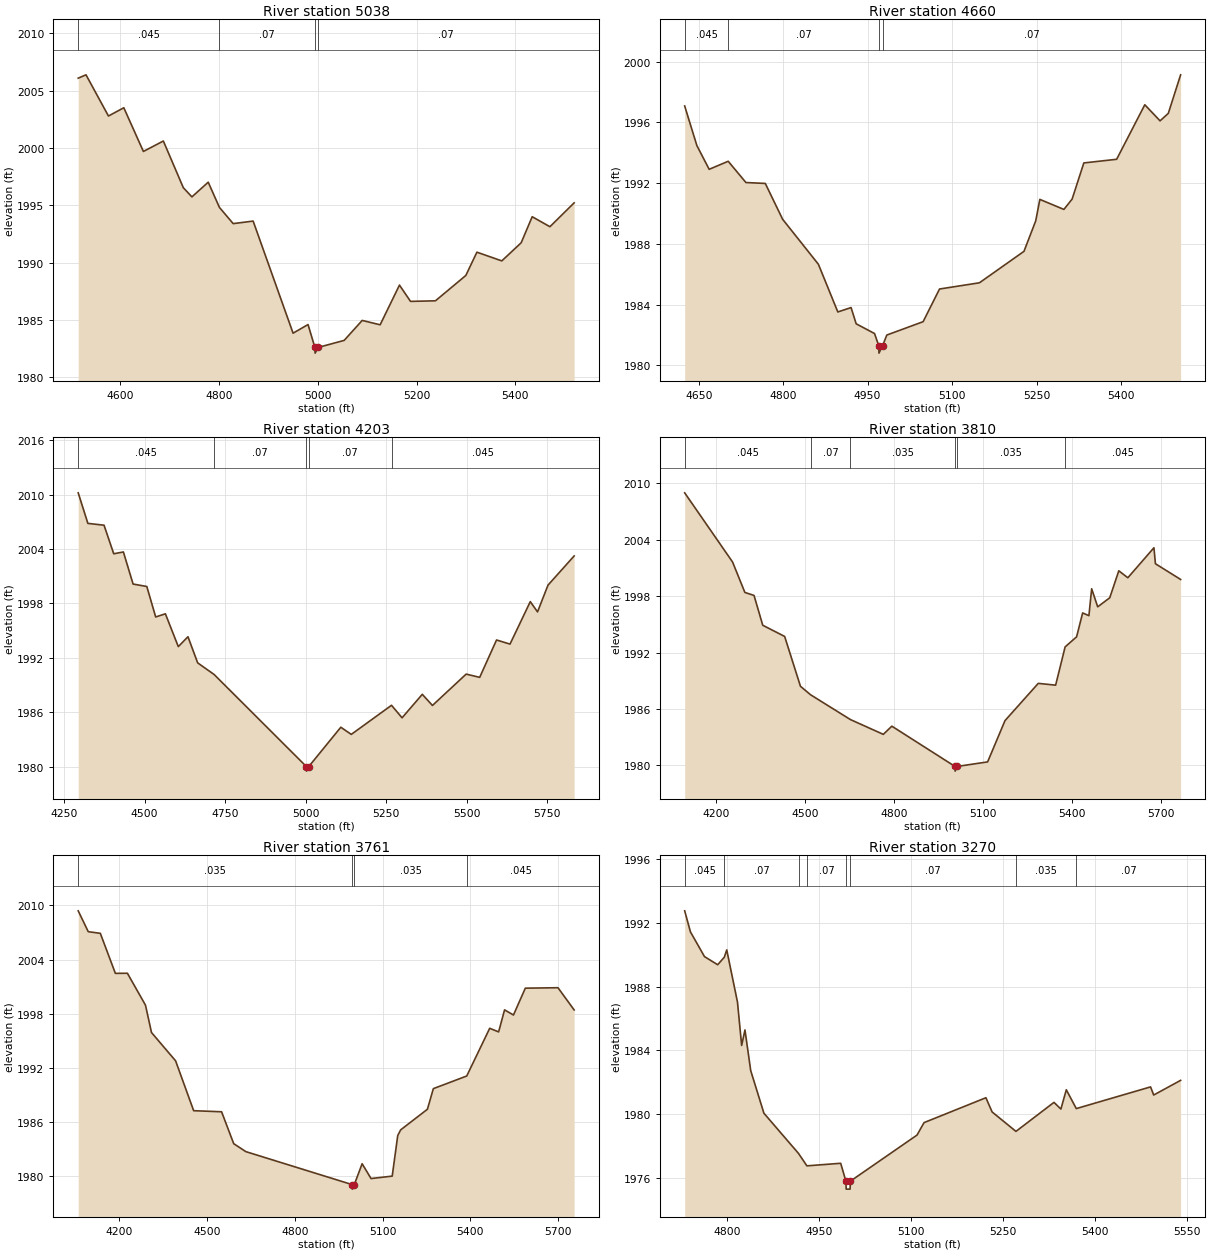
Type RM Length L Ch R = 1,5038,378,378,378
BEGIN DESCRIPTION:
Plum Creek Trib5 6.0
END DESCRIPTION:
XS GIS Cut Line= 3
      1392642.20      6919768.60      1392575.08      6919288.67
      1392343.59      6918824.16
#Sta/Elev= 30
  4515.4 2006.08  4531.2 2006.37  4576.6 2002.78  4607.7 2003.50  4647.3 1999.69
  4687.7 2000.60  4728.1 1996.53  4745.5 1995.73  4778.5 1997.01  4801.2 1994.81
  4829.0 1993.40  4869.4 1993.62  4950.2 1983.85  4980.5 1984.60  4994.3 1982.61
  4994.8 1982.11  5001.3 1982.61  5053.6 1983.22  5090.1 1984.96  5126.4 1984.58
  5165.5 1988.04  5187.9 1986.62  5238.3 1986.67  5299.8 1988.88  5322.2 1990.91
  5372.6 1990.15  5411.8 1991.73  5434.1 1994.00  5470.0 1993.13  5519.0 1995.21
#Mann=4,-1,0
  4515.4   0.045       0  4801.2    0.07       0  4994.3    0.07       0
  5001.3    0.07       0
Bank Sta=4994.3,5001.3
Exp/Cntr=0.3,0.1

Type RM Length L Ch R = 1,4660,457,457,457
BEGIN DESCRIPTION:
Plum Creek Trib5 5.0
END DESCRIPTION:
XS GIS Cut Line= 3
      1392904.99      6919337.98      1392755.00      6918988.00
      1392354.97      6918687.98
#Sta/Elev= 30
  4625.1 1997.08  4646.8 1994.47  4668.6 1992.91  4702.4 1993.44  4733.9 1992.04
  4768.3 1991.98  4799.1 1989.62  4862.6 1986.66  4897.1 1983.52  4920.6 1983.81
  4929.7 1982.74  4962.3 1982.10  4969.7 1981.31  4970.2 1980.81  4976.7 1981.31
  4984.1 1982.00  5048.6 1982.88  5077.7 1985.03  5148.6 1985.44  5227.7 1987.51
  5248.6 1989.52  5255.9 1990.93  5298.6 1990.27  5313.2 1990.95  5334.0 1993.33
  5392.3 1993.57  5442.3 1997.16  5469.4 1996.10  5484.0 1996.59  5505.9 1999.13
#Mann=4,-1,0
  4625.1   0.045       0  4702.4    0.07       0  4969.7    0.07       0
  4976.7    0.07       0
Bank Sta=4969.7,4976.7
Exp/Cntr=0.3,0.1

Type RM Length L Ch R = 1,4203,393,393,393
BEGIN DESCRIPTION:
Plum Creek Trib5 4.0
END DESCRIPTION:
XS GIS Cut Line= 3
      1393205.00      6919537.97      1393155.00      6918838.00
      1392905.00      6918038.01
#Sta/Elev= 30
  4293.7 2010.19  4323.7 2006.82  4373.9 2006.62  4404.0 2003.47  4434.0 2003.67
  4464.1 2000.13  4506.7 1999.86  4534.3 1996.50  4564.4 1996.85  4604.5 1993.23
  4634.5 1994.32  4664.6 1991.44  4715.9 1990.15  5002.3 1980.00  5002.8 1979.50
  5009.5 1980.00  5109.1 1984.34  5141.6 1983.55  5266.5 1986.76  5299.3 1985.38
  5362.1 1987.97  5393.6 1986.74  5498.3 1990.20  5540.3 1989.84  5592.6 1993.96
  5634.5 1993.51  5697.4 1998.19  5719.9 1997.06  5752.4 2000.01  5833.6 2003.23
#Mann=5,-1,0
  4293.7   0.045       0  4715.9    0.07       0  5002.3    0.07       0
  5009.5    0.07       0  5266.5   0.045       0
Bank Sta=5002.3,5009.5
Exp/Cntr=0.3,0.1

Type RM Length L Ch R = 1,3810,49,49,49
BEGIN DESCRIPTION:
Mapping XS 5c451a00
END DESCRIPTION:
XS GIS Cut Line= 3
      1393253.32      6919514.52      1393479.01      6918639.97
      1393615.69      6917882.81
#Sta/Elev= 30
  4094.5 2008.99  4256.1 2001.63  4297.5 1998.40  4328.4 1998.08  4357.8 1994.91
  4431.7 1993.72  4485.0 1988.42  4519.1 1987.52  4653.6 1984.88  4764.4 1983.31
  4793.2 1984.18  5006.2 1979.90  5006.7 1979.40  5013.5 1979.90  5116.2 1980.38
  5174.8 1984.77  5287.0 1988.73  5345.6 1988.54  5377.6 1992.61  5416.3 1993.68
  5436.7 1996.22  5457.8 1995.93  5467.1 1998.79  5487.5 1996.87  5528.1 1997.83
  5558.6 2000.70  5589.1 1999.96  5677.1 2003.15  5682.2 2001.45  5767.1 1999.78
#Mann=6,-1,0
  4094.5   0.045       0  4519.1    0.07       0  4653.6   0.035       0
  5006.2   0.035       0  5013.5   0.035       0  5377.6   0.045       0
Bank Sta=5006.2,5013.5
Exp/Cntr=0.3,0.1

Type RM Length L Ch R = 1,3761,491,491,491
BEGIN DESCRIPTION:
Mapping XS 1559b007
END DESCRIPTION:
XS GIS Cut Line= 3
      1393303.23      6919551.43      1393526.75      6918644.31
      1393656.96      6917893.47
#Sta/Elev= 30
  4058.9 2009.40  4093.3 2007.09  4134.5 2006.91  4186.0 2002.48  4227.2 2002.49
  4289.0 1998.96  4309.6 1995.93  4392.0 1992.80  4453.8 1987.28  4549.3 1987.16
  4590.8 1983.63  4632.3 1982.75  4995.9 1979.10  4996.4 1978.60  5003.2 1979.10
  5030.0 1981.41  5060.5 1979.77  5132.9 1980.04  5151.8 1984.53  5161.9 1985.16
  5253.3 1987.44  5273.6 1989.72  5387.8 1991.12  5466.4 1996.40  5496.9 1996.00
  5517.2 1998.44  5547.6 1997.87  5588.2 2000.84  5699.9 2000.89  5755.2 1998.43
#Mann=4,-1,0
  4058.9   0.035       0  4995.9   0.035       0  5003.2   0.035       0
  5387.8   0.045       0
Bank Sta=4995.9,5003.2
Exp/Cntr=0.3,0.1

Type RM Length L Ch R = 1,3270,543,543,543
BEGIN DESCRIPTION:
Plum Creek Trib5 2.0
END DESCRIPTION:
XS GIS Cut Line= 3
      1393605.01      6919237.98      1393705.00      6918988.00
      1393776.31      6918453.27
#Sta/Elev= 30
  4731.3 1992.75  4740.7 1991.43  4763.6 1989.88  4785.1 1989.37  4795.9 1989.84
  4799.9 1990.30  4817.4 1987.03  4824.2 1984.31  4829.6 1985.28  4839.0 1982.73
  4860.5 1980.06  4916.9 1977.54  4930.6 1976.76  4985.7 1976.92  4994.2 1975.80
  4994.7 1975.30  5001.0 1975.30  5001.5 1975.80  5110.2 1978.69  5121.6 1979.47
  5222.5 1981.03  5232.6 1980.14  5271.5 1978.92  5333.5 1980.74  5344.8 1980.32
  5353.6 1981.53  5369.9 1980.35  5491.0 1981.71  5496.1 1981.20  5540.0 1982.12
#Mann=8,-1,0
  4731.3   0.045       0  4795.9    0.07       0  4916.9   0.045       0
  4930.6    0.07       0  4994.2    0.07       0  5001.5    0.07       0
  5271.5   0.035       0  5369.9    0.07       0
Bank Sta=4994.2,5001.5
Exp/Cntr=0.3,0.1

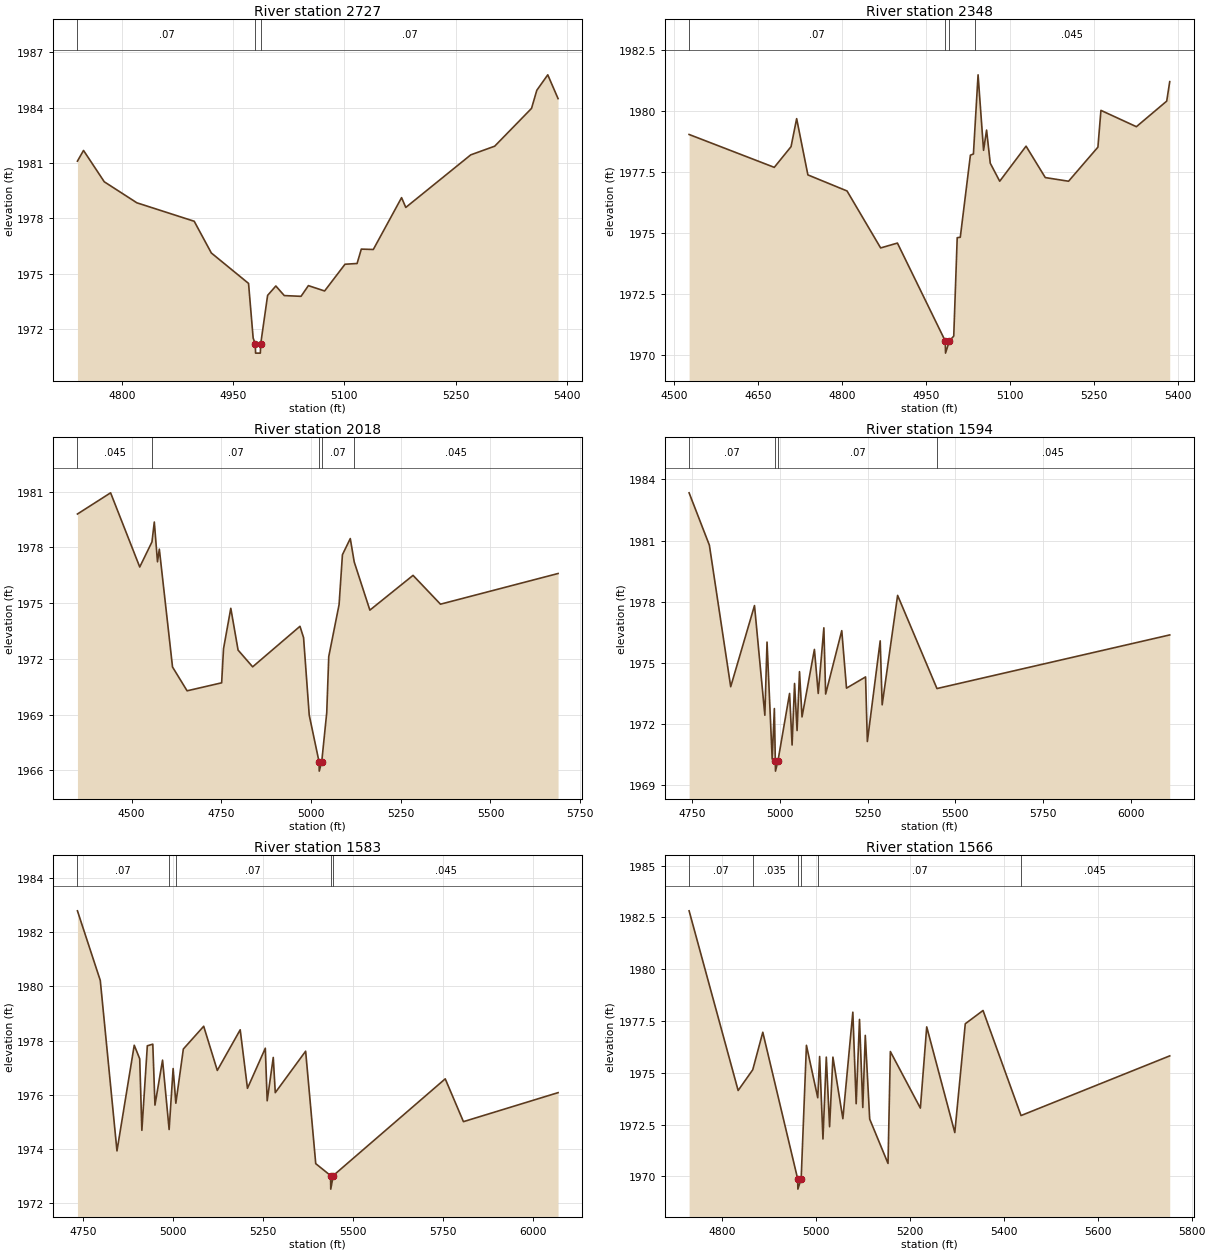
Type RM Length L Ch R = 1,2727,379,379,379
BEGIN DESCRIPTION:
Mapping XS 8be61c95
END DESCRIPTION:
XS GIS Cut Line= 3
      1394099.64      6918904.64      1393946.67      6918695.25
      1393762.38      6918352.69
#Sta/Elev= 30
  4740.0 1981.10  4748.2 1981.68  4776.2 1979.98  4820.2 1978.84  4897.5 1977.84
  4920.6 1976.12  4970.8 1974.47  4977.0 1971.51  4979.8 1971.19  4980.3 1970.69
  4986.7 1970.69  4987.2 1971.19  4996.5 1973.82  5007.6 1974.33  5019.0 1973.81
  5041.6 1973.77  5051.5 1974.35  5073.4 1974.06  5100.9 1975.51  5117.2 1975.55
  5122.9 1976.33  5139.1 1976.31  5177.2 1979.12  5182.9 1978.59  5270.5 1981.44
  5302.8 1981.91  5352.5 1983.96  5359.6 1984.94  5374.4 1985.78  5388.3 1984.49
#Mann=3,-1,0
  4740.0    0.07       0  4979.8    0.07       0  4987.2    0.07       0
Bank Sta=4979.8,4987.2
Exp/Cntr=0.3,0.1

Type RM Length L Ch R = 1,2348,330,330,330
BEGIN DESCRIPTION:
Mapping XS f3d6bdcd
END DESCRIPTION:
XS GIS Cut Line= 3
      1394144.15      6918860.19      1394125.70      6918394.68
      1393969.90      6918033.31
#Sta/Elev= 30
  4526.6 1979.04  4678.9 1977.69  4708.9 1978.54  4718.9 1979.69  4739.0 1977.38
  4809.0 1976.72  4869.1 1974.38  4899.1 1974.58  4984.6 1970.56  4985.1 1970.06
  4992.0 1970.56  4999.8 1970.76  5006.0 1974.80  5011.5 1974.82  5029.6 1978.19
  5035.0 1978.24  5037.9 1979.38  5043.3 1981.49  5053.1 1978.39  5058.5 1979.22
  5065.1 1977.86  5082.0 1977.12  5129.1 1978.56  5163.5 1977.27  5205.1 1977.12
  5257.6 1978.52  5263.0 1980.03  5326.4 1979.36  5380.6 1980.41  5386.0 1981.21
#Mann=4,-1,0
  4526.6    0.07       0  4984.6    0.07       0  4992.0    0.07       0
  5037.9   0.045       0
Bank Sta=4984.6,4992
Exp/Cntr=0.3,0.1

Type RM Length L Ch R = 1,2018,424,424,424
BEGIN DESCRIPTION:
Mapping XS f64aa738
END DESCRIPTION:
XS GIS Cut Line= 3
      1394311.09      6919129.05      1394421.93      6918492.34
      1394141.85      6917858.23
#Sta/Elev= 30
  4349.0 1979.79  4441.4 1980.93  4522.6 1976.94  4556.7 1978.29  4563.2 1979.36
  4572.1 1977.22  4577.2 1977.90  4614.0 1971.56  4654.6 1970.28  4750.9 1970.71
  4756.1 1972.54  4776.4 1974.72  4796.7 1972.47  4837.3 1971.57  4969.2 1973.75
  4979.2 1973.14  4995.0 1968.97  5022.4 1966.46  5022.9 1965.96  5029.8 1966.46
  5043.8 1969.11  5049.4 1972.12  5078.2 1974.92  5087.5 1977.60  5109.4 1978.47
  5120.4 1977.21  5164.0 1974.62  5284.3 1976.49  5360.8 1974.94  5688.5 1976.59
#Mann=5,-1,0
  4349.0   0.045       0  4556.7    0.07       0  5022.4    0.07       0
  5029.8    0.07       0  5120.4   0.045       0
Bank Sta=5022.4,5029.8
Exp/Cntr=0.3,0.1

Type RM Length L Ch R = 1,1594,11,11,11
BEGIN DESCRIPTION:
Mapping XS 8394740f
END DESCRIPTION:
XS GIS Cut Line= 6
      1394790.86      6918934.00      1394763.72      6918803.76
      1394668.24      6918735.40      1394583.60      6918654.02
      1394554.30      6918486.92      1394165.38      6917751.80
#Sta/Elev= 30
  4741.5 1983.34  4799.3 1980.77  4860.0 1973.83  4927.8 1977.81  4957.3 1972.43
  4963.5 1976.02  4978.2 1970.28  4984.4 1972.76  4987.1 1970.19  4987.6 1969.69
  4994.6 1970.19  5027.7 1973.50  5034.9 1970.97  5041.9 1973.99  5049.1 1971.68
  5056.0 1974.57  5063.2 1972.35  5098.5 1975.66  5109.4 1973.50  5125.4 1976.72
  5130.5 1973.47  5176.4 1976.58  5189.9 1973.76  5244.2 1974.31  5249.3 1971.14
  5285.9 1976.08  5291.5 1972.94  5335.5 1978.31  5447.6 1973.74  6110.7 1976.37
#Mann=4,-1,0
  4741.5    0.07       0  4987.1    0.07       0  4994.6    0.07       0
  5447.6   0.045       0
Bank Sta=4987.1,4994.6
Exp/Cntr=0.3,0.1

Type RM Length L Ch R = 1,1583,17,17,17
BEGIN DESCRIPTION:
Mapping XS 6be6e7c2
END DESCRIPTION:
XS GIS Cut Line= 6
      1394797.35      6918930.67      1394775.66      6918793.99
      1394680.17      6918733.23      1394591.20      6918637.74
      1394571.67      6918498.85      1394213.59      6917767.99
#Sta/Elev= 30
  4734.6 1982.79  4798.1 1980.22  4844.5 1973.93  4892.5 1977.83  4907.7 1977.33
  4913.7 1974.69  4928.9 1977.81  4944.1 1977.87  4950.1 1975.62  4971.2 1977.28
  4989.5 1974.72  5000.6 1976.97  5008.2 1975.69  5029.0 1977.69  5085.6 1978.53
  5123.4 1976.90  5187.1 1978.40  5207.3 1976.24  5256.9 1977.72  5262.1 1975.78
  5279.0 1977.38  5284.6 1976.08  5369.0 1977.61  5397.1 1973.46  5438.3 1973.02
  5438.8 1972.52  5445.8 1973.02  5757.1 1976.59  5807.7 1975.01  6070.8 1976.08
#Mann=5,-1,0
  4734.6    0.07       0  4989.5   0.035       0  5008.2    0.07       0
  5438.3   0.035       0  5445.8   0.045       0
Bank Sta=5438.3,5445.8
Exp/Cntr=0.3,0.1

Type RM Length L Ch R = 1,1566,620,620,620
BEGIN DESCRIPTION:
Mapping XS c256ccfa
END DESCRIPTION:
XS GIS Cut Line= 6
      1394803.86      6918927.41      1394784.34      6918783.14
      1394689.94      6918718.04      1394607.47      6918635.57
      1394583.60      6918477.15      1394364.43      6918043.14
#Sta/Elev= 30
  4730.0 1982.82  4834.4 1974.15  4865.5 1975.15  4886.9 1976.96  4961.1 1969.89
  4961.6 1969.39  4968.6 1969.89  4979.8 1976.33  5003.9 1973.80  5007.9 1975.79
  5015.0 1971.81  5022.1 1975.76  5029.1 1972.40  5036.2 1975.76  5057.4 1972.79
  5078.6 1977.93  5085.7 1973.51  5092.8 1977.58  5099.8 1973.33  5105.1 1976.81
  5114.5 1972.77  5153.5 1970.63  5158.5 1976.03  5222.4 1973.30  5235.9 1977.22
  5295.7 1972.12  5318.0 1977.37  5355.8 1978.01  5436.7 1972.94  5753.3 1975.82
#Mann=6,-1,0
  4730.0    0.07       0  4865.5   0.035       0  4961.1   0.035       0
  4968.6   0.035       0  5003.9    0.07       0  5436.7   0.045       0
Bank Sta=4961.1,4968.6
Exp/Cntr=0.3,0.1