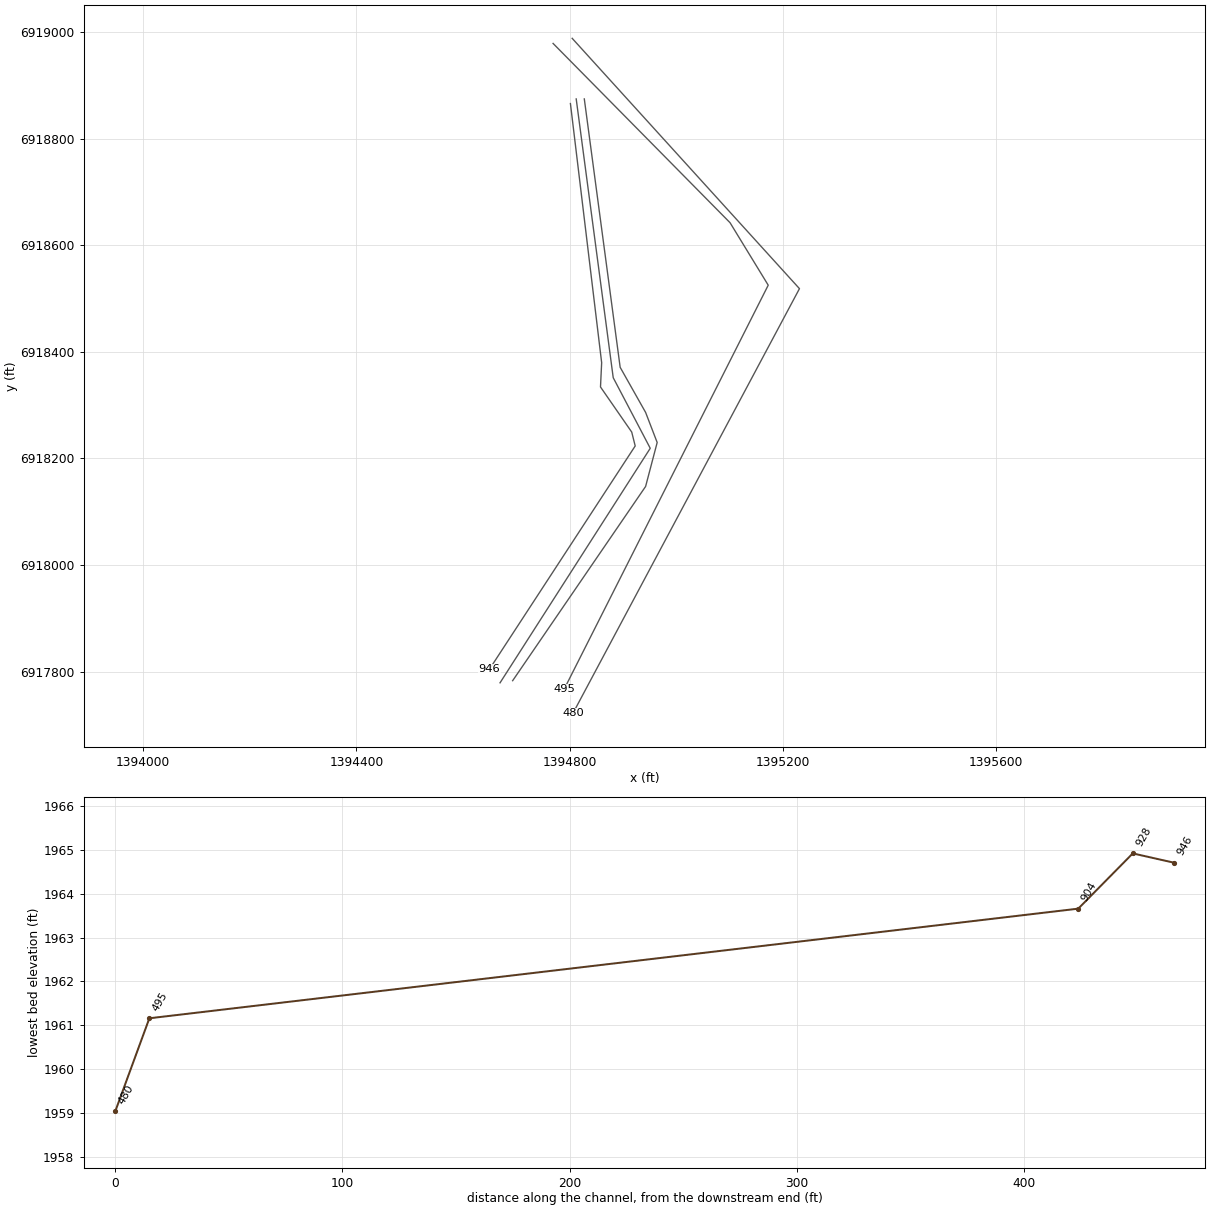
HEC-RAS study Plum Creek Trib5.prj: Plum Creek Trib5 Base Level Engineering

--- Plum Creek Trib5.g01 (geometry) --- (continued)

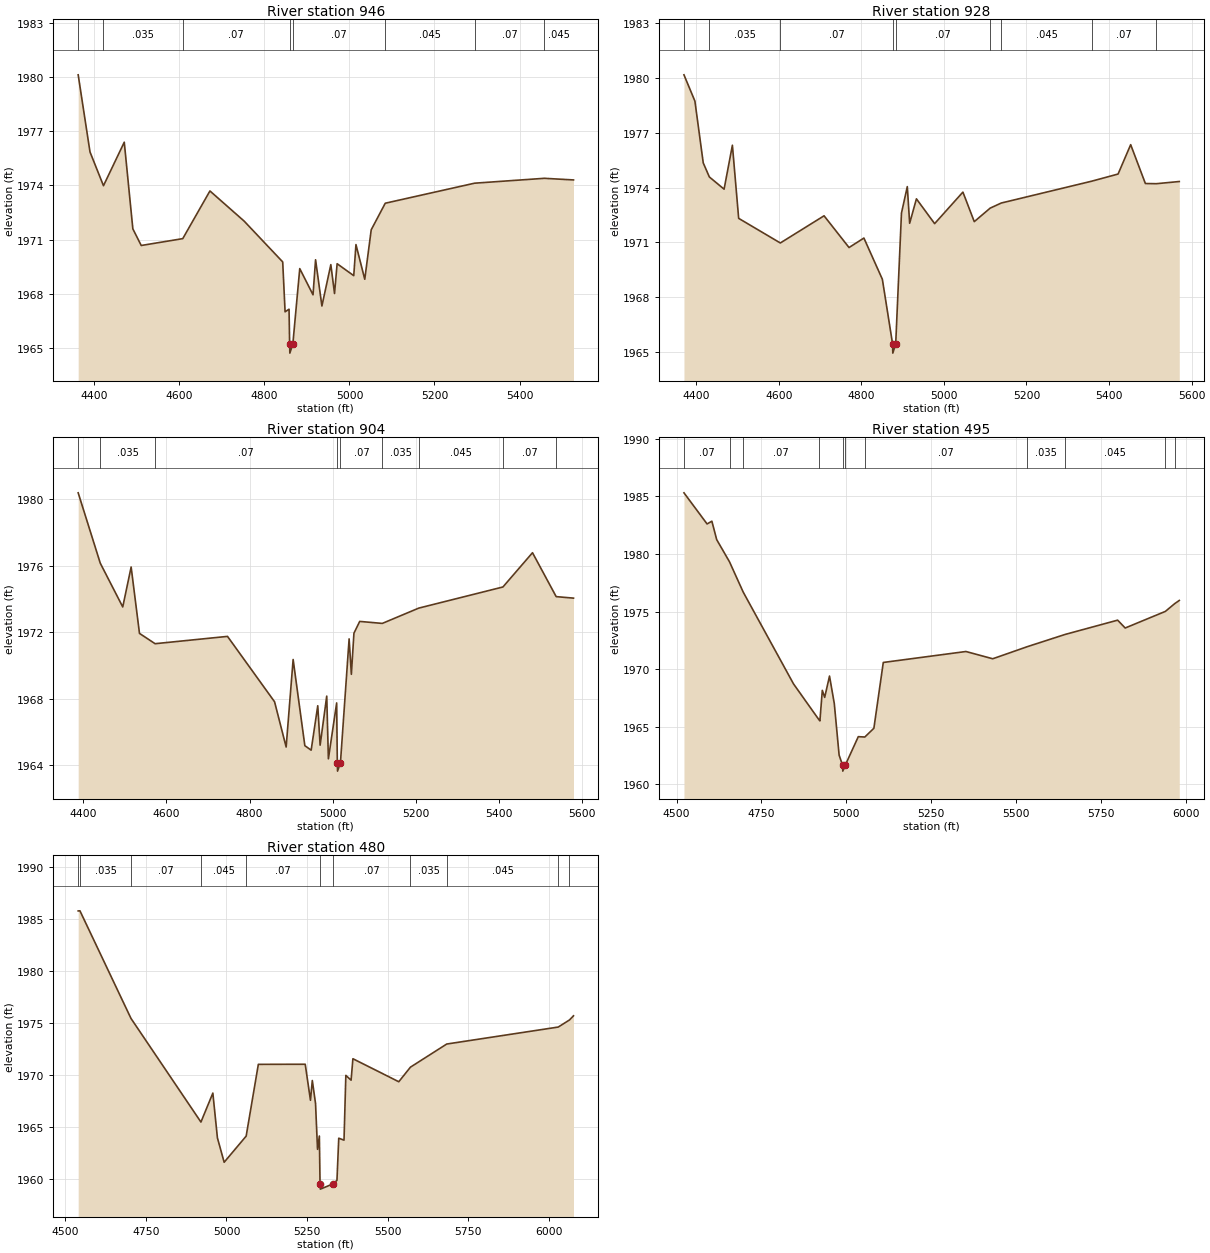
Type RM Length L Ch R = 1,946,18,18,18
BEGIN DESCRIPTION:
Mapping XS a15ed6a4
END DESCRIPTION:
XS GIS Cut Line= 6
      1394801.70      6918865.64      1394860.29      6918379.49
      1394858.12      6918333.92      1394916.72      6918249.29
      1394923.23      6918223.24      1394649.88      6917804.55
#Sta/Elev= 30
  4361.9 1980.12  4389.7 1975.85  4421.4 1973.98  4470.3 1976.39  4490.5 1971.59
  4510.2 1970.67  4607.9 1971.05  4671.8 1973.69  4752.3 1972.02  4843.0 1969.76
  4848.6 1967.00  4857.9 1967.14  4859.3 1965.21  4859.8 1964.71  4866.8 1965.21
  4883.1 1969.39  4914.3 1967.94  4920.3 1969.88  4935.2 1967.32  4956.2 1969.61
  4964.9 1968.01  4971.0 1969.66  5010.1 1969.00  5015.3 1970.72  5036.0 1968.80
  5051.2 1971.54  5084.2 1973.01  5294.4 1974.12  5458.4 1974.39  5527.0 1974.30
#Mann=8,-1,0
  4361.9    0.07       0  4421.4   0.035       0  4607.9    0.07       0
  4859.3    0.07       0  4866.8    0.07       0  5084.2   0.045       0
  5294.4    0.07       0  5458.4   0.045       0
Bank Sta=4859.3,4866.8
Exp/Cntr=0.3,0.1

Type RM Length L Ch R = 1,928,24,24,24
BEGIN DESCRIPTION:
Mapping XS dccea865
END DESCRIPTION:
XS GIS Cut Line= 5
      1394812.55      6918874.31      1394882.00      6918351.28
      1394927.57      6918264.48      1394951.44      6918218.90
      1394669.67      6917778.90
#Sta/Elev= 30
  4370.5 1980.18  4397.0 1978.74  4417.2 1975.35  4432.0 1974.58  4467.7 1973.91
  4487.8 1976.32  4503.0 1972.31  4603.9 1970.96  4709.8 1972.45  4770.3 1970.71
  4806.3 1971.23  4851.0 1968.97  4875.8 1965.42  4876.3 1964.92  4883.3 1965.42
  4897.3 1972.60  4911.4 1974.05  4917.1 1972.04  4933.5 1973.38  4977.6 1972.02
  5046.1 1973.75  5073.6 1972.13  5112.1 1972.87  5138.9 1973.15  5358.4 1974.35
  5421.9 1974.74  5452.4 1976.35  5488.0 1974.22  5514.6 1974.21  5570.1 1974.33
#Mann=9,-1,0
  4370.5    0.07       0  4432.0   0.035       0  4603.9    0.07       0
  4875.8    0.07       0  4883.3    0.07       0  5112.1   0.035       0
  5138.9   0.045       0  5358.4    0.07       0  5514.6   0.045       0
Bank Sta=4875.8,4883.3
Exp/Cntr=0.3,0.1

Type RM Length L Ch R = 1,904,409,409,409
BEGIN DESCRIPTION:
Mapping XS c32f0640
END DESCRIPTION:
XS GIS Cut Line= 6
      1394827.74      6918874.33      1394895.02      6918370.81
      1394942.76      6918286.18      1394964.46      6918229.75
      1394942.76      6918147.29      1394693.31      6917782.88
#Sta/Elev= 30
  4387.5 1980.39  4440.7 1976.16  4494.8 1973.53  4515.0 1975.93  4535.1 1971.94
  4572.7 1971.32  4747.0 1971.76  4860.3 1967.83  4888.2 1965.11  4905.0 1970.37
  4933.2 1965.19  4948.4 1964.92  4964.3 1967.59  4970.0 1965.22  4985.9 1968.17
  4989.9 1964.40  5009.8 1967.76  5011.4 1964.16  5011.9 1963.66  5018.9 1964.16
  5039.8 1971.61  5045.2 1969.48  5051.4 1971.95  5065.3 1972.66  5119.7 1972.54
  5207.5 1973.46  5410.1 1974.73  5481.3 1976.79  5538.3 1974.15  5580.0 1974.06
#Mann=9,-1,0
  4387.5    0.07       0  4440.7   0.035       0  4572.7    0.07       0
  5011.4    0.07       0  5018.9    0.07       0  5119.7   0.035       0
  5207.5   0.045       0  5410.1    0.07       0  5538.3   0.045       0
Bank Sta=5011.4,5018.9
Exp/Cntr=0.3,0.1

Type RM Length L Ch R = 1,495,15,15,15
BEGIN DESCRIPTION:
Mapping XS 49c2c57e
END DESCRIPTION:
XS GIS Cut Line= 4
      1394769.18      6918978.42      1395101.18      6918642.08
      1395172.79      6918524.89      1394790.01      6917767.12
#Sta/Elev= 30
  4521.7 1985.31  4589.8 1982.61  4603.9 1982.85  4618.1 1981.25  4655.9 1979.32
  4696.3 1976.69  4844.4 1968.73  4918.8 1965.64  4922.1 1965.52  4929.2 1968.17
  4936.2 1967.56  4950.4 1969.41  4964.5 1967.02  4978.7 1962.55  4989.0 1961.66
  4989.5 1961.16  4996.6 1961.66  5035.2 1964.15  5054.4 1964.12  5081.1 1964.88
  5108.8 1970.59  5352.2 1971.54  5431.2 1970.91  5533.0 1971.96  5644.2 1973.02
  5799.0 1974.26  5821.3 1973.58  5939.6 1975.02  5967.4 1975.70  5980.6 1975.97
#Mann=11,-1,0
  4521.7    0.07       0  4655.9   0.035       0  4696.3    0.07       0
  4918.8   0.045       0  4989.0   0.045       0  4996.6   0.045       0
  5054.4    0.07       0  5533.0   0.035       0  5644.2   0.045       0
  5939.6    0.07       0  5967.4   0.045       0
Bank Sta=4989,4996.6
Exp/Cntr=0.3,0.1

Type RM Length L Ch R = 1,480,0,0,0
BEGIN DESCRIPTION:
Plum Creek Trib5 1.0
END DESCRIPTION:
XS GIS Cut Line= 3
      1394805.00      6918988.00      1395231.39      6918518.38
      1394806.34      6917721.56
#Sta/Elev= 30
  4539.7 1985.75  4545.2 1985.76  4703.6 1975.43  4920.7 1965.48  4957.7 1968.26
  4971.9 1963.96  4992.8 1961.62  5061.1 1964.13  5098.9 1971.02  5244.4 1971.03
  5260.7 1967.57  5266.4 1969.47  5276.4 1967.27  5282.6 1962.86  5288.3 1964.14
  5290.4 1959.54  5291.4 1959.04  5330.4 1959.54  5342.9 1959.88  5348.5 1963.93
  5364.8 1963.74  5370.5 1969.96  5386.8 1969.50  5392.4 1971.56  5534.8 1969.35
  5571.0 1970.75  5683.6 1972.97  6029.7 1974.60  6064.6 1975.28  6077.1 1975.68
#Mann=11,-1,0
  4539.7    0.07       0  4545.2   0.035       0  4703.6    0.07       0
  4920.7   0.045       0  5061.1    0.07       0  5290.4   0.045       0
  5330.4    0.07       0  5571.0   0.035       0  5683.6   0.045       0
  6029.7    0.07       0  6064.6   0.045       0
Bank Sta=5290.4,5330.4
Exp/Cntr=0.3,0.1

Chan Stop Cuts=-1