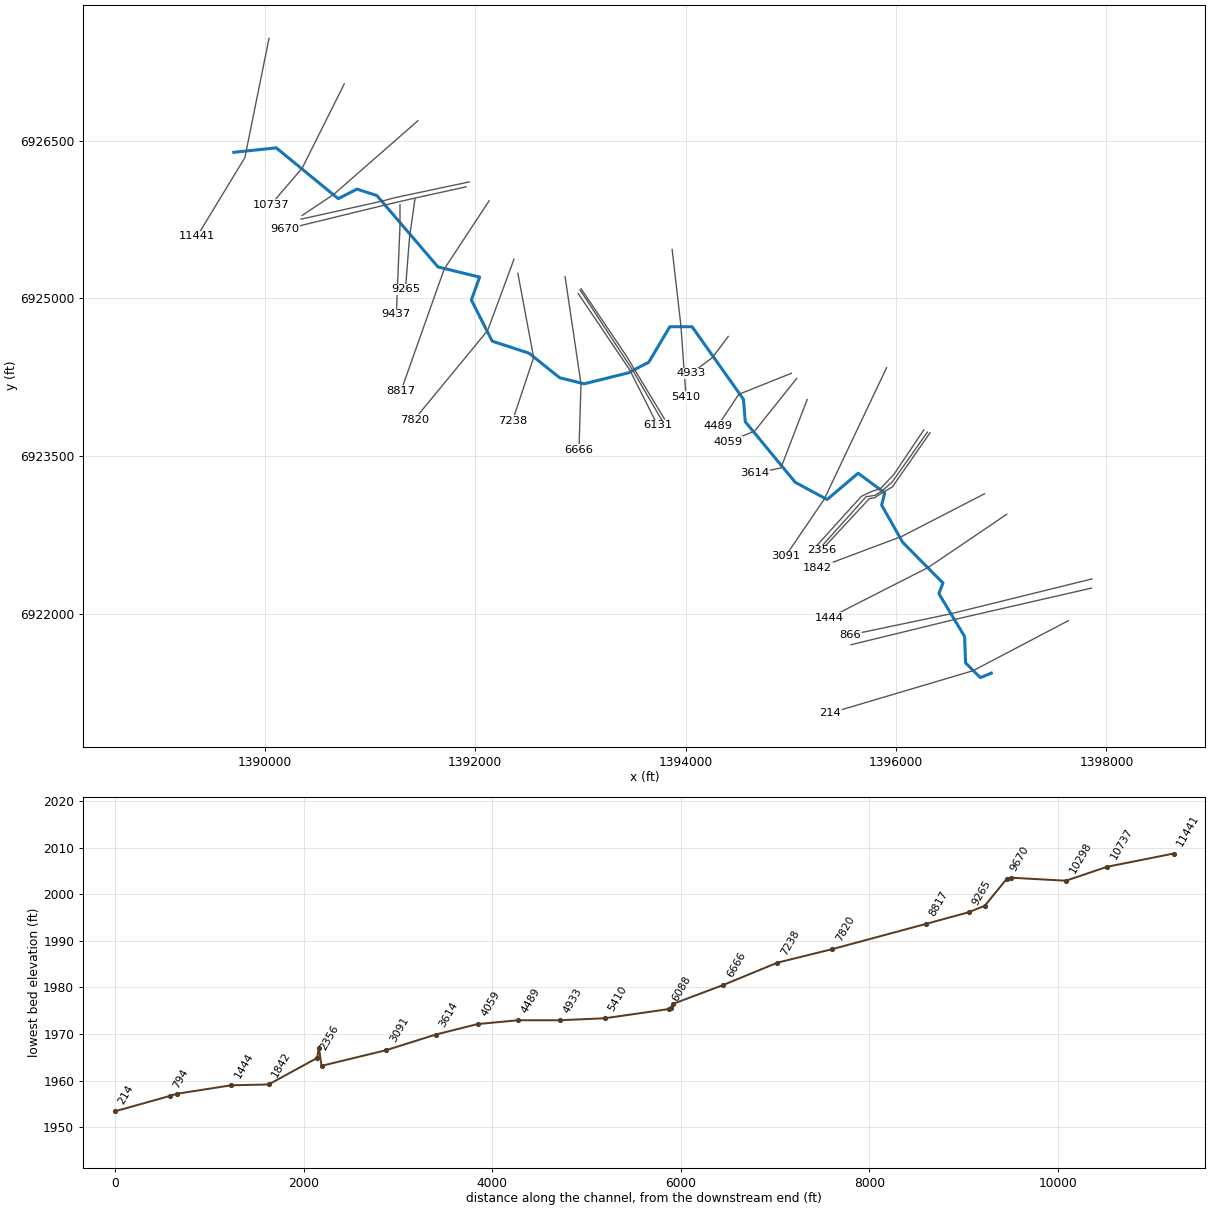
--- Plum Creek Trib6.prj (project) ---

Proj Title=Plum Creek Trib6 Base Level Engineering
Current Plan=p01
Default Exp/Contr=0.3,0.1
English Units
Geom File=g01
Flow File=f01
Plan File=p01
BEGIN DESCRIPTION:
Plum Creek Trib6
END DESCRIPTION:

--- Plum Creek Trib6.p01 (plan) ---

Plan Title=Multiple Run
Short Identifier=Multiple
Geom File=g01
Flow File=f01
Subcritical Flow
K Sum by GR= 0
Std Step Tol= 0.01
Critical Tol= 0.01
Num of Std Step Trials= 20
Max Error Tol= 0.3
Flow Tol Ratio= 0.001
Split Flow NTrial= 30
Split Flow Tol= 0.02
Split Flow Ratio= 0.02
Log Output Level= 0
Friction Slope Method= 1
Unsteady Friction Slope Method= 2
Unsteady Bridges Friction Slope Method= 1
Parabolic Critical Depth
Global Vel Dist=  1 , 1 , 1
Global Log Level= 0
CheckData=True
Encroach Param= -1, 0, 0, 0
BEGIN DESCRIPTION:
Multiple Run
END DESCRIPTION:

--- Plum Creek Trib6.f01 (steady flow) ---

Flow Title=Multiple
Number of Profiles=7
Profile Names=10-year,25-year,50-year,1pct_min,100-year,1pct_plu,500-year
River Rch & RM= Plum Creek Trib6,Reach-1,11441
     299     425     530     329     657    1311    1021
River Rch & RM= Plum Creek Trib6,Reach-1,8817
     317     449     560     347     692    1381    1071
River Rch & RM= Plum Creek Trib6,Reach-1,7238
     410     588     740     462     922    1840    1451
River Rch & RM= Plum Creek Trib6,Reach-1,5410
     487     703     888     556    1110    2215    1760
Boundary for River Rch & Prof#=Plum Creek Trib6,Reach-1,1
Up Type=0
Dn Type=3
Dn Slope=0.005
Boundary for River Rch & Prof#=Plum Creek Trib6,Reach-1,2
Up Type=0
Dn Type=3
Dn Slope=0.005
Boundary for River Rch & Prof#=Plum Creek Trib6,Reach-1,3
Up Type=0
Dn Type=3
Dn Slope=0.005
Boundary for River Rch & Prof#=Plum Creek Trib6,Reach-1,4
Up Type=0
Dn Type=3
Dn Slope=0.005
Boundary for River Rch & Prof#=Plum Creek Trib6,Reach-1,5
Up Type=0
Dn Type=3
Dn Slope=0.005
Boundary for River Rch & Prof#=Plum Creek Trib6,Reach-1,6
Up Type=0
Dn Type=3
Dn Slope=0.005
Boundary for River Rch & Prof#=Plum Creek Trib6,Reach-1,7
Up Type=0
Dn Type=3
Dn Slope=0.005

--- Plum Creek Trib6.g01 (geometry) ---

Geom Title=Existing Conditions

River Reach=Plum Creek Trib6,Reach-1
Reach XY= 30
      1389705.00      6926388.00      1390108.43      6926430.21
      1390697.99      6925946.99      1390875.20      6926038.37
      1391065.02      6925976.77      1391645.32      6925298.76
      1392041.62      6925201.88      1391963.08      6924984.70
      1392160.62      6924593.62      1392511.67      6924478.70
      1392801.67      6924246.02      1393034.90      6924187.90
      1393453.26      6924291.37      1393649.75      6924393.44
      1393848.79      6924730.20      1394061.21      6924730.20
      1394549.48      6924040.43      1394566.26      6923828.01
      1395041.79      6923251.63      1395344.38      6923088.59
      1395639.64      6923338.11      1395891.88      6923151.24
      1395862.82      6923034.59      1396062.86      6922681.83
      1396445.85      6922294.73      1396406.66      6922194.05
      1396651.63      6921786.27      1396660.52      6921535.57
      1396801.61      6921395.59      1396905.00      6921438.00

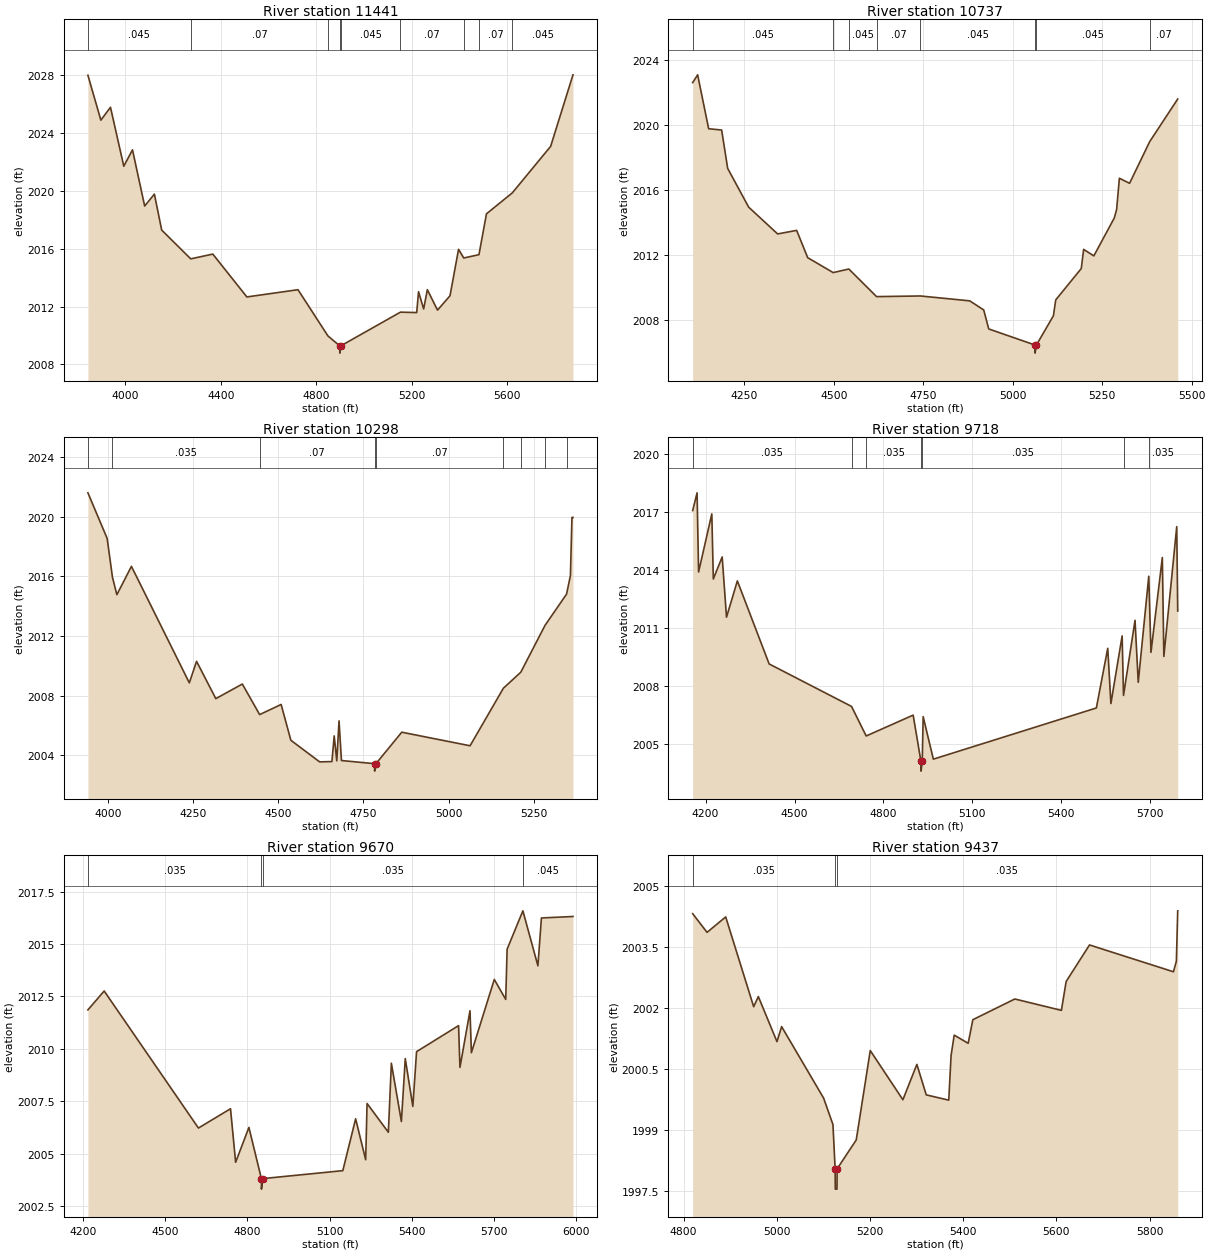
Type RM Length L Ch R = 1,11441,704,704,704
BEGIN DESCRIPTION:
Plum Creek Trib6 20.0
END DESCRIPTION:
XS GIS Cut Line= 3
      1390039.70      6927471.17      1389810.06      6926337.19
      1389354.98      6925587.97
#Sta/Elev= 30
  3843.0 2027.97  3897.3 2024.87  3937.6 2025.76  3993.4 2021.69  4029.9 2022.82
  4080.9 2018.94  4121.7 2019.76  4152.3 2017.28  4274.1 2015.29  4366.6 2015.62
  4509.4 2012.66  4723.7 2013.16  4849.2 2009.97  4898.9 2009.28  4899.1 2008.78
  4902.9 2009.28  5153.4 2011.61  5221.4 2011.58  5229.2 2013.02  5250.6 2011.83
  5266.1 2013.16  5308.7 2011.75  5361.0 2012.74  5396.9 2015.95  5418.8 2015.35
  5482.5 2015.58  5513.9 2018.40  5622.4 2019.85  5783.0 2023.06  5876.6 2028.00
#Mann=9,-1,0
  3843.0   0.045       0  4274.1    0.07       0  4849.2   0.045       0
  4898.9   0.045       0  4902.9   0.045       0  5153.4    0.07       0
  5418.8   0.045       0  5482.5    0.07       0  5622.4   0.045       0
Bank Sta=4898.9,4902.9
Exp/Cntr=0.3,0.1

Type RM Length L Ch R = 1,10737,439,439,439
BEGIN DESCRIPTION:
Plum Creek Trib6 19.0
END DESCRIPTION:
XS GIS Cut Line= 3
      1390754.98      6927037.96      1390355.00      6926238.00
      1390054.97      6925887.97
#Sta/Elev= 30
  4105.7 2022.61  4119.6 2023.09  4150.4 2019.77  4186.7 2019.69  4203.5 2017.33
  4262.2 2014.94  4343.2 2013.29  4396.3 2013.51  4427.1 2011.83  4498.3 2010.91
  4542.1 2011.13  4619.6 2009.43  4741.7 2009.47  4879.9 2009.17  4919.0 2008.61
  4933.0 2007.44  5062.2 2006.45  5062.5 2005.95  5066.3 2006.45  5113.7 2008.25
  5120.3 2009.23  5191.6 2011.16  5198.2 2012.34  5226.7 2011.94  5283.8 2014.27
  5290.4 2014.80  5298.1 2016.72  5326.6 2016.41  5382.9 2018.98  5461.1 2021.60
#Mann=8,-1,0
  4105.7   0.045       0  4498.3    0.07       0  4542.1   0.045       0
  4619.6    0.07       0  4741.7   0.045       0  5062.2   0.045       0
  5066.3   0.045       0  5382.9    0.07       0
Bank Sta=5062.2,5066.3
Exp/Cntr=0.3,0.1

Type RM Length L Ch R = 1,10298,580,580,580
BEGIN DESCRIPTION:
Plum Creek Trib6 18.0
END DESCRIPTION:
XS GIS Cut Line= 3
      1391455.01      6926688.01      1390655.00      6925988.00
      1390354.99      6925787.99
#Sta/Elev= 30
  3941.5 2021.60  3998.0 2018.54  4013.6 2015.93  4026.5 2014.77  4069.2 2016.67
  4239.1 2008.86  4260.4 2010.30  4316.9 2007.80  4394.7 2008.78  4445.5 2006.73
  4508.6 2007.41  4537.1 2005.01  4621.6 2003.56  4657.6 2003.58  4664.3 2005.30
  4671.9 2003.63  4678.5 2006.31  4685.6 2003.65  4782.7 2003.44  4783.0 2002.94
  4786.9 2003.44  4862.6 2005.55  5063.1 2004.64  5160.9 2008.50  5211.9 2009.57
  5283.0 2012.71  5346.3 2014.81  5357.6 2016.05  5362.1 2019.95  5365.1 2019.95
#Mann=9,-1,0
  3941.5    0.07       0  4013.6   0.035       0  4445.5    0.07       0
  4782.7    0.07       0  4786.9    0.07       0  5160.9   0.045       0
  5211.9    0.07       0  5283.0   0.045       0  5346.3   0.035       0
Bank Sta=4782.7,4786.9
Exp/Cntr=0.3,0.1

Type RM Length L Ch R = 1,9718,48,48,48
BEGIN DESCRIPTION:
Mapping XS dd11ca0c
END DESCRIPTION:
XS GIS Cut Line= 4
      1391942.47      6926106.54      1391230.66      6925955.50
      1391123.02      6925925.99      1390344.96      6925752.70
#Sta/Elev= 30
  4156.3 2017.08  4171.2 2018.00  4176.3 2013.90  4220.9 2016.91  4226.0 2013.54
  4255.9 2014.68  4270.5 2011.56  4307.1 2013.44  4414.3 2009.14  4692.3 2006.94
  4741.7 2005.41  4900.2 2006.49  4926.5 2004.09  4926.8 2003.59  4930.8 2004.09
  4933.9 2006.41  4968.3 2004.21  5518.2 2006.86  5556.6 2009.95  5567.3 2007.09
  5605.2 2010.59  5609.8 2007.51  5648.7 2011.40  5659.5 2008.19  5695.0 2013.68
  5702.4 2009.74  5740.8 2014.65  5745.9 2009.53  5789.4 2016.25  5792.7 2011.88
#Mann=7,-1,0
  4156.3   0.035       0  4692.3    0.07       0  4741.7   0.035       0
  4926.5   0.035       0  4930.8   0.035       0  5609.8    0.07       0
  5695.0   0.035       0
Bank Sta=4926.5,4930.8
Exp/Cntr=0.3,0.1

Type RM Length L Ch R = 1,9670,233,233,233
BEGIN DESCRIPTION:
Mapping XS 09c6c300
END DESCRIPTION:
XS GIS Cut Line= 4
      1391912.96      6926059.67      1391383.44      6925943.35
      1391145.59      6925887.79      1390190.72      6925655.15
#Sta/Elev= 30
  4218.0 2011.86  4277.3 2012.76  4621.1 2006.23  4738.1 2007.15  4756.8 2004.60
  4805.2 2006.26  4850.7 2003.82  4851.0 2003.32  4855.0 2003.82  5147.7 2004.20
  5194.5 2006.67  5231.1 2004.72  5236.2 2007.40  5313.8 2006.03  5324.8 2009.32
  5361.4 2006.54  5375.5 2009.54  5403.1 2007.26  5416.7 2009.87  5569.9 2011.11
  5575.0 2009.12  5611.6 2011.82  5616.7 2009.82  5700.2 2013.31  5741.9 2012.36
  5747.0 2014.75  5804.5 2016.58  5859.3 2013.96  5872.1 2016.24  5987.2 2016.31
#Mann=4,-1,0
  4218.0   0.035       0  4850.7   0.035       0  4855.0   0.035       0
  5804.5   0.045       0
Bank Sta=4850.7,4855
Exp/Cntr=0.3,0.1

Type RM Length L Ch R = 1,9437,172,172,172
BEGIN DESCRIPTION:
Mapping XS 8d09d91c
END DESCRIPTION:
XS GIS Cut Line= 3
      1391284.59      6925888.91      1391284.59      6925691.03
      1391249.94      6924848.82
#Sta/Elev= 30
  4819.6 2004.33  4850.5 2003.87  4890.5 2004.25  4950.5 2002.04  4960.5 2002.29
  5000.5 2001.18  5010.5 2001.55  5100.6 1999.79  5120.6 1999.14  5125.3 1998.05
  5125.6 1997.55  5129.3 1997.55  5129.6 1998.05  5170.6 1998.76  5200.7 2000.96
  5270.7 1999.75  5300.7 2000.62  5320.8 1999.87  5369.1 1999.74  5374.1 2000.84
  5380.8 2001.34  5410.8 2001.14  5420.8 2001.72  5510.9 2002.23  5610.8 2001.95
  5621.0 2002.66  5671.1 2003.56  5851.2 2002.90  5857.5 2003.16  5860.4 2004.40
#Mann=3,-1,0
  4819.6   0.035       0  5125.3   0.035       0  5129.6   0.035       0
Bank Sta=5125.3,5129.6
Exp/Cntr=0.3,0.1

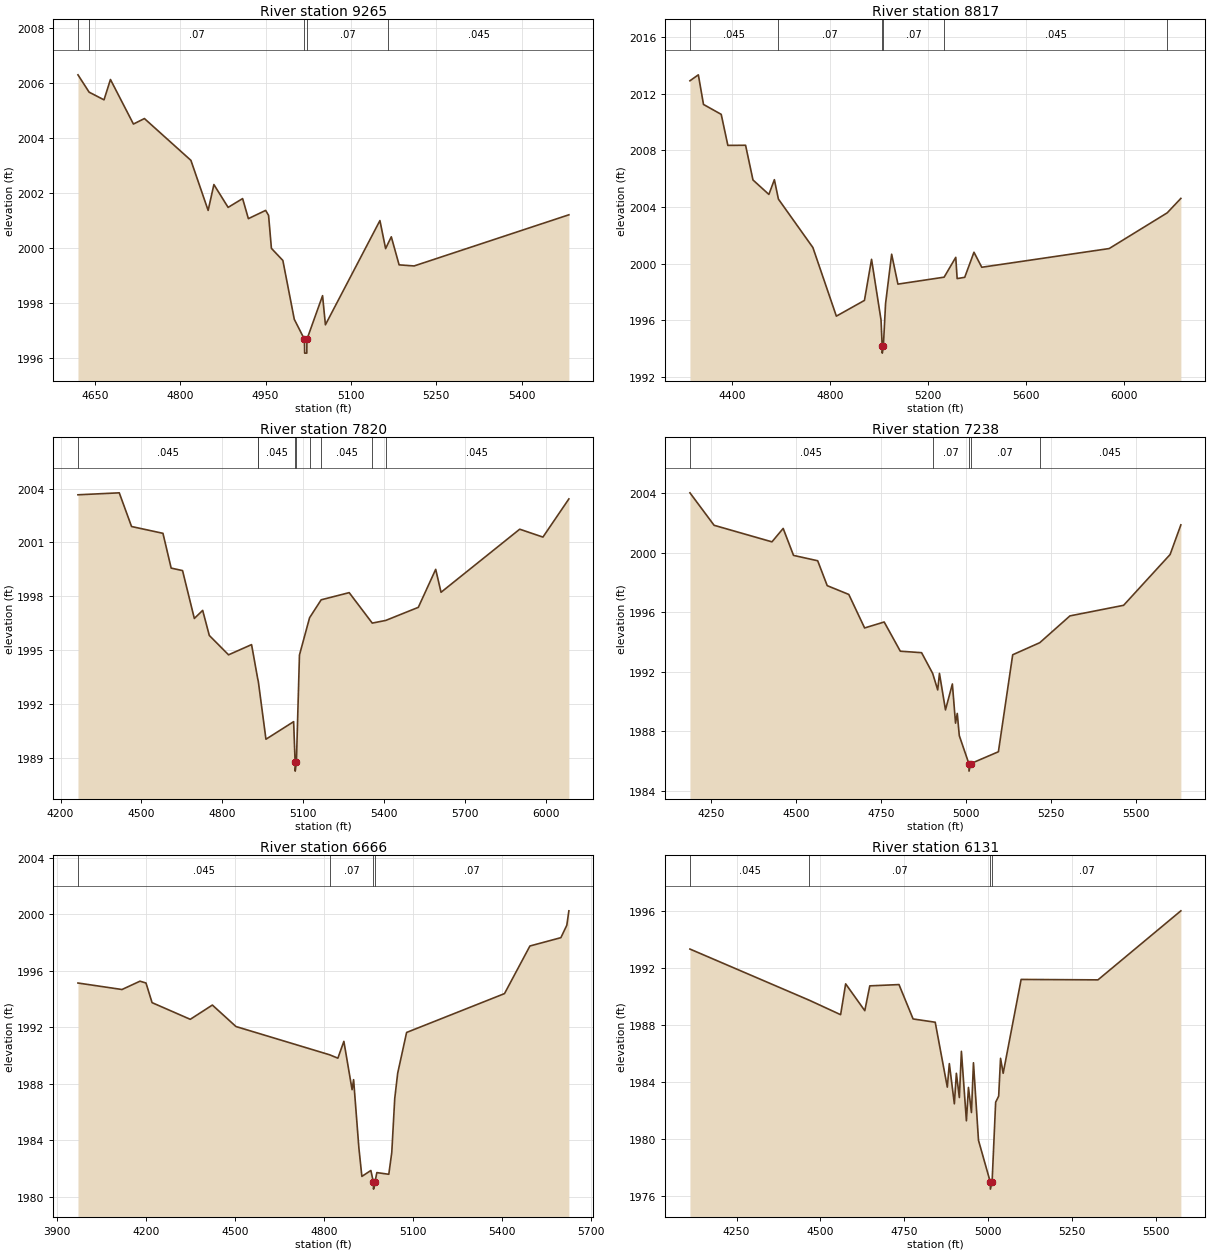
Type RM Length L Ch R = 1,9265,448,448,448
BEGIN DESCRIPTION:
Mapping XS ab497e61
END DESCRIPTION:
XS GIS Cut Line= 3
      1391426.96      6925944.51      1391374.87      6925576.45
      1391336.68      6925086.86
#Sta/Elev= 30
  4620.3 2006.28  4639.9 2005.65  4666.1 2005.37  4677.4 2006.11  4717.8 2004.49
  4737.1 2004.69  4818.8 2003.17  4849.1 2001.35  4859.2 2002.29  4884.2 2001.46
  4909.7 2001.78  4919.8 2001.05  4950.1 2001.35  4955.3 2001.17  4960.3 1999.97
  4980.4 1999.53  5000.5 1997.39  5018.4 1996.66  5018.7 1996.16  5022.5 1996.16
  5022.7 1996.66  5050.2 1998.25  5055.2 1997.19  5151.0 2000.98  5161.0 1999.96
  5165.8 2000.17  5171.0 2000.39  5184.7 1999.37  5211.1 1999.33  5483.1 2001.19
#Mann=5,-1,0
  4620.3   0.035       0  4639.9    0.07       0  5018.4    0.07       0
  5022.7    0.07       0  5165.8   0.045       0
Bank Sta=5018.4,5022.7
Exp/Cntr=0.3,0.1

Type RM Length L Ch R = 1,8817,997,997,997
BEGIN DESCRIPTION:
Mapping XS b27bd77c
END DESCRIPTION:
XS GIS Cut Line= 3
      1392131.80      6925927.12      1391704.73      6925277.84
      1391295.26      6924122.28
#Sta/Elev= 30
  4227.6 2012.90  4261.9 2013.32  4282.9 2011.23  4355.2 2010.53  4382.3 2008.34
  4454.6 2008.35  4484.8 2005.90  4549.7 2004.88  4572.1 2005.92  4588.6 2004.55
  4729.3 2001.13  4825.0 1996.29  4939.6 1997.40  4968.6 2000.30  5007.3 1996.02
  5012.0 1994.18  5012.3 1993.68  5016.8 1994.18  5025.8 1997.18  5050.6 2000.66
  5076.2 1998.55  5264.7 1999.04  5312.2 2000.44  5317.9 1998.94  5348.8 1999.03
  5386.5 2000.80  5418.3 1999.74  5938.2 2001.06  6175.0 2003.58  6230.7 2004.60
#Mann=6,-1,0
  4227.6   0.045       0  4588.6    0.07       0  5012.0    0.07       0
  5016.8    0.07       0  5264.7   0.045       0  6175.0   0.035       0
Bank Sta=5012,5016.8
Exp/Cntr=0.3,0.1

Type RM Length L Ch R = 1,7820,582,582,582
BEGIN DESCRIPTION:
Mapping XS dd00ad4a
END DESCRIPTION:
XS GIS Cut Line= 3
      1392367.93      6925371.60      1392117.93      6924694.50
      1391420.04      6923847.31
#Sta/Elev= 30
  4264.6 2003.66  4417.7 2003.77  4463.2 2001.89  4579.6 2001.51  4610.0 1999.57
  4652.2 1999.43  4695.9 1996.76  4726.8 1997.21  4751.4 1995.81  4822.7 1994.73
  4908.0 1995.30  4930.7 1993.40  4933.0 1993.25  4961.3 1990.02  5063.9 1991.00
  5069.4 1988.74  5069.7 1988.24  5074.2 1988.74  5085.5 1994.72  5123.0 1996.80
  5165.9 1997.80  5269.8 1998.20  5355.3 1996.50  5405.4 1996.65  5526.0 1997.38
  5590.4 1999.50  5610.2 1998.22  5901.8 2001.74  5987.8 2001.30  6084.0 2003.43
#Mann=9,-1,0
  4264.6   0.045       0  4930.7    0.07       0  4933.0   0.045       0
  5069.4   0.045       0  5074.2   0.045       0  5123.0    0.07       0
  5165.9   0.045       0  5355.3    0.07       0  5405.4   0.045       0
Bank Sta=5069.4,5074.2
Exp/Cntr=0.3,0.1

Type RM Length L Ch R = 1,7238,572,572,572
BEGIN DESCRIPTION:
Plum Creek Trib6 13.0
END DESCRIPTION:
XS GIS Cut Line= 3
      1392405.01      6925237.97      1392555.00      6924438.00
      1392354.99      6923837.97
#Sta/Elev= 30
  4186.7 2004.01  4257.9 2001.83  4428.3 2000.72  4461.4 2001.62  4491.9 1999.81
  4563.1 1999.45  4591.1 1997.78  4654.7 1997.19  4701.3 1994.94  4759.0 1995.34
  4806.5 1993.38  4869.2 1993.28  4901.8 1991.89  4916.7 1990.78  4921.8 1991.89
  4939.6 1989.44  4959.9 1991.18  4969.2 1988.55  4974.3 1989.20  4980.3 1987.71
  5008.6 1985.83  5009.0 1985.33  5013.7 1985.83  5095.5 1986.63  5137.6 1993.14
  5217.3 1993.95  5306.3 1995.75  5464.4 1996.46  5601.4 1999.87  5633.1 2001.86
#Mann=5,-1,0
  4186.7   0.045       0  4901.8    0.07       0  5008.6    0.07       0
  5013.7    0.07       0  5217.3   0.045       0
Bank Sta=5008.6,5013.7
Exp/Cntr=0.3,0.1

Type RM Length L Ch R = 1,6666,535,535,535
BEGIN DESCRIPTION:
Plum Creek Trib6 12.0
END DESCRIPTION:
XS GIS Cut Line= 3
      1392854.04      6925204.92      1393004.99      6924187.15
      1392986.04      6923561.04
#Sta/Elev= 30
  3971.1 1995.14  4119.6 1994.68  4180.3 1995.27  4200.5 1995.14  4221.0 1993.75
  4349.8 1992.57  4424.3 1993.58  4503.8 1992.06  4819.6 1990.06  4847.5 1989.82
  4867.7 1991.01  4895.4 1987.59  4900.5 1988.30  4918.3 1983.47  4928.4 1981.45
  4958.7 1981.87  4967.2 1981.05  4967.7 1980.55  4972.6 1981.05  4978.9 1981.72
  5019.2 1981.60  5029.2 1983.14  5039.2 1986.96  5049.2 1988.76  5079.2 1991.64
  5409.3 1994.39  5495.0 1997.76  5599.4 1998.35  5619.4 1999.23  5626.4 2000.25
#Mann=4,-1,0
  3971.1   0.045       0  4819.6    0.07       0  4967.2    0.07       0
  4972.6    0.07       0
Bank Sta=4967.2,4972.6
Exp/Cntr=0.3,0.1

Type RM Length L Ch R = 1,6131,24,24,24
BEGIN DESCRIPTION:
Mapping XS 931cdabc
END DESCRIPTION:
XS GIS Cut Line= 3
      1392979.06      6925045.16      1393468.62      6924319.50
      1393732.50      6923795.22
#Sta/Elev= 30
  4111.3 1993.31  4467.0 1989.72  4560.1 1988.71  4575.1 1990.87  4632.1 1988.99
  4647.0 1990.73  4734.0 1990.82  4776.0 1988.41  4841.9 1988.18  4877.9 1983.63
  4883.9 1985.28  4898.9 1982.46  4904.9 1984.60  4913.8 1982.90  4919.9 1986.14
  4934.8 1981.27  4940.9 1983.61  4949.8 1981.85  4955.8 1985.34  4970.8 1979.90
  5005.9 1976.98  5006.3 1976.48  5011.3 1976.98  5021.9 1982.57  5030.9 1983.00
  5036.5 1985.65  5044.3 1984.60  5097.8 1991.18  5326.6 1991.15  5573.6 1995.99
#Mann=4,-1,0
  4111.3   0.045       0  4467.0    0.07       0  5005.9    0.07       0
  5011.3    0.07       0
Bank Sta=5005.9,5011.3
Exp/Cntr=0.3,0.1

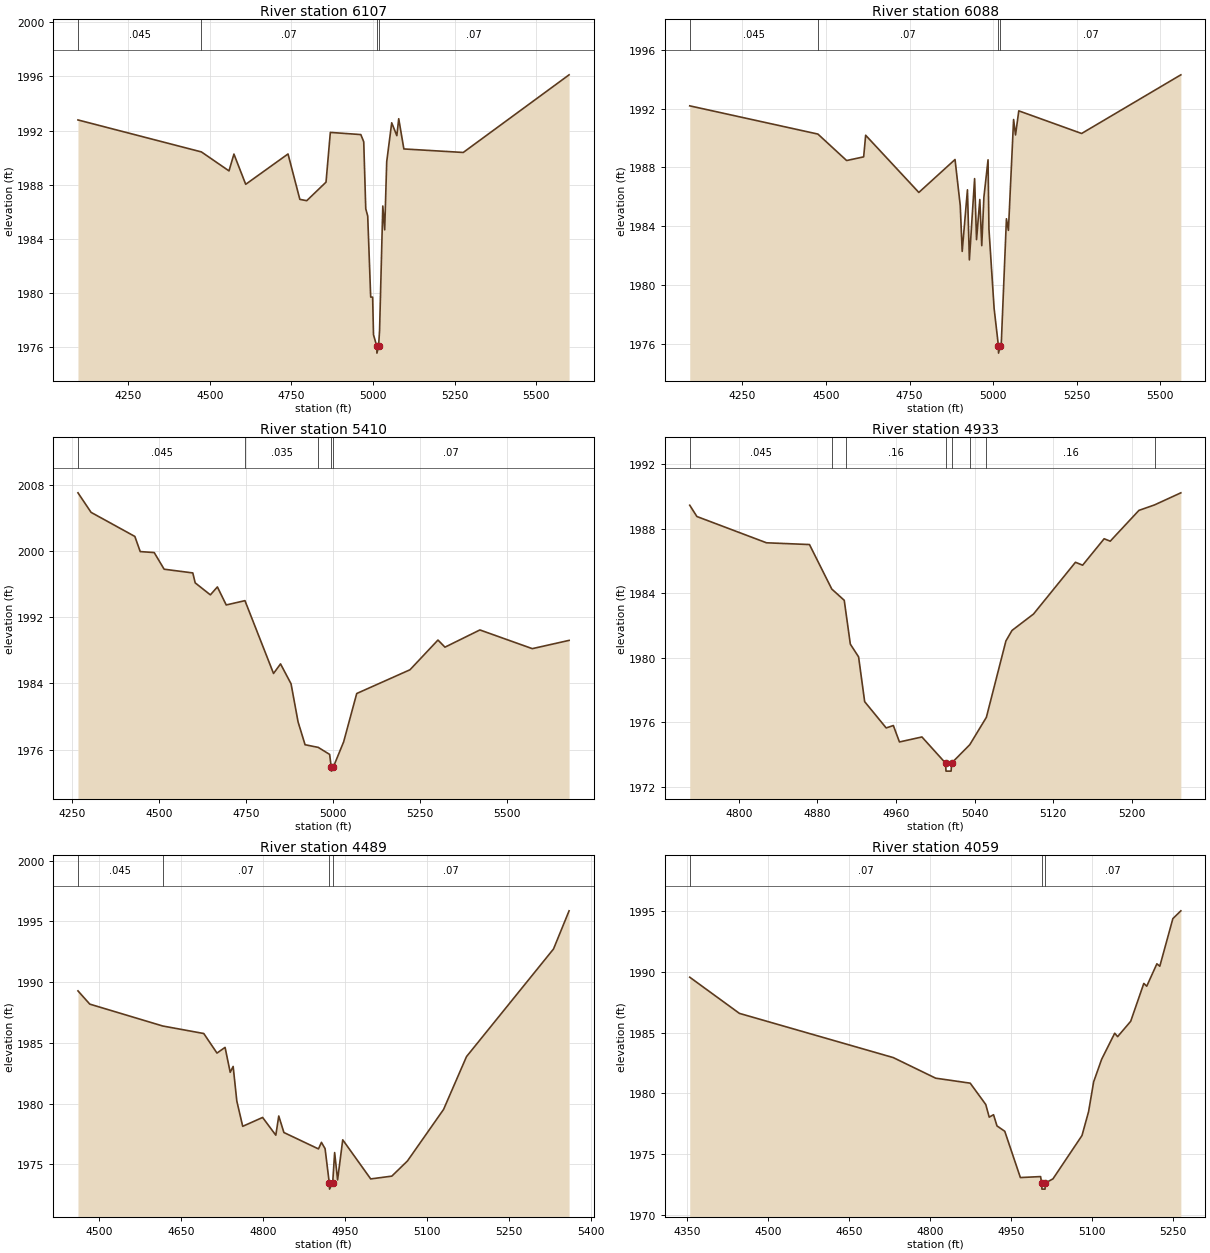
Type RM Length L Ch R = 1,6107,19,19,19
BEGIN DESCRIPTION:
Mapping XS b80d3f8b
END DESCRIPTION:
XS GIS Cut Line= 4
      1392996.41      6925079.91      1393413.07      6924444.50
      1393492.93      6924322.98      1393794.99      6923805.65
#Sta/Elev= 30
  4096.1 1992.78  4474.2 1990.42  4558.7 1989.02  4573.8 1990.26  4609.9 1988.03
  4739.5 1990.27  4775.7 1986.92  4796.8 1986.82  4855.9 1988.19  4869.1 1991.86
  4962.5 1991.70  4971.4 1991.17  4977.6 1986.22  4983.6 1985.69  4992.7 1979.71
  4998.7 1979.70  5001.3 1976.93  5011.4 1976.07  5011.8 1975.57  5016.8 1976.07
  5019.9 1977.22  5029.8 1986.43  5035.6 1984.67  5041.8 1989.70  5057.1 1992.57
  5072.8 1991.62  5078.6 1992.87  5094.3 1990.64  5276.2 1990.38  5600.4 1996.11
#Mann=4,-1,0
  4096.1   0.045       0  4474.2    0.07       0  5011.4    0.07       0
  5016.8    0.07       0
Bank Sta=5011.4,5016.8
Exp/Cntr=0.3,0.1

Type RM Length L Ch R = 1,6088,678,678,678
BEGIN DESCRIPTION:
Mapping XS 9d5a54b5
END DESCRIPTION:
XS GIS Cut Line= 4
      1393006.80      6925090.36      1393444.32      6924441.03
      1393499.87      6924347.28      1393798.49      6923854.21
#Sta/Elev= 30
  4092.7 1992.19  4475.9 1990.27  4561.8 1988.47  4612.7 1988.72  4618.7 1990.19
  4777.7 1986.30  4885.9 1988.54  4901.5 1985.41  4907.3 1982.29  4923.0 1986.48
  4928.8 1981.71  4944.4 1987.24  4950.2 1983.09  4960.0 1985.82  4965.8 1982.68
  4972.2 1985.98  4984.6 1988.52  4987.3 1983.81  5002.8 1978.40  5015.6 1975.87
  5016.0 1975.37  5021.0 1975.87  5024.1 1975.98  5039.6 1984.51  5045.5 1983.72
  5061.0 1991.26  5066.8 1990.21  5076.5 1991.85  5264.4 1990.31  5561.1 1994.30
#Mann=4,-1,0
  4092.7   0.045       0  4475.9    0.07       0  5015.6    0.07       0
  5021.0    0.07       0
Bank Sta=5015.6,5021
Exp/Cntr=0.3,0.1

Type RM Length L Ch R = 1,5410,477,477,477
BEGIN DESCRIPTION:
Plum Creek Trib6 10.0
END DESCRIPTION:
XS GIS Cut Line= 3
      1393871.40      6925465.38      1393955.00      6924738.00
      1394003.33      6924062.80
#Sta/Elev= 30
  4268.0 2007.02  4305.6 2004.66  4431.2 2001.75  4446.6 1999.92  4486.8 1999.80
  4515.2 1997.79  4597.5 1997.34  4604.3 1996.14  4647.9 1994.69  4668.0 1995.65
  4693.4 1993.47  4747.1 1993.99  4829.1 1985.19  4849.2 1986.35  4879.4 1983.94
  4899.5 1979.34  4919.6 1976.58  4957.3 1976.26  4990.1 1975.41  4994.6 1973.89
  4995.1 1973.39  5000.7 1973.89  5030.2 1976.92  5067.8 1982.77  5220.7 1985.64
  5300.9 1989.23  5321.0 1988.37  5421.2 1990.45  5571.6 1988.19  5677.1 1989.19
#Mann=5,-1,0
  4268.0   0.045       0  4747.1   0.035       0  4957.3    0.07       0
  4994.6    0.07       0  5000.7    0.07       0
Bank Sta=4994.6,5000.7
Exp/Cntr=0.3,0.1

Type RM Length L Ch R = 1,4933,444,444,444
BEGIN DESCRIPTION:
Plum Creek Trib6 9.0
END DESCRIPTION:
XS GIS Cut Line= 3
      1394404.99      6924637.99      1394255.00      6924438.00
      1394054.99      6924287.99
#Sta/Elev= 30
  4750.0 1989.46  4757.3 1988.76  4828.1 1987.13  4871.9 1987.02  4894.6 1984.26
  4907.3 1983.56  4909.3 1982.68  4913.5 1980.84  4921.9 1980.05  4928.1 1977.27
  4950.0 1975.64  4957.3 1975.79  4963.5 1974.77  4986.4 1975.08  5010.4 1973.46
  5010.9 1972.96  5016.1 1972.96  5016.6 1973.46  5035.1 1974.60  5052.0 1976.30
  5071.9 1981.04  5078.1 1981.69  5100.0 1982.71  5142.7 1985.92  5150.0 1985.74
  5171.9 1987.38  5178.1 1987.23  5207.3 1989.14  5223.2 1989.48  5250.0 1990.23
#Mann=8,-1,0
  4750.0   0.045       0  4894.6    0.07       0  4909.3    0.16       0
  5010.4    0.07       0  5016.6    0.16       0  5035.1    0.07       0
  5052.0    0.16       0  5223.2    0.07       0
Bank Sta=5010.4,5016.6
Exp/Cntr=0.3,0.1

Type RM Length L Ch R = 1,4489,430,430,430
BEGIN DESCRIPTION:
Plum Creek Trib6 8.0
END DESCRIPTION:
XS GIS Cut Line= 3
      1395005.04      6924288.02      1394505.00      6924088.00
      1394305.01      6923788.02
#Sta/Elev= 30
  4461.7 1989.28  4483.3 1988.19  4616.8 1986.39  4692.0 1985.77  4716.2 1984.16
  4731.0 1984.63  4740.4 1982.58  4745.8 1983.06  4752.5 1980.21  4763.3 1978.13
  4799.7 1978.86  4823.9 1977.40  4829.3 1978.98  4838.7 1977.62  4902.0 1976.27
  4907.4 1976.81  4914.1 1976.29  4921.8 1973.46  4922.3 1972.96  4928.0 1973.46
  4931.6 1975.97  4937.0 1973.72  4946.4 1977.02  4997.6 1973.80  5036.3 1974.03
  5064.9 1975.28  5131.0 1979.52  5173.0 1983.87  5332.3 1992.73  5360.8 1995.87
#Mann=4,-1,0
  4461.7   0.045       0  4616.8    0.07       0  4921.8    0.07       0
  4928.0    0.07       0
Bank Sta=4921.8,4928
Exp/Cntr=0.3,0.1

Type RM Length L Ch R = 1,4059,445,445,445
BEGIN DESCRIPTION:
Plum Creek Trib6 7.0
END DESCRIPTION:
XS GIS Cut Line= 3
      1395054.98      6924237.97      1394655.00      6923738.00
      1394405.03      6923638.01
#Sta/Elev= 30
  4355.4 1989.54  4447.4 1986.57  4732.3 1982.94  4810.8 1981.25  4874.8 1980.84
  4903.6 1979.09  4910.0 1978.05  4918.0 1978.25  4924.4 1977.33  4938.8 1976.89
  4967.7 1973.09  5005.1 1973.17  5007.1 1972.64  5007.6 1972.14  5013.4 1972.14
  5013.9 1972.64  5028.0 1972.98  5081.8 1976.54  5094.0 1978.50  5103.4 1980.95
  5118.2 1982.80  5142.4 1984.94  5147.8 1984.66  5172.0 1985.92  5196.3 1989.03
  5201.7 1988.80  5220.5 1990.64  5225.9 1990.44  5250.1 1994.35  5264.9 1994.99
#Mann=3,-1,0
  4355.4    0.07       0  5007.1    0.07       0  5013.9    0.07       0
Bank Sta=5007.1,5013.9
Exp/Cntr=0.3,0.1

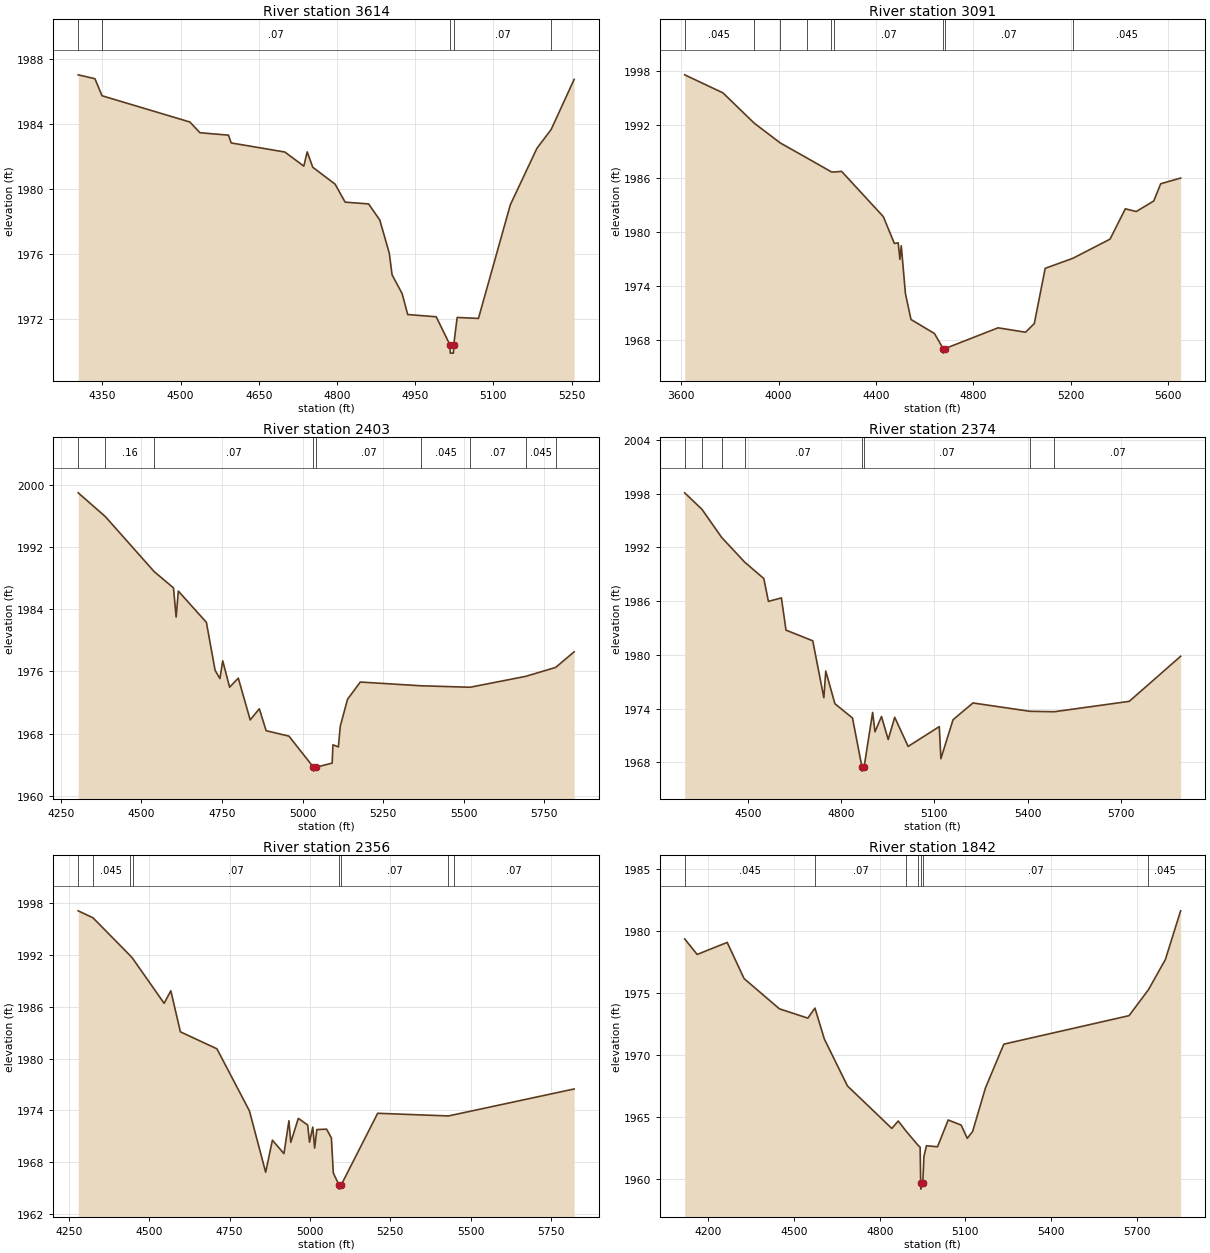
Type RM Length L Ch R = 1,3614,523,523,523
BEGIN DESCRIPTION:
Plum Creek Trib6 6.0
END DESCRIPTION:
XS GIS Cut Line= 3
      1395154.99      6924037.98      1394905.00      6923388.00
      1394654.95      6923337.99
#Sta/Elev= 30
  4303.6 1987.04  4335.7 1986.80  4349.3 1985.75  4517.9 1984.13  4537.1 1983.47
  4591.8 1983.32  4597.1 1982.84  4700.0 1982.28  4736.4 1981.41  4742.9 1982.29
  4753.6 1981.34  4796.4 1980.30  4815.7 1979.19  4860.7 1979.08  4882.1 1978.09
  4900.4 1976.04  4905.7 1974.71  4925.0 1973.55  4935.7 1972.26  4990.4 1972.12
  5016.9 1970.38  5017.4 1969.88  5023.4 1969.88  5023.9 1970.38  5030.6 1972.08
  5071.4 1972.02  5132.6 1979.03  5183.6 1982.51  5210.9 1983.67  5255.0 1986.76
#Mann=5,-1,0
  4303.6   0.045       0  4349.3    0.07       0  5016.9    0.07       0
  5023.9    0.07       0  5210.9   0.045       0
Bank Sta=5016.9,5023.9
Exp/Cntr=0.3,0.1

Type RM Length L Ch R = 1,3091,688,688,688
BEGIN DESCRIPTION:
Plum Creek Trib6 5.0
END DESCRIPTION:
XS GIS Cut Line= 3
      1395909.60      6924340.35      1395315.70      6923088.70
      1394948.88      6922550.28
#Sta/Elev= 30
  3614.6 1997.55  3771.8 1995.54  3900.0 1992.17  4007.2 1989.96  4116.5 1988.29
  4216.8 1986.74  4228.1 1986.72  4259.2 1986.79  4430.4 1981.75  4475.9 1978.76
  4491.6 1978.83  4498.6 1976.99  4504.2 1978.50  4521.4 1973.16  4544.1 1970.29
  4640.6 1968.72  4676.3 1967.04  4676.8 1966.54  4683.3 1967.04  4901.7 1969.36
  5014.6 1968.87  5050.5 1969.83  5095.3 1975.99  5208.4 1977.10  5361.6 1979.24
  5424.5 1982.62  5469.3 1982.32  5541.1 1983.49  5569.6 1985.41  5651.5 1986.05
#Mann=9,-1,0
  3614.6   0.045       0  3900.0    0.07       0  4007.2   0.045       0
  4116.5    0.07       0  4216.8    0.16       0  4228.1    0.07       0
  4676.3    0.07       0  4683.3    0.07       0  5208.4   0.045       0
Bank Sta=4676.3,4683.3
Exp/Cntr=0.3,0.1

Type RM Length L Ch R = 1,2403,29,29,29
BEGIN DESCRIPTION:
Mapping XS 9287efcb
END DESCRIPTION:
XS GIS Cut Line= 6
      1396263.76      6923750.06      1395979.04      6923326.45
      1395854.04      6923194.50      1395763.76      6923163.25
      1395670.01      6923118.12      1395235.95      6922638.92
#Sta/Elev= 30
  4304.0 1998.96  4388.0 1995.91  4539.5 1988.83  4599.6 1986.73  4607.7 1982.98
  4614.6 1986.32  4701.6 1982.30  4728.6 1976.13  4743.6 1975.06  4752.3 1977.35
  4773.6 1973.96  4800.6 1975.12  4837.5 1969.75  4865.8 1971.18  4886.9 1968.36
  4957.7 1967.66  5033.8 1963.66  5034.3 1963.16  5041.1 1963.66  5091.7 1964.19
  5094.1 1966.54  5111.1 1966.28  5116.7 1968.91  5139.3 1972.40  5179.0 1974.62
  5366.8 1974.14  5519.6 1973.95  5691.9 1975.35  5785.0 1976.50  5842.3 1978.51
#Mann=9,-1,0
  4304.0    0.07       0  4388.0    0.16       0  4539.5    0.07       0
  5033.8    0.07       0  5041.1    0.07       0  5366.8   0.045       0
  5519.6    0.07       0  5691.9   0.045       0  5785.0    0.07       0
Bank Sta=5033.8,5041.1
Exp/Cntr=0.3,0.1

Type RM Length L Ch R = 1,2374,18,18,18
BEGIN DESCRIPTION:
Mapping XS 5fb14954
END DESCRIPTION:
XS GIS Cut Line= 6
      1396298.46      6923729.19      1395965.15      6923257.00
      1395867.93      6923170.20      1395801.96      6923128.53
      1395715.15      6923114.64      1395232.48      6922576.42
#Sta/Elev= 30
  4295.7 1998.09  4351.4 1996.25  4414.6 1993.12  4489.0 1990.35  4550.6 1988.52
  4565.4 1985.97  4607.2 1986.36  4622.0 1982.76  4708.2 1981.57  4743.9 1975.22
  4750.1 1978.19  4779.6 1974.54  4836.2 1972.95  4866.4 1967.52  4866.9 1967.02
  4873.7 1967.52  4901.0 1973.57  4908.6 1971.41  4929.5 1973.12  4951.2 1970.55
  4972.1 1973.03  5015.4 1969.78  5115.7 1971.99  5120.8 1968.41  5160.0 1972.76
  5224.2 1974.63  5407.3 1973.70  5485.8 1973.65  5727.4 1974.81  5892.9 1979.84
#Mann=8,-1,0
  4295.7    0.07       0  4351.4   0.045       0  4414.6    0.16       0
  4489.0    0.07       0  4866.4    0.07       0  4873.7    0.07       0
  5407.3   0.045       0  5485.8    0.07       0
Bank Sta=4866.4,4873.7
Exp/Cntr=0.3,0.1

Type RM Length L Ch R = 1,2356,514,514,514
BEGIN DESCRIPTION:
Mapping XS b6b7a430
END DESCRIPTION:
XS GIS Cut Line= 6
      1396322.79      6923722.28      1395965.15      6923208.39
      1395847.09      6923138.95      1395795.01      6923104.23
      1395746.40      6923097.28      1395291.57      6922607.73
#Sta/Elev= 30
  4279.3 1997.14  4325.3 1996.33  4439.8 1991.99  4448.7 1991.62  4546.6 1986.41
  4567.5 1987.86  4597.2 1983.10  4710.9 1981.13  4811.9 1973.94  4862.5 1966.81
  4883.5 1970.53  4919.4 1968.97  4934.9 1972.78  4940.7 1970.28  4964.2 1973.06
  4993.2 1972.29  4999.0 1970.30  5009.2 1972.05  5014.9 1969.62  5021.8 1971.76
  5052.0 1971.81  5067.0 1970.79  5073.0 1966.72  5090.4 1965.35  5090.9 1964.85
  5097.7 1965.35  5211.0 1973.65  5431.0 1973.34  5449.8 1973.49  5822.3 1976.47
#Mann=8,-1,0
  4279.3    0.07       0  4325.3   0.045       0  4439.8    0.16       0
  4448.7    0.07       0  5090.4    0.07       0  5097.7    0.07       0
  5431.0   0.045       0  5449.8    0.07       0
Bank Sta=5090.4,5097.7
Exp/Cntr=0.3,0.1

Type RM Length L Ch R = 1,1842,398,398,398
BEGIN DESCRIPTION:
Plum Creek Trib6 2.0
END DESCRIPTION:
XS GIS Cut Line= 3
      1396840.12      6923142.40      1396055.00      6922738.00
      1395255.05      6922438.02
#Sta/Elev= 30
  4116.8 1979.35  4160.6 1978.10  4265.8 1979.07  4325.0 1976.15  4448.8 1973.71
  4548.3 1972.96  4573.2 1973.77  4606.2 1971.27  4687.0 1967.49  4842.5 1964.06
  4865.0 1964.66  4891.5 1963.87  4932.9 1962.74  4941.7 1962.54  4943.7 1959.66
  4944.2 1959.16  4951.0 1959.66  4955.0 1961.80  4963.9 1962.66  5002.6 1962.58
  5040.0 1964.74  5085.4 1964.33  5106.7 1963.26  5125.4 1963.80  5170.8 1967.34
  5234.9 1970.86  5673.7 1973.16  5741.7 1975.26  5800.9 1977.69  5854.3 1981.62
#Mann=7,-1,0
  4116.8   0.045       0  4573.2    0.07       0  4891.5   0.045       0
  4932.9    0.07       0  4943.7    0.07       0  4951.0    0.07       0
  5741.7   0.045       0
Bank Sta=4943.7,4951
Exp/Cntr=0.3,0.1

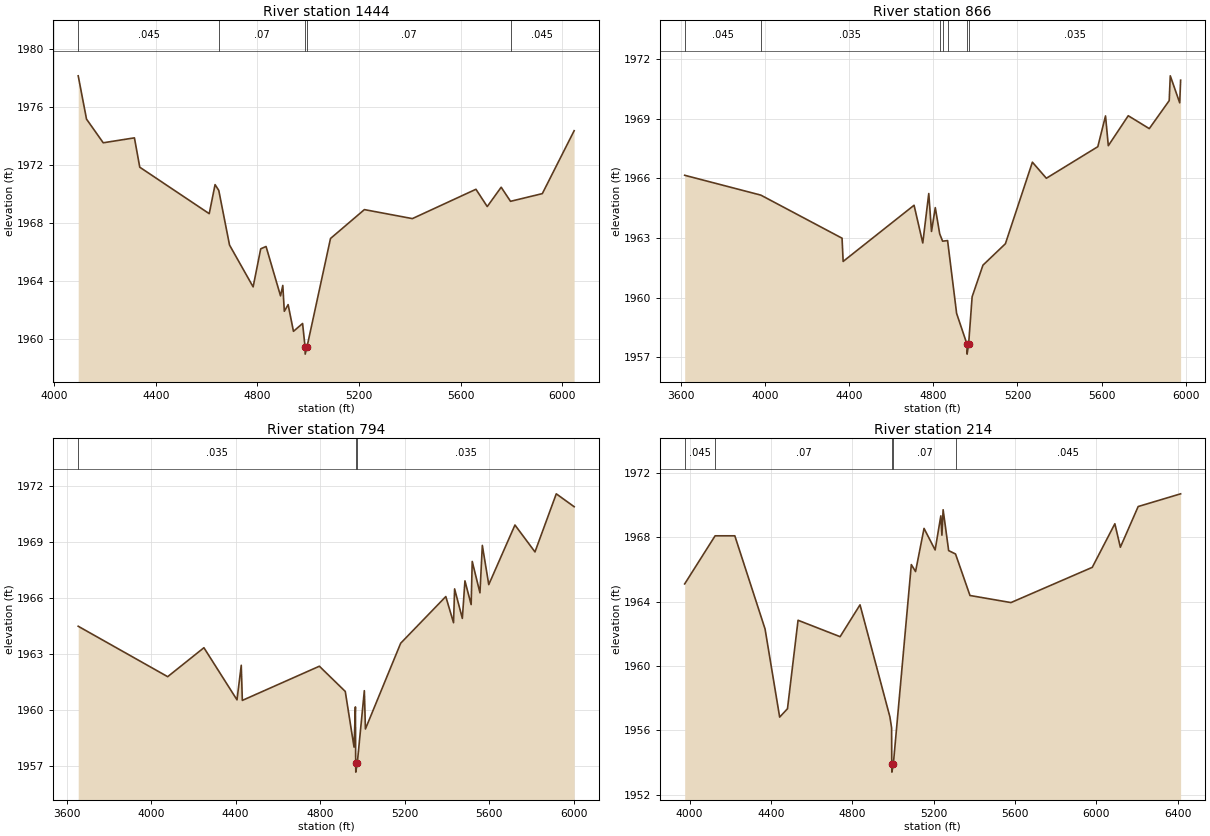
Type RM Length L Ch R = 1,1444,578,578,578
BEGIN DESCRIPTION:
Mapping XS 80986638
END DESCRIPTION:
XS GIS Cut Line= 3
      1397051.98      6922947.99      1396308.90      6922444.50
      1395368.94      6921965.86
#Sta/Elev= 30
  4094.7 1978.14  4127.4 1975.16  4193.2 1973.53  4316.0 1973.87  4337.0 1971.85
  4610.5 1968.65  4633.5 1970.65  4648.1 1970.25  4690.4 1966.49  4783.3 1963.61
  4813.2 1966.23  4834.2 1966.39  4891.2 1962.99  4900.1 1963.71  4906.1 1961.93
  4921.1 1962.39  4942.1 1960.55  4978.0 1961.09  4987.8 1959.48  4988.3 1958.98
  4995.4 1959.48  5087.9 1966.94  5221.3 1968.93  5410.3 1968.31  5660.5 1970.33
  5705.0 1969.14  5759.8 1970.47  5796.7 1969.50  5921.8 1970.03  6047.1 1974.36
#Mann=5,-1,0
  4094.7   0.045       0  4648.1    0.07       0  4987.8    0.07       0
  4995.4    0.07       0  5796.7   0.045       0
Bank Sta=4987.8,4995.4
Exp/Cntr=0.3,0.1

Type RM Length L Ch R = 1,866,72,72,72
BEGIN DESCRIPTION:
Mapping XS a6cdd3fe
END DESCRIPTION:
XS GIS Cut Line= 3
      1397860.96      6922333.39      1396510.29      6922000.06
      1395565.80      6921802.13
#Sta/Elev= 30
  3619.1 1966.16  3981.0 1965.16  4366.8 1962.99  4372.0 1961.82  4708.9 1964.65
  4750.3 1962.75  4778.8 1965.24  4791.8 1963.33  4809.7 1964.53  4830.7 1963.21
  4844.6 1962.84  4868.2 1962.87  4911.1 1959.20  4960.4 1957.65  4960.9 1957.15
  4968.1 1957.65  4984.8 1960.04  5036.1 1961.63  5142.8 1962.71  5271.1 1966.82
  5337.4 1966.01  5581.9 1967.60  5618.5 1969.15  5631.8 1967.65  5726.5 1969.16
  5826.4 1968.51  5921.1 1969.92  5926.2 1971.17  5971.0 1969.81  5975.3 1970.95
#Mann=7,-1,0
  3619.1   0.045       0  3981.0   0.035       0  4830.7   0.045       0
  4844.6    0.07       0  4868.2   0.035       0  4960.4   0.035       0
  4968.1   0.035       0
Bank Sta=4960.4,4968.1
Exp/Cntr=0.3,0.1

Type RM Length L Ch R = 1,794,580,580,580
BEGIN DESCRIPTION:
Mapping XS 56fe4974
END DESCRIPTION:
XS GIS Cut Line= 3
      1397857.48      6922246.58      1396555.43      6921947.98
      1395572.77      6921708.39
#Sta/Elev= 30
  3655.2 1964.50  4078.7 1961.80  4250.2 1963.35  4406.7 1960.56  4426.9 1962.41
  4432.0 1960.53  4796.6 1962.36  4919.2 1961.01  4960.7 1958.03  4967.2 1960.18
  4968.5 1957.19  4969.0 1956.69  4976.2 1957.19  5009.5 1961.05  5014.6 1959.00
  5181.4 1963.59  5395.0 1966.09  5431.6 1964.69  5436.7 1966.50  5473.3 1964.92
  5485.6 1966.93  5515.0 1965.66  5520.1 1967.97  5556.7 1966.29  5567.9 1968.83
  5598.4 1966.73  5722.3 1969.92  5817.1 1968.48  5917.9 1971.59  6002.5 1970.90
#Mann=3,-1,0
  3655.2   0.035       0  4968.5   0.035       0  4976.2   0.035       0
Bank Sta=4968.5,4976.2
Exp/Cntr=0.3,0.1

Type RM Length L Ch R = 1,214,0,0,0
BEGIN DESCRIPTION:
Plum Creek Trib6 1.0
END DESCRIPTION:
XS GIS Cut Line= 3
      1397638.74      6921937.55      1396731.61      6921461.18
      1395374.84      6921059.08
#Sta/Elev= 30
  3975.4 1965.10  4125.1 1968.09  4222.1 1968.09  4370.8 1962.30  4442.7 1956.82
  4481.1 1957.34  4533.1 1962.84  4740.0 1961.82  4838.0 1963.80  4984.9 1956.84
  4993.3 1956.16  4994.2 1953.90  4994.7 1953.40  5001.9 1953.90  5090.3 1966.30
  5111.2 1965.87  5152.9 1968.55  5207.5 1967.21  5235.5 1969.33  5240.8 1968.13
  5246.8 1969.71  5274.0 1967.17  5307.8 1966.96  5378.9 1964.38  5580.5 1963.94
  5980.5 1966.13  6091.6 1968.84  6118.7 1967.38  6206.3 1969.91  6415.1 1970.70
#Mann=5,-1,0
  3975.4   0.045       0  4125.1    0.07       0  4994.2    0.07       0
  5001.9    0.07       0  5307.8   0.045       0
Bank Sta=4994.2,5001.9
Exp/Cntr=0.3,0.1

Chan Stop Cuts=-1