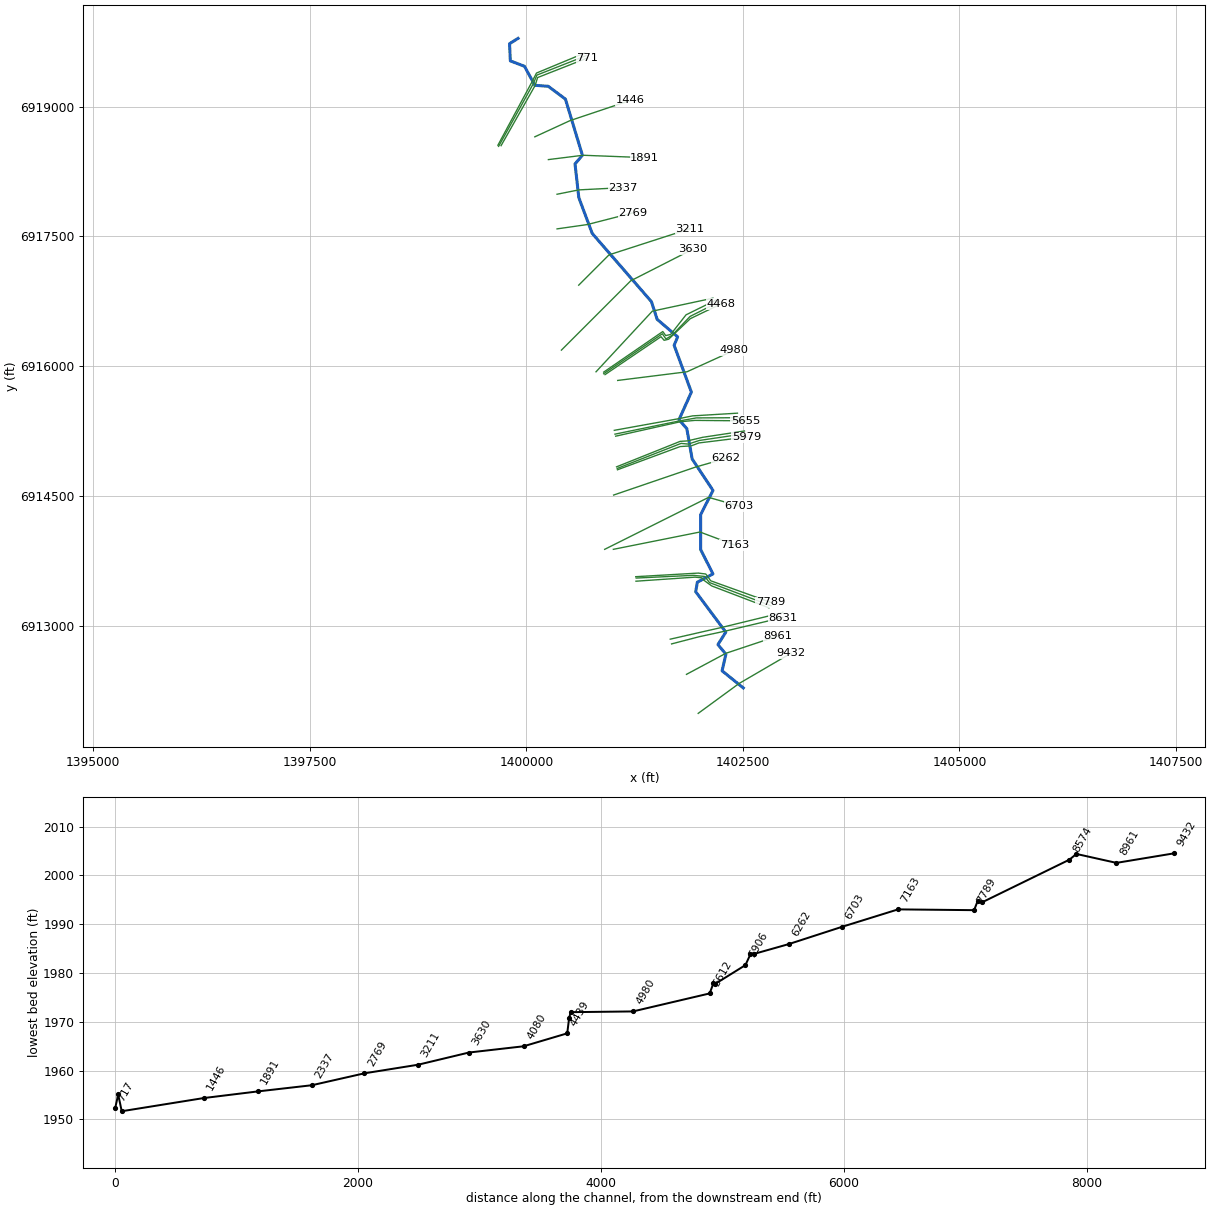
--- Plum Creek Trib7.prj (project) ---

Proj Title=Plum Creek Trib7 Base Level Engineering
Current Plan=p01
Default Exp/Contr=0.3,0.1
English Units
Geom File=g01
Flow File=f01
Plan File=p01
Y Axis Title=Elevation
X Axis Title(PF)=Main Channel Distance
X Axis Title(XS)=Station
BEGIN DESCRIPTION:
Plum Creek Trib7
END DESCRIPTION:
DSS Export Rating Curves= 0
DSS Export Rating Curve Sorted= 0
DSS Export Volume Flow Curves= 0
DXF OffsetX= 0
DXF OffsetY= 0
DXF ScaleX= 1
DXF ScaleY= 10

--- Plum Creek Trib7.p01 (plan) ---

Plan Title=Multiple Run
Short Identifier=Multiple
Geom File=g01
Flow File=f01
Subcritical Flow
K Sum by GR= 0
Std Step Tol= 0.01
Critical Tol= 0.01
Num of Std Step Trials= 20
Max Error Tol= 0.3
Flow Tol Ratio= 0.001
Split Flow NTrial= 30
Split Flow Tol= 0.02
Split Flow Ratio= 0.02
Log Output Level= 0
Friction Slope Method= 1
Unsteady Friction Slope Method= 2
Unsteady Bridges Friction Slope Method= 1
Parabolic Critical Depth
Global Vel Dist=  1 , 1 , 1
Global Log Level= 0
CheckData=True
Encroach Param= -1, 0, 0, 0
BEGIN DESCRIPTION:
Multiple Run
END DESCRIPTION:

--- Plum Creek Trib7.f01 (steady flow) ---

Flow Title=Multiple
Number of Profiles=7
Profile Names=10-year,25-year,50-year,1pct_min,100-year,1pct_plu,500-year
River Rch & RM= Plum Creek Trib7,Reach-1,9432
     278     394     491     305     609    1214     945
River Rch & RM= Plum Creek Trib7,Reach-1,7854
     437     634     803     505    1008    2012    1611
River Rch & RM= Plum Creek Trib7,Reach-1,3630
     552     809    1032     653    1304    2601    2110
Boundary for River Rch & Prof#=Plum Creek Trib7,Reach-1,1
Up Type=0
Dn Type=3
Dn Slope=0.005
Boundary for River Rch & Prof#=Plum Creek Trib7,Reach-1,2
Up Type=0
Dn Type=3
Dn Slope=0.005
Boundary for River Rch & Prof#=Plum Creek Trib7,Reach-1,3
Up Type=0
Dn Type=3
Dn Slope=0.005
Boundary for River Rch & Prof#=Plum Creek Trib7,Reach-1,4
Up Type=0
Dn Type=3
Dn Slope=0.005
Boundary for River Rch & Prof#=Plum Creek Trib7,Reach-1,5
Up Type=0
Dn Type=3
Dn Slope=0.005
Boundary for River Rch & Prof#=Plum Creek Trib7,Reach-1,6
Up Type=0
Dn Type=3
Dn Slope=0.005
Boundary for River Rch & Prof#=Plum Creek Trib7,Reach-1,7
Up Type=0
Dn Type=3
Dn Slope=0.005

--- Plum Creek Trib7.g01 (geometry) ---

Geom Title=Existing Conditions
Program Version=4.10

River Reach=Plum Creek Trib7,Reach-1
Reach XY= 30
        1402505.        6912288.      1402260.39      6912485.56
      1402304.39      6912677.38       1402212.1        6912788.
      1402303.24      6912931.87      1401955.93      6913398.49
      1401974.42      6913508.54      1402154.78        6913604.
      1402013.05      6913884.68      1402012.53      6914288.01
       1402155.4      6914567.87      1401914.58      6914931.45
      1401852.92      6915282.14      1401762.81      6915384.59
      1401905.73      6915703.06      1401706.67      6916244.05
      1401747.18      6916341.41      1401510.59      6916543.61
      1401444.48      6916747.79      1400760.83       6917535.7
      1400606.22       6917948.5      1400562.34       6918338.1
      1400647.66       6918437.9      1400451.47      6919086.55
      1400253.44      6919234.24      1400098.52       6919245.7
       1399978.9      6919465.28      1399815.32      6919527.83
      1399806.54      6919726.29        1399905.        6919788.

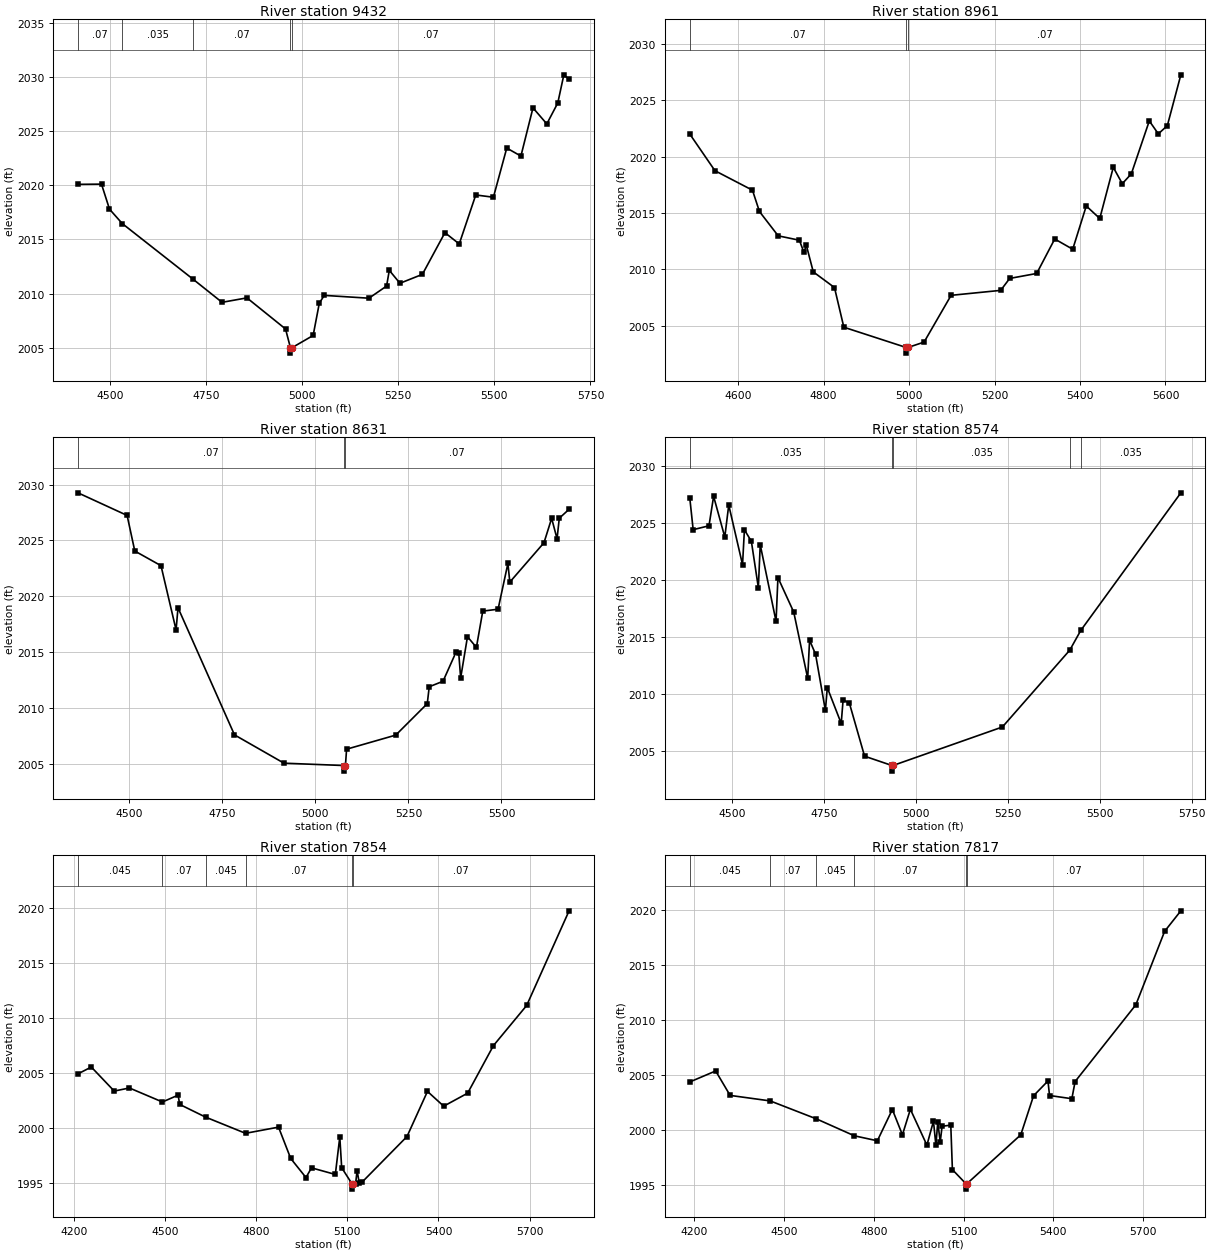
Type RM Length L Ch R = 1 ,9432    ,471,471,471
BEGIN DESCRIPTION:
Plum Creek Trib7 21.0
END DESCRIPTION:
XS GIS Cut Line= 3
       1401984.6      6911993.97        1402455.        6912338.
        1403055.        6912688.
#Sta/Elev= 30
  4416.9 2020.08  4478.1  2020.1  4498.9 2017.79  4532.1 2016.46  4715.7 2011.34
  4791.6 2009.19  4856.4  2009.6  4956.8 2006.73  4969.5    2005  4969.7  2004.5
  4973.5    2005  5028.6 2006.13  5044.7 2009.12  5057.6 2009.83  5173.7 2009.57
  5219.6 2010.69  5226.7 2012.14  5254.4 2010.95  5312.7 2011.77  5371.4 2015.62
  5408.6 2014.58  5451.6  2019.1  5497.5 2018.89  5532.2 2023.43    5569 2022.69
  5600.4 2027.14  5636.4 2025.66  5664.9 2027.59  5680.7 2030.19  5694.3 2029.77
#Mann= 5 ,-1 , 0
  4416.9     .07       0  4532.1    .035       0  4715.7     .07       0
  4969.5     .07       0  4973.5     .07       0
Bank Sta=4969.5,4973.5
XS Rating Curve= 0 ,0
Exp/Cntr=0.3,0.1

Type RM Length L Ch R = 1 ,8961    ,330,330,330
BEGIN DESCRIPTION:
Plum Creek Trib7 20.0
END DESCRIPTION:
XS GIS Cut Line= 3
      1401849.21      6912444.51        1402305.        6912688.
      1402904.99        6912888.
#Sta/Elev= 30
  4486.8 2022.01  4545.8 2018.75  4633.6 2017.02  4649.9 2015.13  4693.8 2012.97
  4743.4 2012.58    4754  2011.5  4759.6 2012.14  4775.9 2009.77  4825.5 2008.38
  4847.4 2004.86  4993.4 2003.06  4993.7 2002.56  4997.4 2003.06  5035.2 2003.54
  5098.4 2007.69  5214.4 2008.13  5235.5 2009.19  5298.7 2009.63  5340.9 2012.69
    5383 2011.78  5414.7 2015.62  5446.3 2014.51  5477.9 2019.05    5499  2017.6
  5520.1 2018.47  5562.2 2023.17  5583.3 2022.02  5604.4 2022.75    5636 2027.26
#Mann= 3 ,-1 , 0
  4486.8     .07       0  4993.4     .07       0  4997.4     .07       0
Bank Sta=4993.4,4997.4
XS Rating Curve= 0 ,0
Exp/Cntr=0.3,0.1

Type RM Length L Ch R = 1 ,8631    ,57,57,57
BEGIN DESCRIPTION:
Mapping XS d47adef9
END DESCRIPTION:
XS GIS Cut Line= 4
      1401677.27      6912796.05      1401997.61      6912879.39
       1402299.7      6912944.49      1402960.59      6913100.61
#Sta/Elev= 30
  4362.5 2029.26  4494.5 2027.24  4515.1 2024.06  4585.5 2022.75    4626 2017.01
  4631.2 2018.99  4782.9 2007.63  4915.9  2005.1  5076.9 2004.89  5077.1 2004.39
  5080.9 2004.89    5084 2006.35  5216.1 2007.61  5300.7 2010.42    5306 2011.93
    5343 2012.42  5377.9 2015.02  5385.3 2014.92  5390.4 2012.72  5408.7  2016.4
  5432.7 2015.45  5449.8 2018.69  5490.9 2018.86  5517.3 2022.95  5522.4 2021.28
  5614.2  2024.8  5634.8 2026.98  5649.3 2025.15  5655.3 2026.99  5681.6 2027.79
#Mann= 3 ,-1 , 0
  4362.5     .07       0  5076.9     .07       0  5080.9     .07       0
Bank Sta=5076.9,5080.9
XS Rating Curve= 0 ,0
Exp/Cntr=0.3,0.1

Type RM Length L Ch R = 1 ,8574    ,720,720,720
BEGIN DESCRIPTION:
Mapping XS bfdee9ef
END DESCRIPTION:
XS GIS Cut Line= 3
      1401661.68      6912850.74      1402255.43      6912986.16
      1402960.62       6913157.9
#Sta/Elev= 30
  4385.9 2027.21  4395.2 2024.39  4438.2 2024.73  4450.8 2027.31  4481.2 2023.74
  4491.9 2026.55  4529.4 2021.32  4534.5 2024.38  4553.4 2023.37  4572.4 2019.31
  4577.5 2023.07  4620.5 2016.35  4625.6 2020.19  4668.6 2017.16  4706.5 2011.36
  4711.6  2014.7  4727.8 2013.48  4754.6 2008.54  4759.8 2010.54  4797.6  2007.4
  4802.8 2009.49  4820.1 2009.15  4861.1 2004.53  4934.9 2003.72  4935.1 2003.22
  4938.9 2003.72  5235.7 2007.09  5418.9 2013.83  5448.6 2015.55  5720.7 2027.62
#Mann= 5 ,-1 , 0
  4385.9    .035       0  4934.9    .035       0  4938.9    .035       0
  5418.9     .07       0  5448.6    .035       0
Bank Sta=4934.9,4938.9
XS Rating Curve= 0 ,0
Exp/Cntr=0.3,0.1

Type RM Length L Ch R = 1 ,7854    ,37,37,37
BEGIN DESCRIPTION:
Mapping XS 38d612cd
END DESCRIPTION:
XS GIS Cut Line= 6
      1401265.88      6913520.01      1401948.14      6913566.89
      1402026.26      6913559.07      1402047.09      6913533.03
      1402140.84      6913465.32      1402800.79       6913213.3
#Sta/Elev= 30
  4212.4 2004.92  4256.3 2005.54  4331.8 2003.36  4381.9 2003.64  4490.6 2002.37
  4542.3 2002.99  4547.5 2002.15  4632.7    2001  4764.4 1999.53  4873.1 2000.09
  4913.2 1997.25  4963.5 1995.52  4981.7  1996.4  5060.2  1995.8  5074.9  1999.2
  5081.1 1996.41  5114.7 1994.97  5114.9 1994.47  5118.7 1994.97    5127 1994.98
  5131.9 1996.15  5138.9 1995.04  5149.6 1995.14  5296.3 1999.24  5363.7 2003.33
  5417.2 2001.99  5496.1 2003.17    5581 2007.48  5690.5 2011.12  5830.2  2019.7
#Mann= 6 ,-1 , 0
  4212.4    .045       0  4490.6     .07       0  4632.7    .045       0
  4764.4     .07       0  5114.7     .07       0  5118.7     .07       0
Bank Sta=5114.7,5118.7
XS Rating Curve= 0 ,0
Exp/Cntr=0.3,0.1

Type RM Length L Ch R = 1 ,7817    ,28,28,28
BEGIN DESCRIPTION:
Mapping XS 0daba781
END DESCRIPTION:
XS GIS Cut Line= 5
      1401268.44      6913556.47      1401929.91      6913587.72
      1402060.11       6913574.7       1402114.8      6913504.39
      1402825.74      6913236.16
#Sta/Elev= 30
  4184.6  2004.4  4271.3  2005.4  4319.6 2003.18  4453.6 2002.68    4608 2001.05
  4735.2 1999.51  4811.9 1999.06    4862  2001.9  4895.7  1999.6  4922.3 2001.92
  4977.6 1998.66  4999.5 2000.84  5007.6 1998.66  5013.9 2000.75  5022.1 1998.96
  5028.4 2000.38  5057.4 2000.48  5062.8 1996.44  5107.7 1995.17    5108 1994.67
  5111.7 1995.17  5291.4  1999.6  5334.2 2003.15  5382.3 2004.49  5387.6 2003.17
  5462.2 2002.88  5473.1 2004.44  5676.2 2011.41  5772.4 2018.08  5826.6 2019.94
#Mann= 6 ,-1 , 0
  4184.6    .045       0  4453.6     .07       0    4608    .045       0
  4735.2     .07       0  5107.7     .07       0  5111.7     .07       0
Bank Sta=5107.7,5111.7
XS Rating Curve= 0 ,0
Exp/Cntr=0.3,0.1

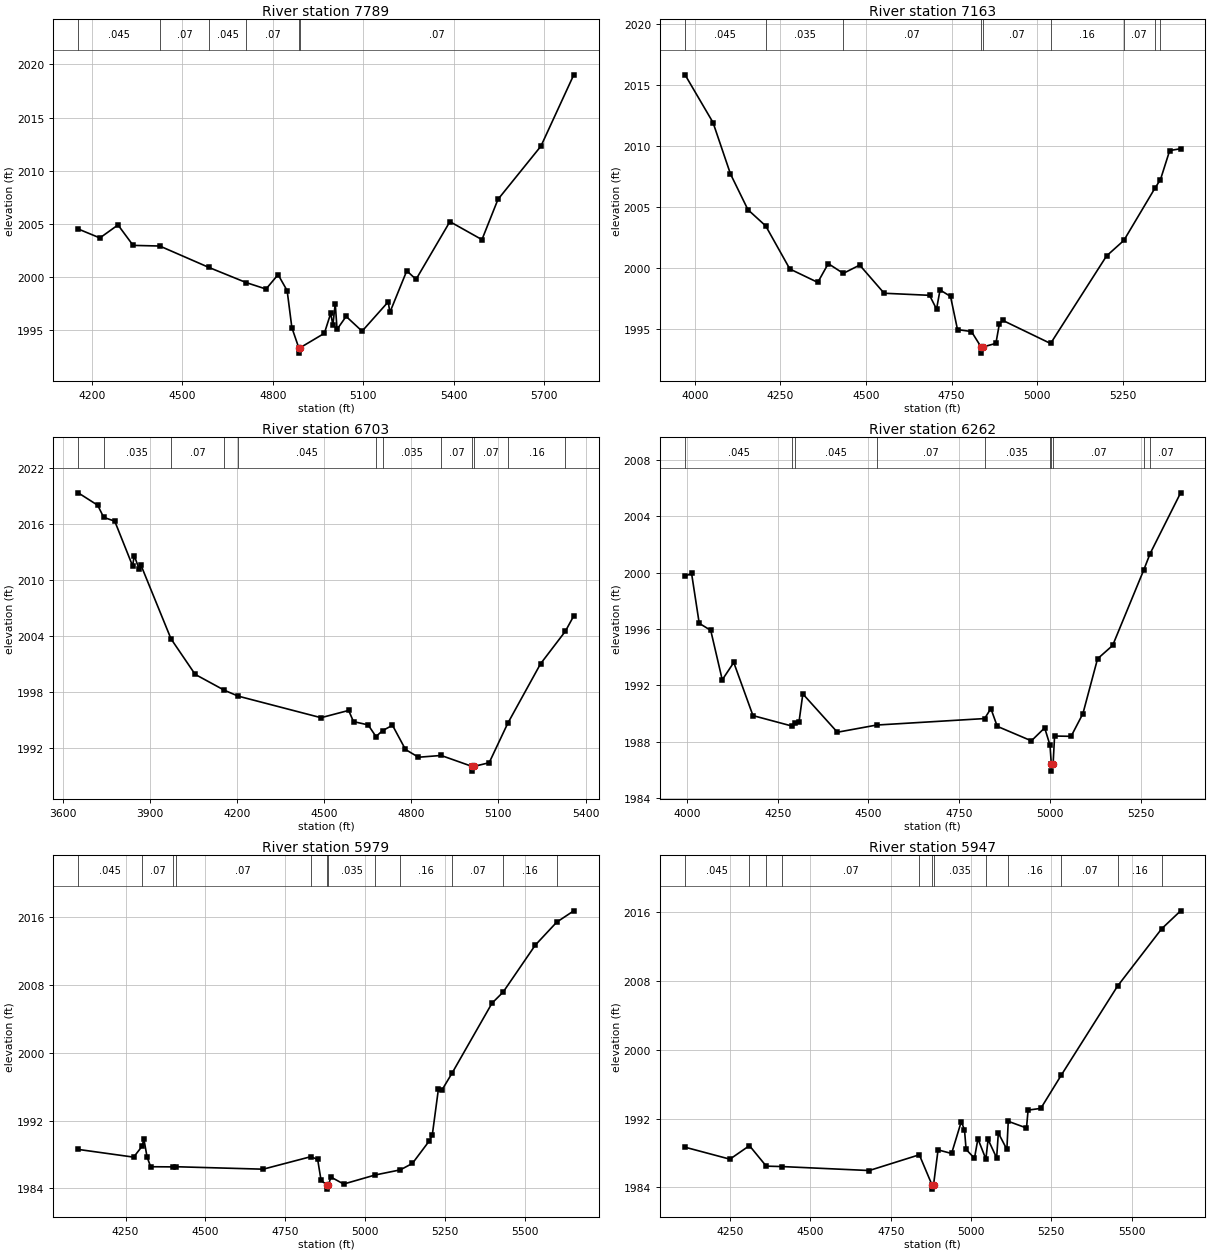
Type RM Length L Ch R = 1 ,7789    ,626,626,626
BEGIN DESCRIPTION:
Mapping XS 4102e502
END DESCRIPTION:
XS GIS Cut Line= 6
      1401263.25       6913572.1      1401984.59      6913613.76
      1402070.53      6913603.35      1402091.36      6913579.91
      1402127.82      6913525.22      1402821.54      6913275.79
#Sta/Elev= 30
  4154.3 2004.53  4226.2 2003.69  4286.3 2004.91  4336.4 2002.99  4424.7 2002.93
  4587.7 2000.92    4712 1999.49  4777.1 1998.89  4817.2 2000.24  4847.2 1998.74
  4862.9 1995.26  4885.8 1993.37    4886 1992.87  4889.8 1993.37  4970.6 1994.73
  4991.7 1996.61  4998.9 1995.49  5006.7 1997.53  5012.7  1995.1  5042.8 1996.32
  5095.7 1994.93  5182.5 1997.69  5187.8 1996.69  5243.9  2000.6  5274.7  1999.8
  5386.9 2005.22  5493.2 2003.53  5546.3 2007.31  5688.8 2012.31  5797.7 2019.01
#Mann= 6 ,-1 , 0
  4154.3    .045       0  4424.7     .07       0  4587.7    .045       0
    4712     .07       0  4885.8     .07       0  4889.8     .07       0
Bank Sta=4885.8,4889.8
XS Rating Curve= 0 ,0
Exp/Cntr=0.3,0.1

Type RM Length L Ch R = 1 ,7163    ,460,460,460
BEGIN DESCRIPTION:
Plum Creek Trib7 16.0
END DESCRIPTION:
XS GIS Cut Line= 3
      1401004.99        6913888.        1402005.        6914088.
      1402404.99        6913938.
#Sta/Elev= 30
  3971.6 2015.85  4053.2 2011.94  4104.2 2007.72  4155.2 2004.79  4207.1 2003.46
  4277.5 1999.93  4359.1 1998.83  4389.7 2000.37  4433.6 1999.57  4481.5 2000.25
  4552.9 1997.94  4685.5 1997.77  4705.9 1996.64  4716.1 1998.21  4746.7 1997.68
  4767.1 1994.96  4807.8  1994.8    4836 1993.53  4836.4 1993.03  4840.8 1993.53
  4879.2 1993.83  4889.4 1995.44  4899.6 1995.71  5038.9 1993.82  5202.3    2001
  5252.8 2002.27    5343 2006.53  5359.7 2007.26  5386.6 2009.64  5418.6 2009.79
#Mann= 9 ,-1 , 0
  3971.6    .045       0  4207.1    .035       0  4433.6     .07       0
    4836     .07       0  4840.8     .07       0  5038.9     .16       0
  5252.8     .07       0    5343     .16       0  5359.7     .07       0
Bank Sta=4836,4840.8
XS Rating Curve= 0 ,0
Exp/Cntr=0.3,0.1

Type RM Length L Ch R = 1 ,6703    ,441,441,441
BEGIN DESCRIPTION:
Plum Creek Trib7 15.0
END DESCRIPTION:
XS GIS Cut Line= 3
      1400904.97      6913887.98        1402105.        6914488.
      1402455.02      6914387.99
#Sta/Elev= 30
  3653.7 2019.32  3720.8 2017.99  3741.4 2016.69  3779.5 2016.28    3841 2011.48
  3846.6 2012.58  3863.4 2011.15    3869 2011.62  3973.1 2003.66  4056.2 1999.85
    4157 1998.14  4204.8 1997.51  4489.5  1995.2  4584.5 1995.98  4601.3 1994.78
  4651.6 1994.43  4678.6 1993.18  4701.3 1993.81  4735.4 1994.39  4780.2 1991.79
  4824.9 1990.96  4902.9 1991.15  5009.9 1989.97  5010.2 1989.47  5014.7 1989.97
  5068.2 1990.37  5132.2  1994.6    5245 2000.98  5330.2 2004.46  5359.4 2006.12
#Mann= 12 ,-1 , 0
  3653.7    .045       0  3741.4    .035       0  3973.1     .07       0
    4157    .035       0  4204.8    .045       0  4678.6     .07       0
  4701.3    .035       0  4902.9     .07       0  5009.9     .07       0
  5014.7     .07       0  5132.2     .16       0  5330.2     .07       0
Bank Sta=5009.9,5014.7
XS Rating Curve= 0 ,0
Exp/Cntr=0.3,0.1

Type RM Length L Ch R = 1 ,6262    ,283,283,283
BEGIN DESCRIPTION:
Plum Creek Trib7 14.0
END DESCRIPTION:
XS GIS Cut Line= 3
      1401008.05      6914514.81        1401955.        6914838.
      1402305.01        6914938.
#Sta/Elev= 30
  3995.1 1999.73    4013 1999.95  4034.1  1996.4  4065.8  1995.9  4097.5 1992.39
  4129.2 1993.62  4182.1 1989.85  4290.8  1989.1  4298.5 1989.29  4308.9 1989.41
  4319.4 1991.39  4414.5 1988.67  4522.6 1989.18  4819.9 1989.64  4837.2 1990.35
  4854.7 1989.09  4948.7 1988.06  4985.3 1988.98    5000 1987.75  5003.6 1986.41
    5004 1985.91  5008.5 1986.41  5012.6  1988.4  5058.1 1988.38  5090.6 1989.99
  5130.9 1993.88  5172.5 1994.83  5257.9 2000.17  5275.5 2001.34  5359.7 2005.66
#Mann= 10 ,-1 , 0
  3995.1    .045       0  4290.8     .07       0  4298.5    .045       0
  4522.6     .07       0  4819.9    .035       0    5000     .07       0
  5003.6    .035       0  5008.5     .07       0  5257.9     .16       0
  5275.5     .07       0
Bank Sta=5003.6,5008.5
XS Rating Curve= 0 ,0
Exp/Cntr=0.3,0.1

Type RM Length L Ch R = 1 ,5979    ,32,32,32
BEGIN DESCRIPTION:
Mapping XS 8a6a311b
END DESCRIPTION:
XS GIS Cut Line= 5
      1401052.28      6914806.46      1401776.26       6915074.7
      1401903.86      6915082.51      1401992.41      6915116.37
      1402544.46      6915184.07
#Sta/Elev= 30
  4101.8  1988.6  4275.3 1987.69  4301.9 1988.98  4307.3 1989.83  4317.4  1987.7
  4328.6 1986.56  4399.5 1986.54  4407.4 1986.56  4680.6 1986.27  4829.5 1987.74
  4851.2 1987.42  4861.9 1984.94  4880.2 1984.42  4880.5 1983.92  4885.1 1984.42
  4892.6 1985.34  4932.7 1984.52  5031.5 1985.59  5109.8 1986.19  5147.7 1986.95
  5199.9 1989.57  5209.9 1990.29  5229.1 1995.71  5240.2  1995.6  5272.1 1997.61
  5396.9 2005.84  5431.6 2007.14  5532.3 2012.68  5599.5 2015.39  5652.7 2016.72
#Mann= 12 ,-1 , 0
  4101.8    .045       0  4301.9     .07       0  4399.5    .045       0
  4407.4     .07       0  4829.5    .035       0  4880.2    .035       0
  4885.1    .035       0  5031.5     .07       0  5109.8     .16       0
  5272.1     .07       0  5431.6     .16       0  5599.5     .07       0
Bank Sta=4880.2,4885.1
XS Rating Curve= 0 ,0
Exp/Cntr=0.3,0.1

Type RM Length L Ch R = 1 ,5947    ,41,41,41
BEGIN DESCRIPTION:
Mapping XS 29832bb1
END DESCRIPTION:
XS GIS Cut Line= 5
      1401049.72       6914822.1      1401786.68      6915111.16
      1401870.01      6915103.35      1401997.61      6915145.01
      1402525.82      6915223.07
#Sta/Elev= 30
  4109.4 1988.68  4249.1 1987.29  4309.9 1988.86  4362.3 1986.48  4412.3 1986.43
    4683 1985.97    4839  1987.8  4878.4 1984.31  4878.8 1983.81  4883.3 1984.31
  4897.4 1988.37  4939.5 1987.95  4969.6 1991.64  4979.7 1990.71  4984.7 1988.42
  5010.8  1987.4  5021.5 1989.66  5046.3  1987.3  5053.2 1989.58  5079.8 1987.44
  5085.1 1990.33  5111.7 1988.43    5116 1991.69  5172.8 1990.91  5177.8 1992.99
  5217.4 1993.19  5281.8 1997.09  5456.3 2007.39  5593.7 2014.05  5652.9 2016.14
#Mann= 12 ,-1 , 0
  4109.4    .045       0  4309.9     .07       0  4362.3    .045       0
  4412.3     .07       0    4839    .035       0  4878.4    .035       0
  4883.3    .035       0  5046.3     .07       0    5116     .16       0
  5281.8     .07       0  5456.3     .16       0  5593.7     .07       0
Bank Sta=4878.4,4883.3
XS Rating Curve= 0 ,0
Exp/Cntr=0.3,0.1

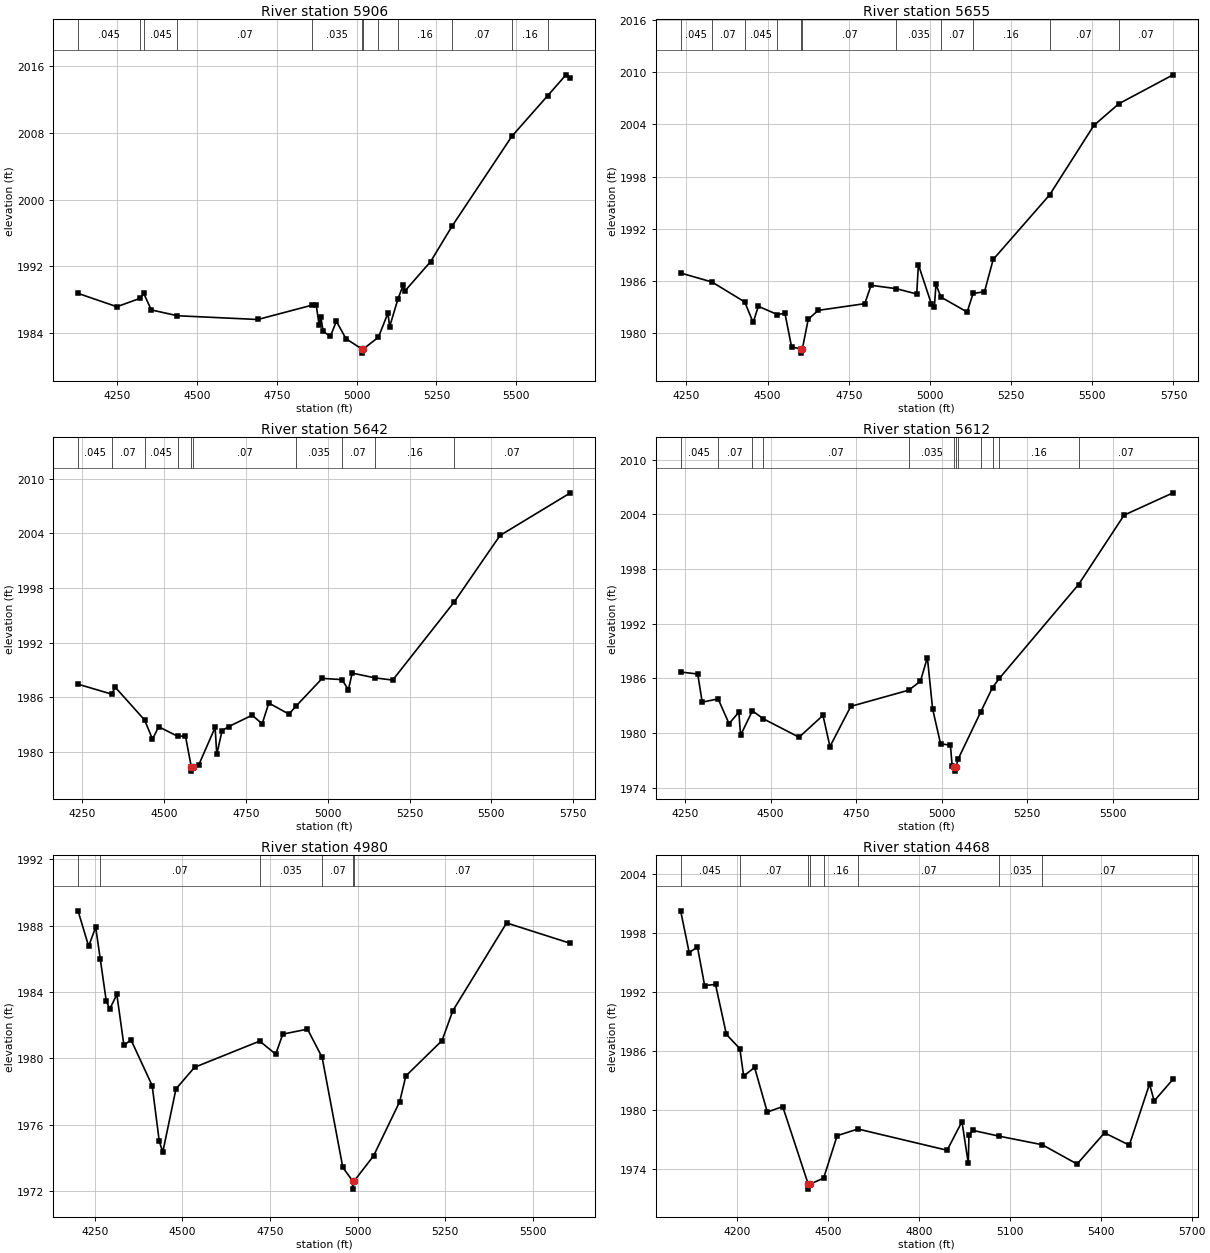
Type RM Length L Ch R = 1 ,5906    ,251,251,251
BEGIN DESCRIPTION:
Mapping XS 30832dee
END DESCRIPTION:
XS GIS Cut Line= 5
      1401041.92      6914840.34      1401776.26       6915134.6
      1401859.59       6915139.8      1402036.68      6915181.47
      1402518.47      6915254.39
#Sta/Elev= 30
  4126.3 1988.77  4248.1 1987.17  4320.9 1988.18  4332.2 1988.77  4355.9 1986.79
  4437.7 1986.09  4689.8 1985.64  4861.1 1987.37    4873 1987.35  4882.3 1984.96
  4887.7 1985.93  4894.5 1984.22  4917.4 1983.61  4936.2 1985.43  4966.2 1983.34
  5015.9 1982.11  5016.3 1981.61  5020.8 1982.11  5068.1 1983.52    5098 1986.42
  5103.1 1984.76  5129.2 1988.09  5145.5 1989.74  5150.6 1989.03  5231.7 1992.58
  5298.5  1996.8  5486.5  2007.6  5598.7 2012.46  5656.1 2014.96  5670.1 2014.55
#Mann= 12 ,-1 , 0
  4126.3    .045       0  4320.9     .07       0  4332.2    .045       0
  4437.7     .07       0  4861.1    .035       0  5015.9    .035       0
  5020.8    .035       0  5068.1     .07       0  5129.2     .16       0
  5298.5     .07       0  5486.5     .16       0  5598.7     .07       0
Bank Sta=5015.9,5020.8
XS Rating Curve= 0 ,0
Exp/Cntr=0.3,0.1

Type RM Length L Ch R = 1 ,5655    ,13,13,13
BEGIN DESCRIPTION:
Mapping XS 59d73af1
END DESCRIPTION:
XS GIS Cut Line= 4
      1401031.46      6915194.49      1401778.86      6915361.16
      1401948.14      6915376.78      1402528.85      6915371.57
#Sta/Elev= 30
  4232.3 1986.93  4328.7  1985.9  4429.5 1983.61  4455.7 1981.25  4471.6 1983.11
  4530.3 1982.16  4553.5 1982.31    4574 1978.43  4602.3 1978.23  4602.7 1977.73
  4607.2 1978.23  4625.3 1981.62    4656 1982.64  4799.4 1983.41  4818.8 1985.52
  4896.6 1985.13  4959.4 1984.52  4964.5 1987.89  5004.2 1983.42  5013.7 1983.02
  5018.7 1985.64  5033.7 1984.17  5114.7 1982.45  5132.9 1984.58  5168.1 1984.78
  5194.9 1988.49  5368.6  1995.9  5504.9 2003.88  5581.9 2006.37  5748.8 2009.69
#Mann= 11 ,-1 , 0
  4232.3    .045       0  4328.7     .07       0  4429.5    .045       0
  4530.3     .07       0  4602.3    .035       0  4607.2     .07       0
  4896.6    .035       0  5033.7     .07       0  5132.9     .16       0
  5368.6     .07       0  5581.9     .07       0
Bank Sta=4602.3,4607.2
XS Rating Curve= 0 ,0
Exp/Cntr=0.3,0.1

Type RM Length L Ch R = 1 ,5642    ,30,30,30
BEGIN DESCRIPTION:
Mapping XS 69dccd13
END DESCRIPTION:
XS GIS Cut Line= 4
       1401023.7      6915217.94      1401771.33      6915371.31
      1401963.76      6915405.43      1402510.32      6915408.03
#Sta/Elev= 30
  4236.8 1987.42    4340 1986.32  4350.4 1987.09  4440.5 1983.47  4464.4 1981.37
  4483.1 1982.74    4541  1981.7  4565.2 1981.71  4582.8 1978.36  4583.1 1977.86
  4587.7 1978.36  4605.4 1978.51  4655.8 1982.66  4660.9  1979.7  4677.1 1982.31
  4697.5 1982.76    4769 1984.01  4799.6 1983.06    4820 1985.35  4881.3 1984.13
    4904 1985.04  4983.3 1988.06  5043.3 1987.92  5063.3 1986.82  5074.8 1988.64
  5143.3 1988.12  5198.6 1987.87  5386.5 1996.45  5526.7 2003.77    5742 2008.46
#Mann= 10 ,-1 , 0
  4236.8    .045       0    4340     .07       0  4440.5    .045       0
    4541     .07       0  4582.8    .035       0  4587.7     .07       0
    4904    .035       0  5043.3     .07       0  5143.3     .16       0
  5386.5     .07       0
Bank Sta=4582.8,4587.7
XS Rating Curve= 0 ,0
Exp/Cntr=0.3,0.1

Type RM Length L Ch R = 1 ,5612    ,632,632,632
BEGIN DESCRIPTION:
Mapping XS bf458550
END DESCRIPTION:
XS GIS Cut Line= 4
      1401015.87       6915262.2      1401765.84      6915397.62
      1401919.49      6915428.87      1402437.76      6915460.12
#Sta/Elev= 30
  4237.5 1986.69  4287.4 1986.47  4300.5 1983.38    4347 1983.74  4378.9 1981.02
  4407.5 1982.28  4412.6 1979.75  4447.1 1982.43  4479.3 1981.55  4583.4 1979.53
  4653.2 1981.93  4673.6 1978.51  4734.5 1982.92    4904  1984.7  4937.8 1985.68
  4958.1 1988.28  4973.5 1982.62  4996.6 1978.82  5025.4 1978.65  5030.5 1976.39
  5037.1 1976.31  5037.5 1975.81    5042 1976.31  5047.9 1977.13  5113.3 1982.26
  5148.3 1984.99  5168.7 1986.01  5399.5 1996.29  5532.6 2003.91  5675.6 2006.36
#Mann= 12 ,-1 , 0
  4237.5    .045       0    4347     .07       0  4447.1    .045       0
  4479.3     .07       0    4904    .035       0  5037.1    .035       0
    5042    .035       0  5047.9     .07       0  5113.3     .16       0
  5148.3     .07       0  5168.7     .16       0  5399.5     .07       0
Bank Sta=5037.1,5042
XS Rating Curve= 0 ,0
Exp/Cntr=0.3,0.1

Type RM Length L Ch R = 1 ,4980    ,512,512,512
BEGIN DESCRIPTION:
Plum Creek Trib7 11.0
END DESCRIPTION:
XS GIS Cut Line= 3
      1401055.02        6915838.        1401855.        6915938.
      1402400.61      6916186.38
#Sta/Elev= 30
  4201.8 1988.89    4232 1986.76  4252.2  1987.9  4265.3 1985.98  4282.4 1983.45
  4292.5 1982.98  4312.6 1983.85  4332.8 1980.78  4352.9 1981.12  4413.4 1978.36
  4433.6 1975.01  4443.7 1974.35  4481.4 1978.16  4534.4 1979.46  4720.4 1981.04
  4766.1 1980.25  4786.3 1981.46  4856.8 1981.76  4898.6 1980.06  4957.6 1973.43
  4985.4 1972.62  4985.8 1972.12  4990.4 1972.62  5045.3 1974.12    5120 1977.39
  5137.6 1978.94  5240.8 1981.07  5271.7 1982.87  5425.2 1988.16  5607.5 1986.93
#Mann= 6 ,-1 , 0
  4201.8    .045       0  4265.3     .07       0  4720.4    .035       0
  4898.6     .07       0  4985.4     .07       0  4990.4     .07       0
Bank Sta=4985.4,4990.4
XS Rating Curve= 0 ,0
Exp/Cntr=0.3,0.1

Type RM Length L Ch R = 1 ,4468    ,13,13,13
BEGIN DESCRIPTION:
Mapping XS 33f17f3c
END DESCRIPTION:
XS GIS Cut Line= 6
      1400909.08      6915905.44      1401554.91      6916342.93
      1401591.36      6916301.26      1401643.45      6916314.28
      1401893.45      6916551.26      1402245.02      6916720.54
#Sta/Elev= 30
  4013.4 2000.25  4041.7    1996  4068.9 1996.58  4092.6 1992.66  4128.5 1992.77
  4164.5 1987.69  4208.8 1986.24  4221.4 1983.46  4257.4 1984.34  4299.4  1979.8
  4350.3 1980.36  4434.6 1972.47    4435 1971.97  4439.6 1972.47  4485.2 1973.08
    4530  1977.4  4598.3 1978.08  4892.9 1975.92  4941.9 1978.83  4962.8 1974.58
    4965 1977.42  4977.8 1977.94  5064.9 1977.35  5206.9 1976.48  5321.9 1974.52
  5412.4 1977.69  5494.3 1976.44  5560.9 1982.65  5576.3 1980.93  5638.6 1983.14
#Mann= 8 ,-1 , 0
  4013.4    .045       0  4208.8     .07       0  4434.6     .07       0
  4439.6     .07       0  4485.2     .16       0  4598.3     .07       0
  5064.9    .035       0  5206.9     .07       0
Bank Sta=4434.6,4439.6
XS Rating Curve= 0 ,0
Exp/Cntr=0.3,0.1

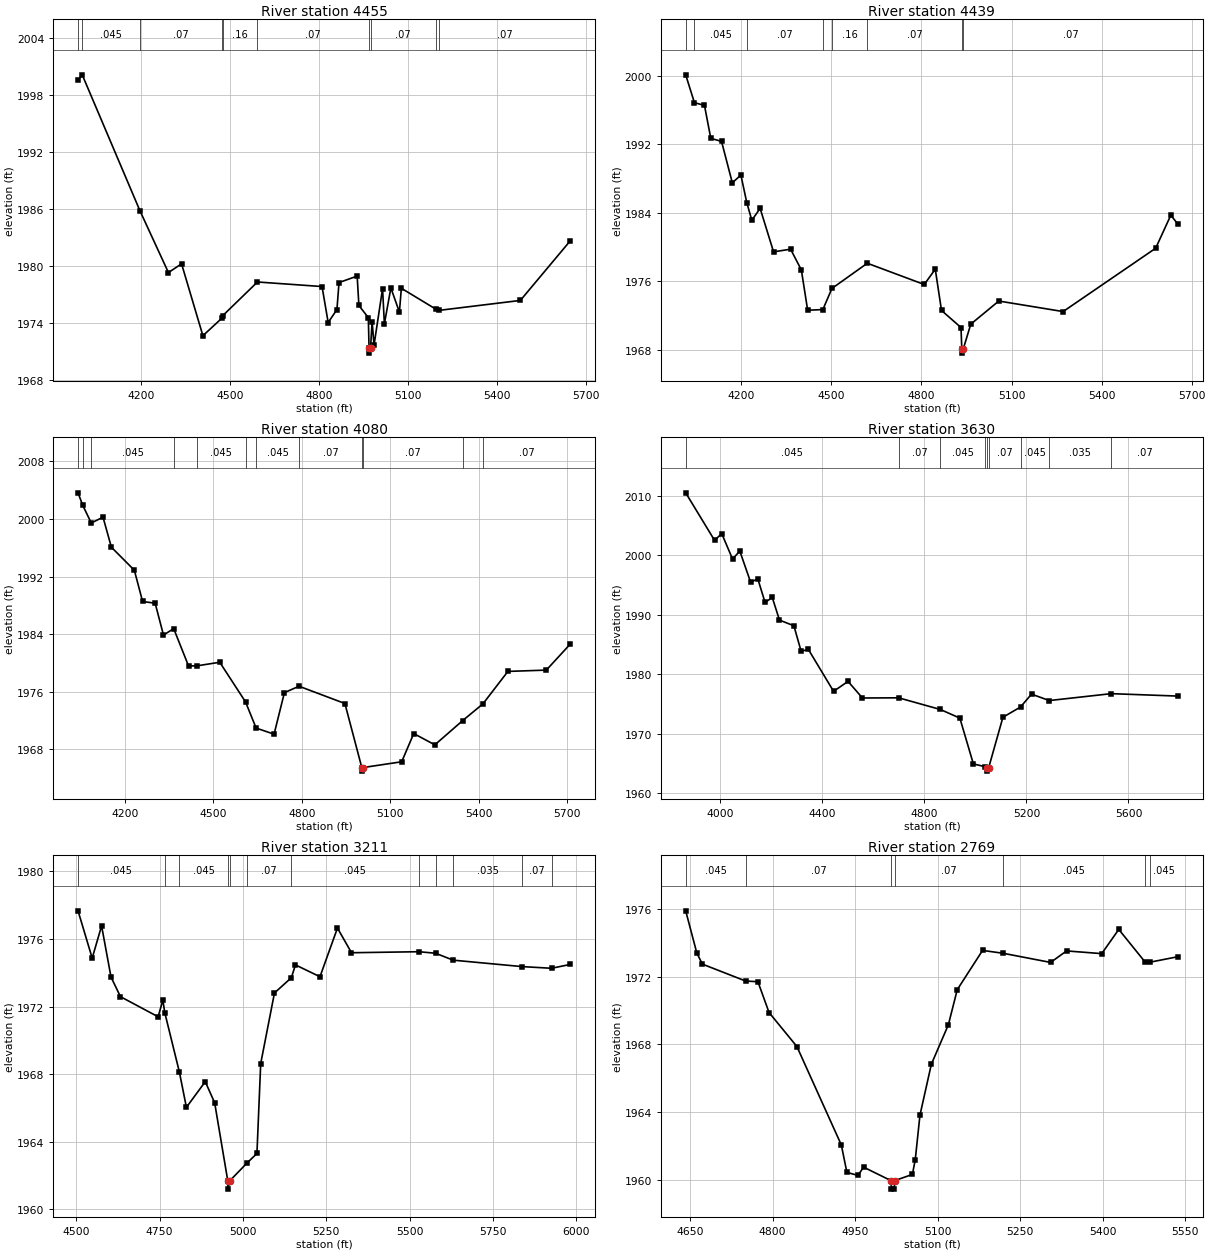
Type RM Length L Ch R = 1 ,4455    ,16,16,16
BEGIN DESCRIPTION:
Mapping XS f6cc07b0
END DESCRIPTION:
XS GIS Cut Line= 6
      1400893.45      6915915.85      1401570.53      6916376.78
       1401612.2      6916316.89      1401682.51      6916358.55
      1401890.84       6916577.3      1402230.99      6916748.68
#Sta/Elev= 30
  3988.9 1999.56    4003 2000.11  4197.4 1985.81  4293.2 1979.32  4337.4 1980.24
  4409.2 1972.68  4472.3  1974.5  4475.4 1974.77  4592.9 1978.33  4810.3 1977.85
  4830.9 1974.07  4860.4 1975.43  4867.4 1978.27  4928.5 1978.95  4934.3 1975.86
  4966.1 1974.58  4968.5 1971.35  4968.9 1970.85  4973.5 1971.35  4978.8 1974.17
  4985.3 1971.69    5014 1977.63  5020.1 1973.93    5042 1977.71  5070.7 1975.16
  5077.2 1977.67  5193.5 1975.47  5205.3 1975.35  5477.8 1976.39  5646.4 1982.68
#Mann= 10 ,-1 , 0
  3988.9     .07       0    4003    .045       0  4197.4     .07       0
  4472.3    .045       0  4475.4     .16       0  4592.9     .07       0
  4968.5     .07       0  4973.5     .07       0  5193.5    .035       0
  5205.3     .07       0
Bank Sta=4968.5,4973.5
XS Rating Curve= 0 ,0
Exp/Cntr=0.3,0.1

Type RM Length L Ch R = 1 ,4439    ,359,359,359
BEGIN DESCRIPTION:
Mapping XS 0c0587cd
END DESCRIPTION:
XS GIS Cut Line= 6
      1400893.44      6915934.07      1401575.74      6916402.82
      1401609.59      6916355.95      1401666.89      6916368.97
      1401843.97      6916595.53      1402208.57      6916775.23
#Sta/Elev= 30
  4014.6 2000.11  4043.7 1996.86  4077.2 1996.54  4098.2  1992.7    4134 1992.34
  4169.9 1987.51  4198.5 1988.41  4218.2 1985.18  4234.9 1983.14  4262.6 1984.52
  4307.3 1979.45  4364.1 1979.76  4399.9 1977.34  4420.9 1972.64  4471.5 1972.71
  4501.8 1975.18  4619.6 1978.12  4809.3 1975.64    4846 1977.43  4866.8 1972.61
  4931.7 1970.62  4934.4 1968.13  4934.8 1967.63  4939.4 1968.13  4964.3 1971.01
  5057.6 1973.71  5271.9 1972.48  5580.2 1979.87  5630.7 1983.73  5654.9 1982.65
#Mann= 8 ,-1 , 0
  4014.6     .07       0  4043.7    .045       0  4218.2     .07       0
  4471.5    .045       0  4501.8     .16       0  4619.6     .07       0
  4934.4     .07       0  4939.4     .07       0
Bank Sta=4934.4,4939.4
XS Rating Curve= 0 ,0
Exp/Cntr=0.3,0.1

Type RM Length L Ch R = 1 ,4080    ,450,450,450
BEGIN DESCRIPTION:
Plum Creek Trib7 9.0
END DESCRIPTION:
XS GIS Cut Line= 3
      1400804.99      6915937.99        1401455.        6916638.
      1402154.95      6916787.99
#Sta/Elev= 30
  4040.5 2003.63  4056.1 2001.93  4085.4 1999.44  4125.3 2000.25  4153.6 1996.08
  4231.6 1992.88  4259.6 1988.54  4302.2  1988.3  4330.5 1983.88  4365.2 1984.77
  4415.5 1979.59  4443.8  1979.6  4521.5  1980.1    4609 1974.59  4644.9 1970.96
  4705.8 1970.11  4740.9 1975.88  4790.5 1976.77  4946.2 1974.37  5003.5 1965.48
  5003.9 1964.98  5008.5 1965.48  5138.9 1966.28  5179.8  1970.2  5251.4 1968.63
  5346.2 1972.01  5414.6 1974.32  5499.4 1978.83  5629.8 1979.01  5711.6 1982.65
#Mann= 12 ,-1 , 0
  4040.5    .045       0  4056.1     .07       0  4085.4    .045       0
  4365.2     .07       0  4443.8    .045       0    4609     .16       0
  4644.9    .045       0  4790.5     .07       0  5003.5     .07       0
  5008.5     .07       0  5346.2    .045       0  5414.6     .07       0
Bank Sta=5003.5,5008.5
XS Rating Curve= 0 ,0
Exp/Cntr=0.3,0.1

Type RM Length L Ch R = 1 ,3630    ,419,419,419
BEGIN DESCRIPTION:
Plum Creek Trib7 8.0
END DESCRIPTION:
XS GIS Cut Line= 3
      1400405.02      6916188.02        1401205.        6916988.
      1401916.87      6917350.74
#Sta/Elev= 30
  3864.3 2010.47  3977.4 2002.49  4005.7 2003.61  4048.1 1999.33  4076.4  2000.7
  4118.8 1995.45  4147.1 1996.01  4175.4 1992.05  4203.7 1992.88    4232 1989.08
  4288.5 1988.13  4316.8 1983.84  4345.1 1984.16  4444.1 1977.11  4500.7 1978.78
  4557.2 1975.99  4699.1 1976.02  4862.6 1974.06  4939.1 1972.61  4992.1 1964.91
  5036.3 1964.46  5045.3  1964.2  5045.8  1963.7  5051.6  1964.2  5107.9 1972.75
  5176.9 1974.48  5220.1 1976.64  5289.6 1975.56  5532.6 1976.72  5794.6 1976.31
#Mann= 9 ,-1 , 0
  3864.3    .045       0  4699.1     .07       0  4862.6    .045       0
  5036.3     .07       0  5045.3    .045       0  5051.6     .07       0
  5176.9    .045       0  5289.6    .035       0  5532.6     .07       0
Bank Sta=5045.3,5051.6
XS Rating Curve= 0 ,0
Exp/Cntr=0.3,0.1

Type RM Length L Ch R = 1 ,3211    ,442,442,442
BEGIN DESCRIPTION:
Plum Creek Trib7 7.0
END DESCRIPTION:
XS GIS Cut Line= 3
      1400604.98      6916937.98        1400955.        6917288.
       1401890.4      6917590.18
#Sta/Elev= 30
    4505 1977.67  4547.5 1974.87  4575.7 1976.78    4604 1973.75  4632.3 1972.59
  4745.4  1971.4  4759.6 1972.39  4765.3 1971.65  4809.2 1968.13  4830.3 1966.04
  4886.9 1967.56  4915.1 1966.31  4954.4  1961.7  4954.9  1961.2  4960.8  1961.7
  5012.5 1962.75    5042 1963.31  5053.3 1968.63  5094.6 1972.81  5145.3 1973.71
  5157.6 1974.47  5231.2 1973.77  5283.7 1976.65  5325.8 1975.19    5528 1975.25
  5578.1 1975.16  5631.1 1974.75  5837.3 1974.37  5926.3 1974.27    5983  1974.5
#Mann= 12 ,-1 , 0
    4505    .045       0  4765.3     .07       0  4809.2    .045       0
  4954.4    .045       0  4960.8    .045       0  5012.5     .07       0
  5145.3    .045       0    5528    .035       0  5578.1     .07       0
  5631.1    .035       0  5837.3     .07       0  5926.3    .035       0
Bank Sta=4954.4,4960.8
XS Rating Curve= 0 ,0
Exp/Cntr=0.3,0.1

Type RM Length L Ch R = 1 ,2769    ,432,432,432
BEGIN DESCRIPTION:
Plum Creek Trib7 6.0
END DESCRIPTION:
XS GIS Cut Line= 3
      1400354.98        6917588.        1400705.        6917638.
      1401229.42      6917772.63
#Sta/Elev= 30
  4642.2 1975.89  4662.4  1973.4  4672.5 1972.74  4751.2 1971.74  4773.5  1971.7
  4793.7 1969.88  4844.3 1967.87  4925.1 1962.05  4935.2 1960.43  4955.4 1960.25
  4965.5 1960.74  5015.5 1959.94    5016 1959.44  5021.4 1959.44  5021.9 1959.94
  5054.3 1960.31  5059.5 1961.19    5068 1963.81  5088.7 1966.82  5119.7 1969.16
  5135.8 1971.23  5181.8 1973.55  5219.3 1973.38  5305.5 1972.84  5334.5 1973.52
  5398.4 1973.36  5429.4 1974.79  5477.1 1972.87    5487 1972.86  5537.2 1973.18
#Mann= 7 ,-1 , 0
  4642.2    .045       0  4751.2     .07       0  5015.5     .07       0
  5021.9     .07       0  5219.3    .045       0  5477.1     .07       0
    5487    .045       0
Bank Sta=5015.5,5021.9
XS Rating Curve= 0 ,0
Exp/Cntr=0.3,0.1

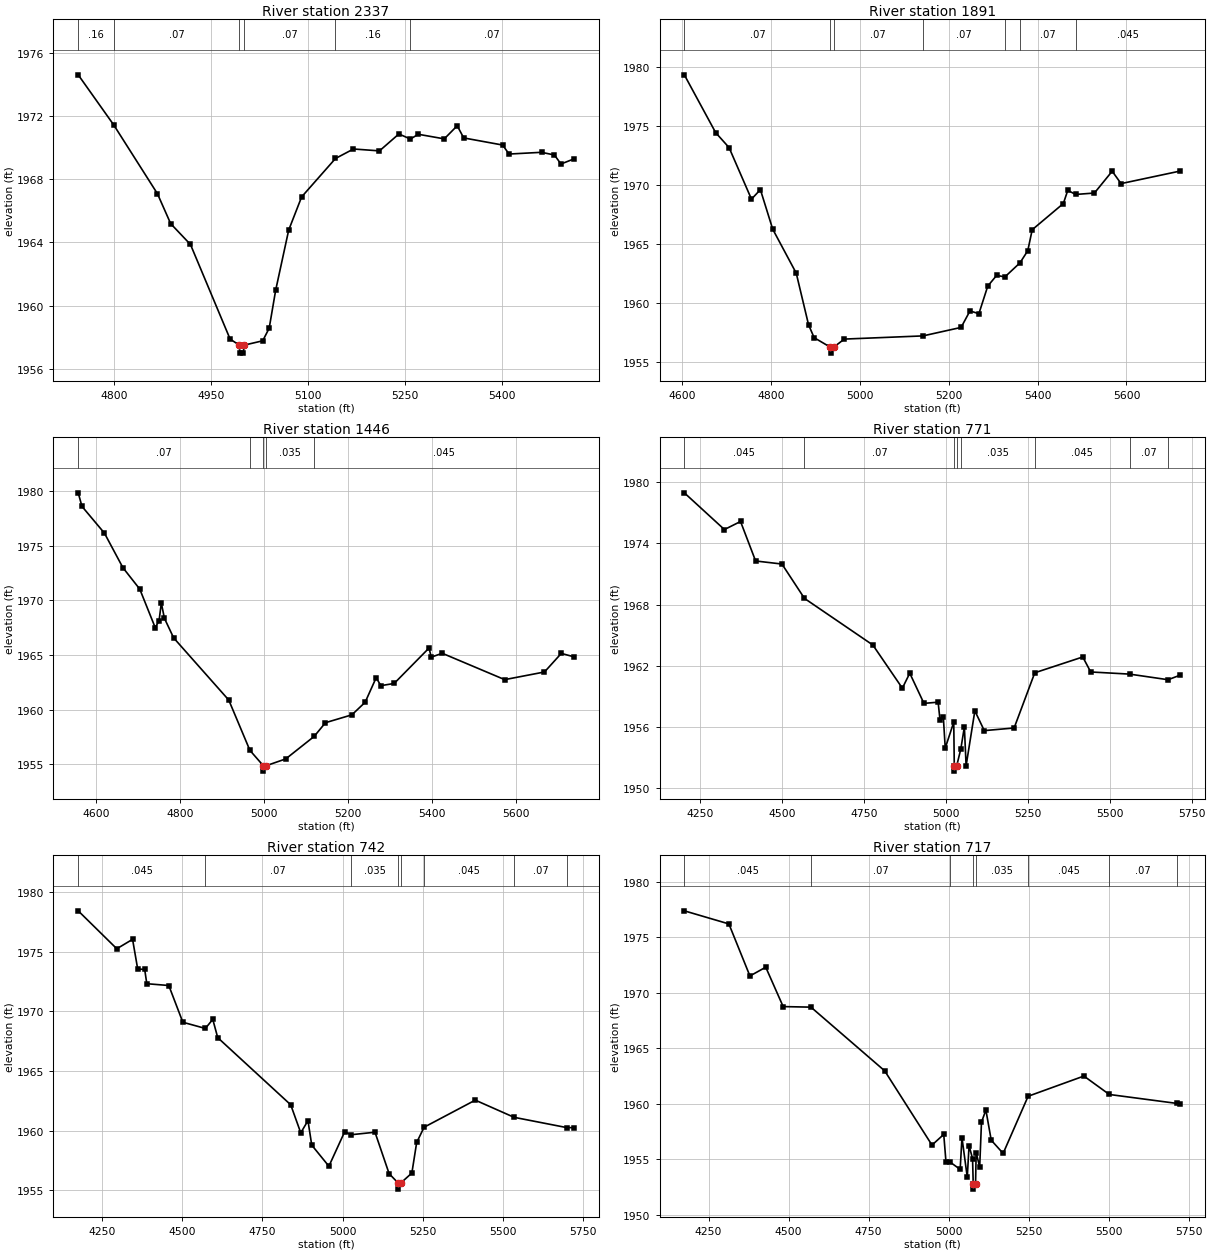
Type RM Length L Ch R = 1 ,2337    ,446,446,446
BEGIN DESCRIPTION:
Plum Creek Trib7 5.0
END DESCRIPTION:
XS GIS Cut Line= 3
      1400354.97      6917987.99        1400605.        6918038.
      1401114.85      6918064.29
#Sta/Elev= 30
  4745.1  1974.6    4800 1971.43  4867.5 1967.08  4887.9 1965.19  4918.5 1963.87
  4979.7 1957.89  4994.1  1957.5  4994.6    1957  5000.4    1957  5000.9  1957.5
  5030.1 1957.78  5040.1 1958.58  5050.1 1960.98  5070.2 1964.78  5090.2 1966.88
  5142.5 1969.31  5170.3 1969.91  5210.4 1969.79  5240.4 1970.86  5258.2 1970.54
  5270.4 1970.84  5310.5 1970.55  5330.5 1971.38  5340.5 1970.61  5400.6 1970.16
  5410.6 1969.59  5460.7  1969.7  5480.7 1969.53  5490.7 1968.96  5510.6 1969.28
#Mann= 6 ,-1 , 0
  4745.1     .16       0    4800     .07       0  4994.1     .07       0
  5000.9     .07       0  5142.5     .16       0  5258.2     .07       0
Bank Sta=4994.1,5000.9
XS Rating Curve= 0 ,0
Exp/Cntr=0.3,0.1

Type RM Length L Ch R = 1 ,1891    ,445,445,445
BEGIN DESCRIPTION:
Plum Creek Trib7 4.0
END DESCRIPTION:
XS GIS Cut Line= 3
      1400254.99        6918388.        1400655.        6918438.
      1401367.46      6918410.64
#Sta/Elev= 30
  4604.4 1979.32    4675 1974.42  4705.2 1973.15  4755.6 1968.78  4775.7 1969.59
  4803.4 1966.24  4856.4 1962.51  4884.1 1958.14  4896.7 1957.04  4933.4 1956.23
  4933.9 1955.73  4940.6 1956.23  4964.7 1956.92  5141.8 1957.19  5227.7 1957.91
  5247.7 1959.31  5267.7 1959.07  5287.7 1961.41  5307.7 1962.32  5326.3 1962.19
  5360.2 1963.38  5377.8 1964.41  5387.8 1966.19  5457.9 1968.41  5467.9 1969.53
  5485.5 1969.18  5527.9  1969.3  5567.9 1971.15  5587.9  1970.1  5720.5 1971.16
#Mann= 7 ,-1 , 0
  4604.4     .07       0  4933.4    .035       0  4940.6     .07       0
  5141.8     .07       0  5326.3    .045       0  5360.2     .07       0
  5485.5    .045       0
Bank Sta=4933.4,4940.6
XS Rating Curve= 0 ,0
Exp/Cntr=0.3,0.1

Type RM Length L Ch R = 1 ,1446    ,675,675,675
BEGIN DESCRIPTION:
Plum Creek Trib7 3.0
END DESCRIPTION:
XS GIS Cut Line= 3
      1400098.09      6918650.94        1400505.        6918838.
      1401201.34       6919071.5
#Sta/Elev= 30
  4556.7 1979.83  4565.7 1978.59  4619.3 1976.14  4663.4 1972.98  4703.6 1971.02
  4740.4  1967.5  4749.5 1968.11    4755 1969.74  4762.4 1968.35  4784.4 1966.56
  4915.9 1960.87  4966.3 1956.27  4998.2 1954.87  4998.7 1954.37  5005.4 1954.87
  5051.9 1955.49  5119.7 1957.55  5146.5  1958.8  5209.6 1959.52  5241.2 1960.67
  5267.4 1962.91  5278.8 1962.19  5310.4 1962.39  5393.6 1965.63  5398.9  1964.8
  5425.2 1965.15  5574.1 1962.74    5669 1963.44  5709.1 1965.14    5739 1964.83
#Mann= 5 ,-1 , 0
  4556.7     .07       0  4966.3    .035       0  4998.2    .035       0
  5005.4    .035       0  5119.7    .045       0
Bank Sta=4998.2,5005.4
XS Rating Curve= 0 ,0
Exp/Cntr=0.3,0.1

Type RM Length L Ch R = 1 ,771     ,29,29,29
BEGIN DESCRIPTION:
Mapping XS 84d7af35
END DESCRIPTION:
XS GIS Cut Line= 4
      1399708.53      6918548.62      1400101.78      6919243.97
      1400130.43      6919335.12      1400706.03      6919561.75
#Sta/Elev= 30
  4201.4 1978.95  4323.8 1975.35    4373 1976.14    4419 1972.27  4499.4 1971.97
  4568.2  1968.6    4777 1964.03    4867  1959.8  4889.6 1961.27  4932.9 1958.31
  4976.2 1958.43    4982 1956.66  4992.1 1956.95  4997.9 1953.93  5023.9 1956.47
  5025.5 1952.17    5026 1951.67  5032.8 1952.17  5045.6 1953.87  5056.3    1956
  5061.6  1952.2  5088.3 1957.58  5117.1 1955.64  5208.2  1955.9  5271.2 1961.31
  5417.7 1962.86    5442 1961.39  5560.5 1961.18  5678.1 1960.63  5714.4 1961.07
#Mann= 8 ,-1 , 0
  4201.4    .045       0  4568.2     .07       0  5025.5     .07       0
  5032.8     .07       0  5045.6    .035       0  5271.2    .045       0
  5560.5     .07       0  5678.1    .045       0
Bank Sta=5025.5,5032.8
XS Rating Curve= 0 ,0
Exp/Cntr=0.3,0.1

Type RM Length L Ch R = 1 ,742     ,25,25,25
BEGIN DESCRIPTION:
Mapping XS 4aca5350
END DESCRIPTION:
XS GIS Cut Line= 4
       1399679.9      6918540.83      1400078.34       6919259.6
      1400122.61      6919363.76      1400690.95      6919588.06
#Sta/Elev= 30
  4175.2 1978.43  4295.6 1975.25  4344.8 1976.04  4360.8 1973.55  4382.6 1973.52
  4389.2 1972.32  4457.8 1972.17  4501.6 1969.09  4571.8 1968.57    4595 1969.33
  4610.4  1967.8  4838.1 1962.17  4869.4 1959.82  4891.9 1960.84  4903.7 1958.79
  4957.2 1957.02  5006.4 1959.91  5026.3 1959.66    5101 1959.87    5145  1956.4
  5173.6  1955.6  5174.1  1955.1  5180.9  1955.6    5216 1956.45    5231 1959.01
  5254.2 1960.29  5413.8 1962.56  5534.9 1961.12  5698.7 1960.26  5721.2 1960.25
#Mann= 8 ,-1 , 0
  4175.2    .045       0  4571.8     .07       0  5026.3    .035       0
  5173.6     .07       0  5180.9    .035       0  5254.2    .045       0
  5534.9     .07       0  5698.7    .045       0
Bank Sta=5173.6,5180.9
XS Rating Curve= 0 ,0
Exp/Cntr=0.3,0.1

Type RM Length L Ch R = 1 ,717     ,512,512,512
BEGIN DESCRIPTION:
Mapping XS 82361716
END DESCRIPTION:
XS GIS Cut Line= 4
      1399672.12      6918553.91      1400062.72      6919280.43
      1400117.41       6919387.2      1400675.39      6919618.89
#Sta/Elev= 30
  4174.1 1977.38  4313.4  1976.2  4379.1 1971.51  4428.6  1972.3    4483 1968.75
  4569.9  1968.7  4800.3 1962.96  4948.1 1956.27  4984.9 1957.23  4991.9 1954.74
    5005 1954.73  5036.2 1954.08  5041.8 1956.94  5058.4 1953.38    5064 1956.21
  5074.9 1955.06    5077  1952.8  5077.5  1952.3  5084.3  1952.8  5086.2 1955.59
  5097.2 1954.29  5102.8 1958.33  5116.6 1959.43  5133.3 1956.71  5170.5 1955.52
  5248.6 1960.67  5422.9 1962.49  5502.3 1960.83  5714.7 1960.02  5723.1 1960.01
#Mann= 8 ,-1 , 0
  4174.1    .045       0  4569.9     .07       0    5005    .035       0
    5077     .07       0  5084.3    .035       0  5248.6    .045       0
  5502.3     .07       0  5714.7    .045       0
Bank Sta=5077,5084.3
XS Rating Curve= 0 ,0
Exp/Cntr=0.3,0.1