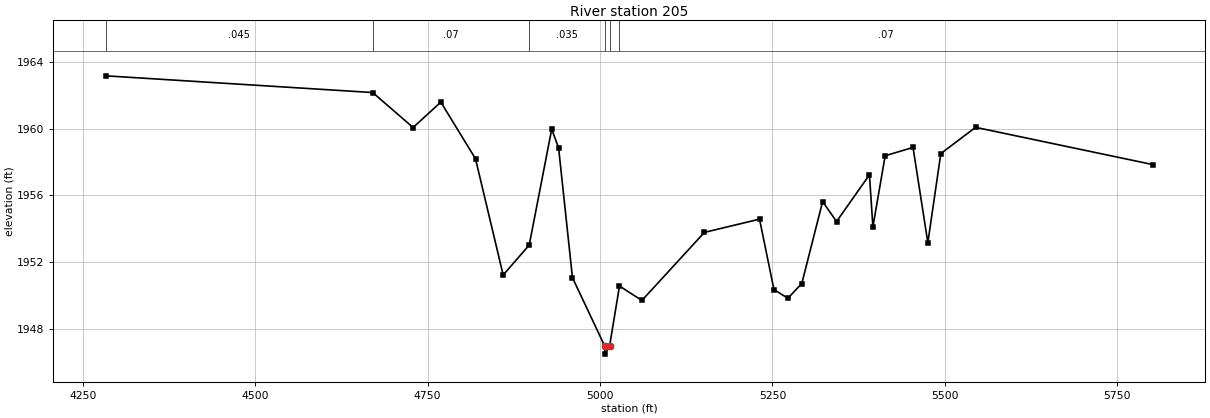
HEC-RAS study Plum Creek Trib7.prj: Plum Creek Trib7 Base Level Engineering

--- Plum Creek Trib7.g01 (geometry) --- (continued)

Type RM Length L Ch R = 1 ,205     ,0,0,0
BEGIN DESCRIPTION:
Plum Creek Trib7 1.0
END DESCRIPTION:
XS GIS Cut Line= 3
      1399091.36      6919573.83       1399804.8       6919643.1
      1400600.31      6919744.93
#Sta/Elev= 30
  4283.2 1963.15  4670.3 1962.15  4728.9 1960.06  4769.1 1961.58  4819.4 1958.19
  4859.5 1951.24  4897.3 1953.03  4929.9 1959.96  4939.9 1958.84    4960 1951.08
  5006.6 1947.01  5007.1 1946.51  5013.9 1947.01  5028.2 1950.58  5060.7 1949.72
  5151.4 1953.79  5231.3 1954.58  5252.2 1950.37  5272.4 1949.85  5292.6 1950.73
  5322.8 1955.63    5343 1954.44  5390.7 1957.23  5395.7 1954.12  5413.5 1958.37
  5453.9 1958.87  5475.4 1953.17  5494.2  1958.5  5544.6 1960.07    5802 1957.84
#Mann= 6 ,-1 , 0
  4283.2    .045       0  4670.3     .07       0  4897.3    .035       0
  5006.6    .035       0  5013.9    .035       0  5028.2     .07       0
Bank Sta=5006.6,5013.9
XS Rating Curve= 0 ,0
Exp/Cntr=0.3,0.1

Chan Stop Cuts=-1
Use User Specified Reach Order=0
Composite Channel Slope=5