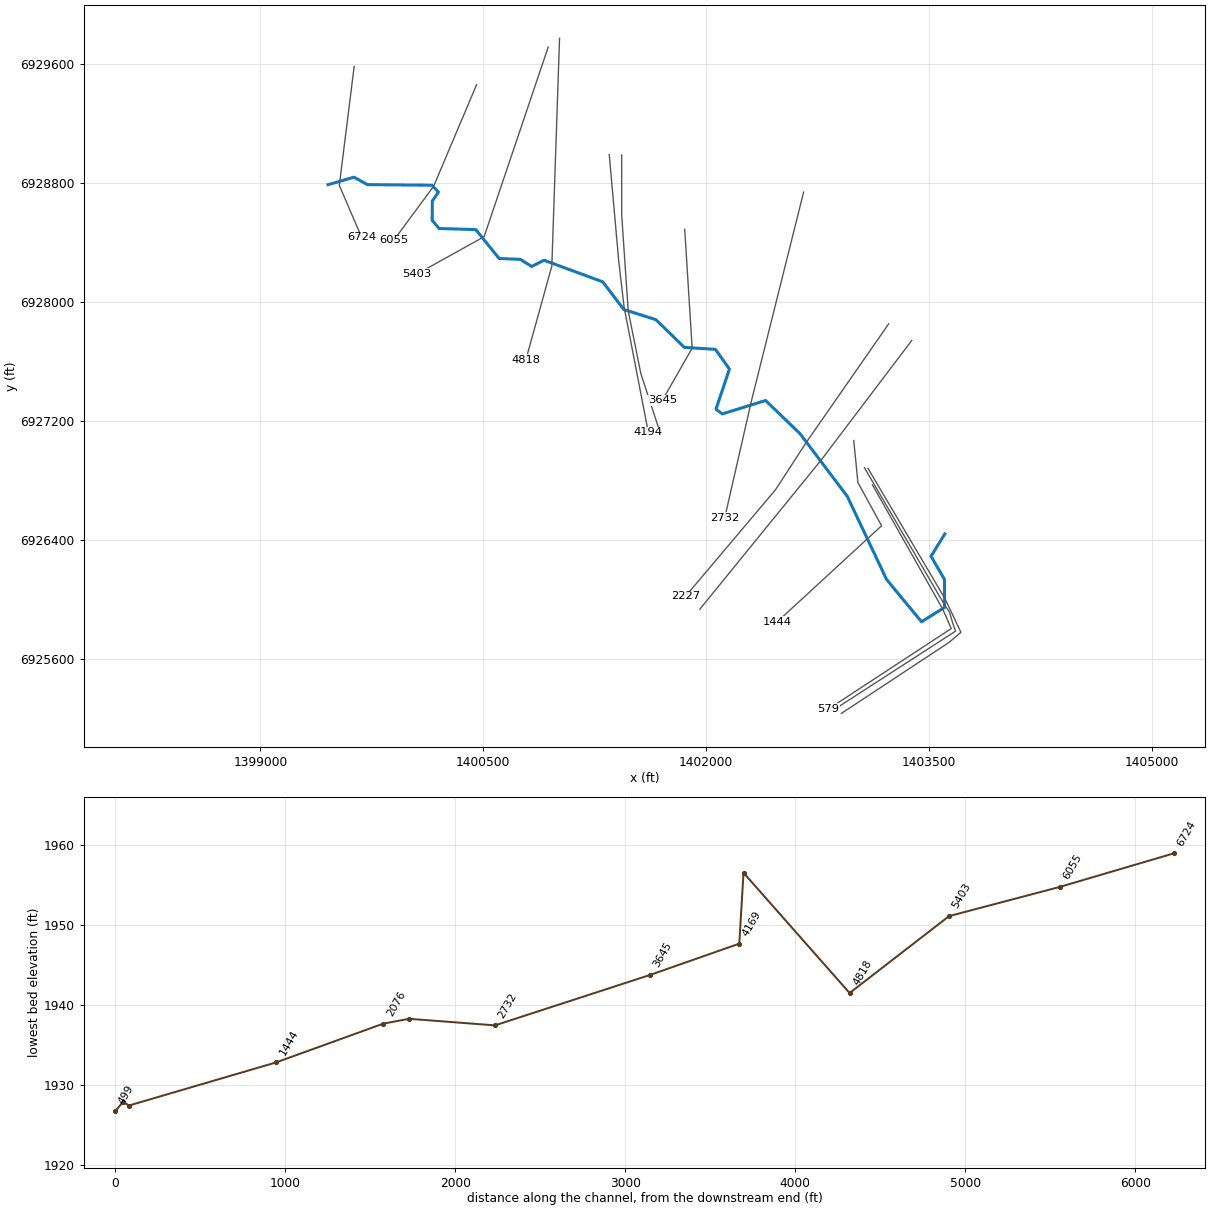
--- Plum Creek Trib8.prj (project) ---

Proj Title=Plum Creek Trib8 Base Level Engineering
Current Plan=p01
Default Exp/Contr=0.3,0.1
English Units
Geom File=g01
Flow File=f01
Plan File=p01
Y Axis Title=Elevation
X Axis Title(PF)=Main Channel Distance
X Axis Title(XS)=Station
BEGIN DESCRIPTION:
Plum Creek Trib8
END DESCRIPTION:
DSS Export Rating Curves= 0
DSS Export Rating Curve Sorted= 0
DSS Export Volume Flow Curves= 0
DXF OffsetX= 0
DXF OffsetY= 0
DXF ScaleX= 1
DXF ScaleY= 10

--- Plum Creek Trib8.p01 (plan) ---

Plan Title=Multiple Run
Short Identifier=Multiple
Geom File=g01
Flow File=f01
Subcritical Flow
K Sum by GR= 0
Std Step Tol= 0.01
Critical Tol= 0.01
Num of Std Step Trials= 20
Max Error Tol= 0.3
Flow Tol Ratio= 0.001
Split Flow NTrial= 30
Split Flow Tol= 0.02
Split Flow Ratio= 0.02
Log Output Level= 0
Friction Slope Method= 1
Unsteady Friction Slope Method= 2
Unsteady Bridges Friction Slope Method= 1
Parabolic Critical Depth
Global Vel Dist=  1 , 1 , 1
Global Log Level= 0
CheckData=True
Encroach Param= -1, 0, 0, 0
BEGIN DESCRIPTION:
Multiple Run
END DESCRIPTION:

--- Plum Creek Trib8.f01 (steady flow) ---

Flow Title=Multiple
Number of Profiles=7
Profile Names=10-year,25-year,50-year,1pct_min,100-year,1pct_plu,500-year
River Rch & RM= Plum Creek Trib8,Reach-1,6724
     355     508     637     398     794    1583    1247
River Rch & RM= Plum Creek Trib8,Reach-1,4194
     357     510     641     400     798    1591    1252
River Rch & RM= Plum Creek Trib8,Reach-1,2732
     480     698     885     558    1112    2220    1781
River Rch & RM= Plum Creek Trib8,Reach-1,2227
     497     723     917     578    1153    2300    1845
Boundary for River Rch & Prof#=Plum Creek Trib8,Reach-1,1
Up Type=0
Dn Type=3
Dn Slope=0.005
Boundary for River Rch & Prof#=Plum Creek Trib8,Reach-1,2
Up Type=0
Dn Type=3
Dn Slope=0.005
Boundary for River Rch & Prof#=Plum Creek Trib8,Reach-1,3
Up Type=0
Dn Type=3
Dn Slope=0.005
Boundary for River Rch & Prof#=Plum Creek Trib8,Reach-1,4
Up Type=0
Dn Type=3
Dn Slope=0.005
Boundary for River Rch & Prof#=Plum Creek Trib8,Reach-1,5
Up Type=0
Dn Type=3
Dn Slope=0.005
Boundary for River Rch & Prof#=Plum Creek Trib8,Reach-1,6
Up Type=0
Dn Type=3
Dn Slope=0.005
Boundary for River Rch & Prof#=Plum Creek Trib8,Reach-1,7
Up Type=0
Dn Type=3
Dn Slope=0.005

--- Plum Creek Trib8.g01 (geometry) ---

Geom Title=Existing Conditions
Program Version=4.10

River Reach=Plum Creek Trib8,Reach-1
Reach XY= 30
        1399455.        6928788.        1399630.      6928838.42
      1399720.21      6928788.54      1400154.01      6928784.47
      1400197.79      6928738.35      1400156.38      6928677.57
      1400155.96      6928548.27      1400202.26      6928493.34
      1400449.16      6928485.95      1400606.25      6928291.45
      1400749.07       6928285.7      1400825.21      6928237.79
      1400908.29       6928279.9      1401303.52      6928134.39
       1401444.9      6927948.39      1401661.06      6927879.86
      1401852.55      6927693.46      1402061.21       6927680.2
      1402155.83      6927548.07      1402065.18      6927277.58
      1402107.98      6927245.79      1402399.11      6927336.04
      1402631.98      6927111.47      1402949.17       6926690.3
      1403213.14      6926131.94      1403448.25       6925847.1
      1403603.02      6925943.67      1403602.76      6926132.07
      1403512.28      6926288.09        1403605.        6926438.

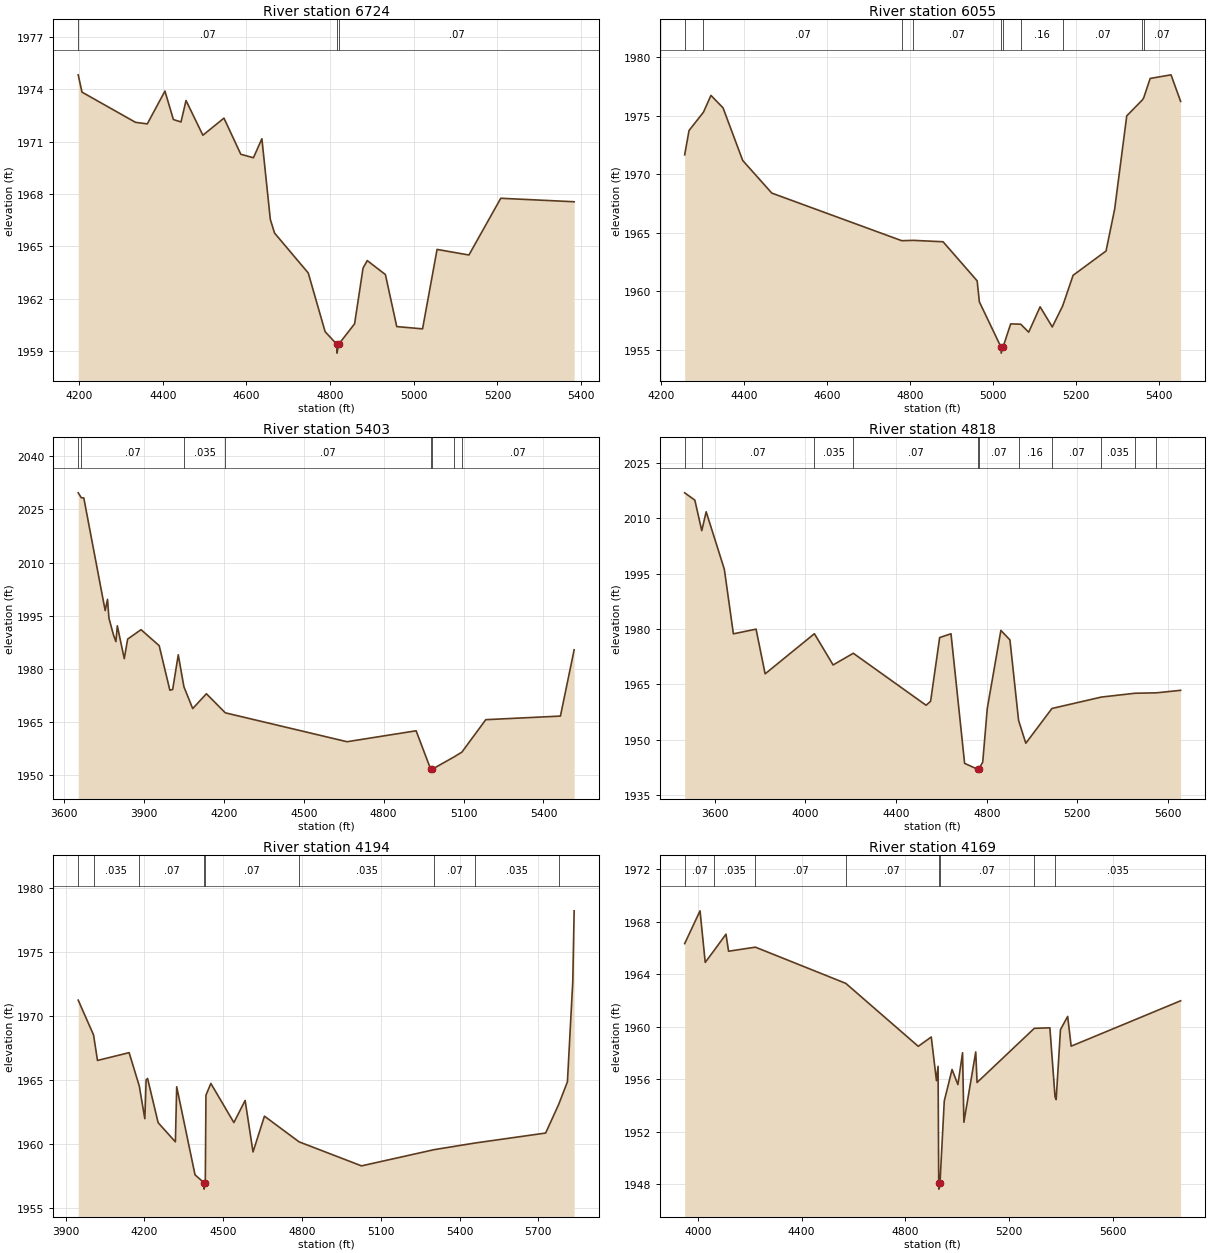
Type RM Length L Ch R = 1 ,6724    ,669,669,669
BEGIN DESCRIPTION:
Plum Creek Trib8 9.0
END DESCRIPTION:
XS GIS Cut Line= 3
      1399630.87      6929583.81      1399530.87      6928783.84
      1399680.45      6928434.84
#Sta/Elev= 30
  4197.6 1974.83  4206.6 1973.84  4334.5 1972.11  4362.8 1972.02    4405  1973.9
  4425.2 1972.27  4443.4 1972.13  4455.4 1973.36  4495.7 1971.37  4546.1 1972.35
  4586.4 1970.28  4616.6 1970.08  4636.8 1971.17    4657 1966.55    4667 1965.77
  4747.7 1963.48    4788 1960.12  4816.2 1959.39  4816.5 1958.89  4820.2 1959.39
  4858.5 1960.57  4878.7 1963.76  4888.8 1964.19  4932.2 1963.39  4959.3 1960.41
    5021 1960.28  5055.7 1964.83  5131.9 1964.51    5208 1967.76  5383.5 1967.56
#Mann= 3 ,-1 , 0
  4197.6     .07       0  4816.2     .07       0  4820.2     .07       0
Bank Sta=4816.2,4820.2
XS Rating Curve= 0 ,0
Exp/Cntr=0.3,0.1

Type RM Length L Ch R = 1 ,6055    ,652,652,652
BEGIN DESCRIPTION:
Plum Creek Trib8 8.0
END DESCRIPTION:
XS GIS Cut Line= 3
      1400454.62      6929461.34      1400165.53      6928777.53
      1399896.87      6928413.55
#Sta/Elev= 30
  4257.6 1971.66  4268.1 1973.74  4302.9 1975.31  4320.9 1976.74    4350 1975.68
  4397.4 1971.18  4467.5 1968.39  4780.6 1964.32  4808.3 1964.35  4880.1 1964.23
  4962.2 1960.89  4967.6 1959.09  5019.9 1955.21  5020.2 1954.71  5024.4 1955.21
    5043 1957.21  5067.3 1957.18  5086.4  1956.5  5113.9 1958.67  5143.2 1956.95
  5168.3 1958.75  5193.3 1961.36  5272.7 1963.44  5293.5 1967.02  5322.6 1974.99
  5360.4 1976.36  5363.7 1976.56  5379.1 1978.19  5429.3  1978.5  5452.4 1976.23
#Mann= 10 ,-1 , 0
  4257.6    .035       0  4302.9     .07       0  4780.6     .16       0
  4808.3     .07       0  5019.9     .07       0  5024.4     .07       0
  5067.3     .16       0  5168.3     .07       0  5360.4    .035       0
  5363.7     .07       0
Bank Sta=5019.9,5024.4
XS Rating Curve= 0 ,0
Exp/Cntr=0.3,0.1

Type RM Length L Ch R = 1 ,5403    ,585,585,585
BEGIN DESCRIPTION:
Plum Creek Trib8 7.0
END DESCRIPTION:
XS GIS Cut Line= 3
      1400936.37      6929713.86      1400505.31      6928438.33
      1400055.02      6928188.01
#Sta/Elev= 30
  3653.6 2029.71  3665.1 2028.33  3674.6 2028.27  3754.8 1996.44  3763.6 1999.61
  3768.9  1994.3  3786.5 1989.43  3795.1 1987.67  3800.4 1992.13  3826.5 1982.85
  3839.2 1988.38  3889.4 1991.04  3957.6 1986.51  3997.6 1973.93  4008.1 1974.12
  4029.2 1983.93  4050.4  1974.9  4083.4 1968.73  4134.8 1972.93  4205.7 1967.54
  4662.6 1959.37    4922 1962.46  4976.9 1951.56  4977.3 1951.06  4981.5 1951.56
  5064.9  1955.1  5093.9 1956.44  5183.4  1965.6  5463.7 1966.62  5515.2 1985.35
#Mann= 8 ,-1 , 0
  3653.6     .16       0  3665.1     .07       0  4050.4    .035       0
  4205.7     .07       0  4976.9     .07       0  4981.5     .07       0
  5064.9     .16       0  5093.9     .07       0
Bank Sta=4976.9,4981.5
XS Rating Curve= 0 ,0
Exp/Cntr=0.3,0.1

Type RM Length L Ch R = 1 ,4818    ,624,624,624
BEGIN DESCRIPTION:
Plum Creek Trib8 6.0
END DESCRIPTION:
XS GIS Cut Line= 3
      1401012.75      6929772.87      1400960.89      6928240.55
       1400785.7      6927608.59
#Sta/Elev= 30
  3466.8 2016.92  3511.7 2014.94  3542.2 2006.66  3561.7 2011.78  3641.8 1996.21
  3681.8 1978.69  3781.9 1979.96  3821.9 1967.84  4039.4 1978.72    4122 1970.25
    4211 1973.42  4532.3 1959.33  4552.3  1960.4  4592.3 1977.68  4642.3 1978.71
  4702.4 1943.57  4760.1 1941.96  4760.4 1941.46  4764.7 1941.96  4782.4 1943.92
  4802.4 1958.44  4862.5 1979.62  4902.5 1977.03  4940.6 1955.21  4972.5 1949.02
  5087.9 1958.45  5305.8 1961.54    5455 1962.58    5549 1962.69  5655.8 1963.37
#Mann= 11 ,-1 , 0
  3466.8     .16       0  3542.2     .07       0  4039.4    .035       0
    4211     .07       0  4760.1     .07       0  4764.7     .07       0
  4940.6     .16       0  5087.9     .07       0  5305.8    .035       0
    5455     .07       0    5549    .035       0
Bank Sta=4760.1,4764.7
XS Rating Curve= 0 ,0
Exp/Cntr=0.3,0.1

Type RM Length L Ch R = 1 ,4194    ,25,25,25
BEGIN DESCRIPTION:
Mapping XS 02ff63fe
END DESCRIPTION:
XS GIS Cut Line= 4
        1401347.      6928991.16      1401410.74      6928278.07
       1401446.6      6927967.32      1401609.91      6927122.91
#Sta/Elev= 30
  3947.7 1971.26  4006.1 1968.54  4021.1 1966.54  4141.6 1967.15  4180.3 1964.54
  4201.4 1961.98  4206.4 1965.03  4211.9 1965.13  4252.1 1961.67  4317.8 1960.17
  4322.8 1964.48  4392.6 1957.59  4426.7 1956.97  4427.1 1956.47  4431.7 1956.97
  4434.2 1963.82  4452.9 1964.74  4540.6 1961.68  4583.4 1963.41  4613.5 1959.38
    4657 1962.18  4788.9 1960.17  5026.7 1958.29  5303.5 1959.56  5459.4 1960.08
    5728 1960.86  5777.8 1963.11  5810.9 1964.87  5831.3 1972.73  5836.5 1978.25
#Mann= 9 ,-1 , 0
  3947.7     .07       0  4006.1    .035       0  4180.3     .07       0
  4426.7     .07       0  4431.7     .07       0  4788.9    .035       0
  5303.5     .07       0  5459.4    .035       0  5777.8     .07       0
Bank Sta=4426.7,4431.7
XS Rating Curve= 0 ,0
Exp/Cntr=0.3,0.1

Type RM Length L Ch R = 1 ,4169    ,524,524,524
BEGIN DESCRIPTION:
Mapping XS 84b0d8b0
END DESCRIPTION:
XS GIS Cut Line= 5
      1401430.66      6928987.18      1401430.96      6928582.96
      1401474.95      6927938.08      1401559.43      6927518.72
       1401693.6      6927106.81
#Sta/Elev= 30
  3949.4 1966.34  4008.6 1968.84  4028.6 1964.91  4062.2  1965.8  4108.6 1967.06
  4118.6 1965.76  4221.9 1966.07  4570.4 1963.31  4849.7 1958.51  4899.9 1959.22
  4919.9 1955.89  4926.1 1956.98  4928.6 1948.12    4929 1947.62  4933.6 1948.12
    4950 1954.34    4980 1956.74  5002.6 1955.59  5020.5 1958.02  5025.6 1952.72
  5071.3 1958.08  5076.4 1955.75    5297 1959.88  5357.1 1959.92  5376.9 1954.67
  5381.3 1954.45  5397.9 1959.78  5425.6 1960.79  5439.1 1958.52    5861 1961.98
#Mann= 8 ,-1 , 0
  3949.4     .07       0  4062.2    .035       0  4221.9     .07       0
  4570.4     .07       0  4928.6     .07       0  4933.6     .07       0
    5297     .07       0  5376.9    .035       0
Bank Sta=4928.6,4933.6
XS Rating Curve= 0 ,0
Exp/Cntr=0.3,0.1

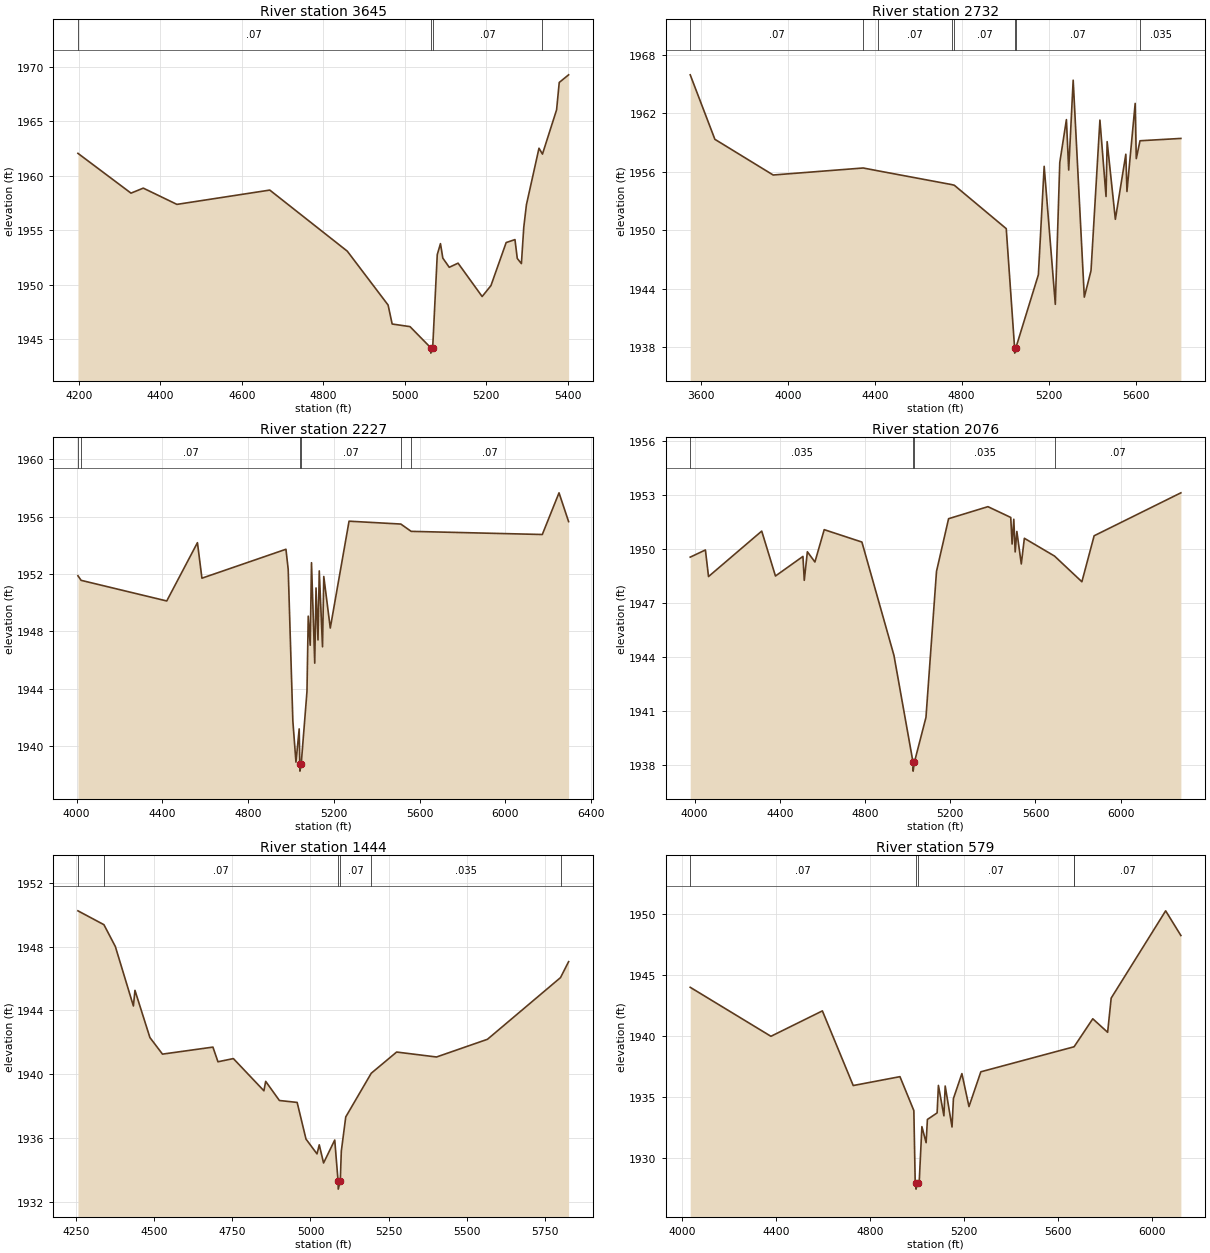
Type RM Length L Ch R = 1 ,3645    ,913,913,913
BEGIN DESCRIPTION:
Plum Creek Trib8 3.0
END DESCRIPTION:
XS GIS Cut Line= 3
        1401855.      6928488.04        1401905.        6927688.
      1401705.01      6927338.01
#Sta/Elev= 30
  4197.9 1962.04  4328.2 1958.39  4358.3 1958.85  4440.9 1957.36  4668.9 1958.67
  4859.2 1953.07  4959.4 1948.13  4969.4 1946.39  5013.2 1946.15  5063.9 1944.22
  5064.3 1943.72  5068.9 1944.22  5080.1 1952.75    5088 1953.76  5093.8 1952.43
  5109.6 1951.59  5131.2 1951.97  5190.3 1948.91  5211.9 1949.91  5249.3 1953.86
  5270.9 1954.13  5276.6  1952.4  5286.7 1951.93  5292.5 1955.25    5299 1957.32
  5329.9 1962.51  5338.4 1961.97  5373.1 1966.03  5379.6 1968.54  5402.6 1969.24
#Mann= 4 ,-1 , 0
  4197.9     .07       0  5063.9      .1       0  5068.9     .07       0
  5338.4    .035       0
Bank Sta=5063.9,5068.9
XS Rating Curve= 0 ,0
Exp/Cntr=0.3,0.1

Type RM Length L Ch R = 1 ,2732    ,505,505,505
BEGIN DESCRIPTION:
Plum Creek Trib8 2.0
END DESCRIPTION:
XS GIS Cut Line= 3
        1402655.      6928737.98        1402305.        6927338.
      1402123.87      6926545.09
#Sta/Elev= 30
  3551.7 1965.95  3665.1 1959.34  3933.1 1955.68  4347.2  1956.4  4417.5  1956.1
  4753.6  1954.7  4766.2 1954.63    5005 1950.18  5043.5 1937.92  5043.9 1937.42
  5048.6 1937.92  5152.8 1945.46  5179.4 1956.57  5230.7 1942.42  5251.2 1956.96
  5281.7 1961.36  5292.2 1956.19  5312.8  1965.4    5364 1943.16  5394.8 1945.87
  5435.8 1961.31  5463.9 1953.48    5469  1959.1  5506.8 1951.14  5554.9 1957.81
  5560.1 1953.99  5597.9 1963.02    5603 1957.36  5620.1 1959.19  5808.1 1959.43
#Mann= 8 ,-1 , 0
  3551.7     .07       0  4347.2     .16       0  4417.5     .07       0
  4753.6     .16       0  4766.2     .07       0  5043.5     .07       0
  5048.6     .07       0  5620.1    .035       0
Bank Sta=5043.5,5048.6
XS Rating Curve= 0 ,0
Exp/Cntr=0.3,0.1

Type RM Length L Ch R = 1 ,2227    ,151,151,151
BEGIN DESCRIPTION:
Mapping XS 06449524
END DESCRIPTION:
XS GIS Cut Line= 4
      1403227.43      6927851.82      1402673.65        6927055.
      1402466.48      6926736.29       1401860.9      6926019.16
#Sta/Elev= 30
  4006.4 1951.88  4021.2 1951.56  4420.7 1950.12  4563.9 1954.19  4584.8 1951.71
  4976.8 1953.73  4987.3 1952.33    5009 1941.75  5023.5 1938.87  5038.6 1941.19
  5041.4 1938.74  5041.9 1938.24    5048 1938.74  5074.9  1943.8  5080.8 1949.06
    5090 1947.03    5096 1952.79  5111.1 1945.78  5117.1 1951.03  5126.3  1947.4
  5132.2 1952.22  5147.4 1946.92  5153.3 1951.83  5183.6 1948.23  5271.2 1955.69
  5512.7 1955.49  5560.9 1954.98  6172.8 1954.76  6250.8 1957.67  6295.5 1955.66
#Mann= 6 ,-1 , 0
  4006.4    .035       0  4021.2     .07       0  5041.4     .07       0
    5048     .07       0  5512.7    .035       0  5560.9     .07       0
Bank Sta=5041.4,5048
XS Rating Curve= 0 ,0
Exp/Cntr=0.3,0.1

Type RM Length L Ch R = 1 ,2076    ,632,632,632
BEGIN DESCRIPTION:
Mapping XS 386aa2f8
END DESCRIPTION:
XS GIS Cut Line= 3
      1403382.79      6927740.24      1402773.25      6926935.49
      1401957.13      6925932.26
#Sta/Elev= 30
  3979.6 1949.55  4050.9 1949.95  4065.5 1948.47  4315.2    1951  4379.6  1948.5
  4508.6 1949.59  4514.9 1948.26  4529.4 1949.85  4564.8 1949.28  4608.5 1951.08
  4785.4 1950.39  4935.8 1944.08  5025.2 1938.14  5025.7 1937.64  5031.8 1938.14
    5086 1940.63  5135.5 1948.76  5192.2 1951.69  5376.8 1952.36  5483.9 1951.76
  5490.3 1950.28  5498.2 1951.66  5504.7 1949.84  5512.6 1950.98  5533.4 1949.17
  5547.8  1950.6  5689.4 1949.61  5817.8 1948.18  5875.3 1950.74  6282.4 1953.13
#Mann= 4 ,-1 , 0
  3979.6    .035       0  5025.2    .035       0  5031.8    .035       0
  5689.4     .07       0
Bank Sta=5025.2,5031.8
XS Rating Curve= 0 ,0
Exp/Cntr=0.3,0.1

Type RM Length L Ch R = 1 ,1444    ,865,865,865
BEGIN DESCRIPTION:
Mapping XS 4c2ca56f
END DESCRIPTION:
XS GIS Cut Line= 4
      1402992.36      6927066.97      1403020.25       6926784.1
      1403179.61      6926493.27       1402478.4      6925847.84
#Sta/Elev= 30
  4256.6 1950.25  4339.7 1949.38  4376.2 1948.01  4433.9 1944.28  4438.9 1945.26
  4486.7  1942.3  4526.9 1941.26  4688.2  1941.7  4704.3 1940.78  4753.6 1940.98
  4851.2 1938.96  4856.9 1939.55  4900.8 1938.35  4957.5 1938.23  4985.8 1935.93
    5021    1935  5028.2 1935.57    5042 1934.43  5077.7 1935.87  5088.4 1933.29
  5088.9 1932.79  5095.4 1933.29  5098.7 1935.17  5112.9 1937.32  5194.4 1940.06
  5275.6 1941.39  5403.2 1941.08    5566 1942.19  5799.6 1946.06  5825.5 1947.06
#Mann= 6 ,-1 , 0
  4256.6    .035       0  4339.7     .07       0  5088.4     .07       0
  5095.4     .07       0  5194.4    .035       0  5799.6     .07       0
Bank Sta=5088.4,5095.4
XS Rating Curve= 0 ,0
Exp/Cntr=0.3,0.1

Type RM Length L Ch R = 1 ,579     ,34,34,34
BEGIN DESCRIPTION:
Mapping XS 04840cdc
END DESCRIPTION:
XS GIS Cut Line= 4
       1403118.2       6926768.2       1403591.2      6925932.39
      1403648.19      6925801.32      1402821.84      6925259.92
#Sta/Elev= 30
  4033.4 1944.01  4377.4 1939.98  4596.7 1942.07  4728.1 1935.93  4927.3 1936.66
  4986.5 1933.87  4992.2 1928.03  4995.3 1927.91  4995.8 1927.41  5002.4 1927.91
  5009.5 1928.05  5020.8 1932.55  5038.8 1931.23  5044.3 1933.14  5085.7 1933.68
  5091.2 1935.94  5114.6 1933.44  5120.1 1935.89  5149.2 1932.52  5155.2 1934.86
  5191.3 1936.91  5221.5  1934.2    5272 1937.06  5669.7 1939.12  5670.2 1939.14
  5749.1 1941.42  5812.4 1940.31  5827.5 1943.12  6059.7  1950.3  6124.6 1948.27
#Mann= 5 ,-1 , 0
  4033.4     .07       0  4995.3     .07       0  5002.4     .07       0
  5669.7    .035       0  5670.2     .07       0
Bank Sta=4995.3,5002.4
XS Rating Curve= 0 ,0
Exp/Cntr=0.3,0.1

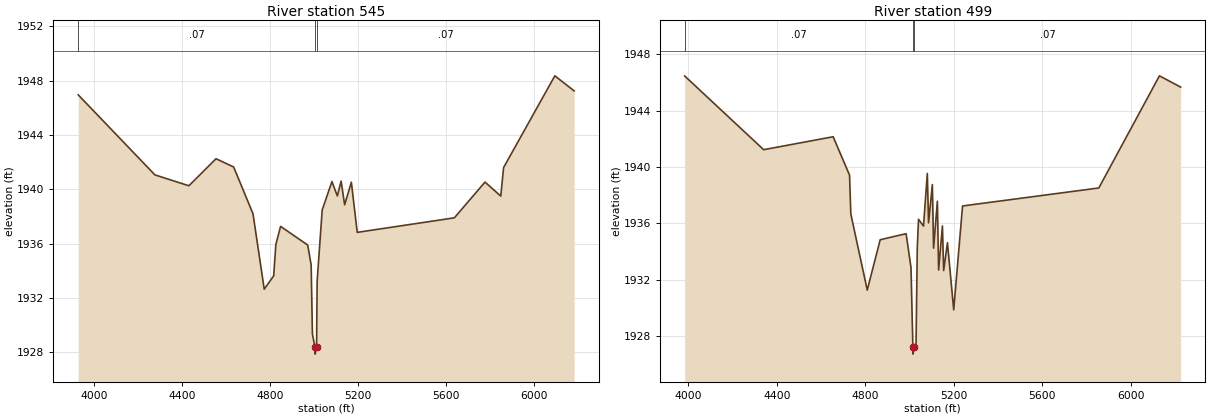
Type RM Length L Ch R = 1 ,545     ,46,46,46
BEGIN DESCRIPTION:
Mapping XS 16c4535e
END DESCRIPTION:
XS GIS Cut Line= 6
      1403064.07      6926883.69      1403605.09      6925957.88
      1403636.17      6925913.29      1403658.97      6925835.36
       1403677.6      6925784.13      1402844.95       6925246.3
#Sta/Elev= 30
  3927.7 1946.96  4276.2 1941.07  4430.7 1940.27  4553.9 1942.26  4634.1 1941.65
  4721.9 1938.21    4773 1932.66  4815.9 1933.64  4825.8 1935.95  4847.3 1937.28
  4970.5 1935.91  4986.2 1934.45    4992 1929.35  5003.7 1928.38  5004.2 1927.88
  5010.8 1928.38  5013.4 1933.23  5036.4 1938.49  5080.7 1940.58  5105.2 1939.52
  5122.4 1940.61  5138.3 1938.87  5168.9 1940.53  5195.6 1936.84    5637 1937.91
  5776.2 1940.54  5847.9 1939.51  5860.7 1941.61  6093.6 1948.36  6181.3 1947.25
#Mann= 3 ,-1 , 0
  3927.7     .07       0  5003.7     .07       0  5010.8     .07       0
Bank Sta=5003.7,5010.8
XS Rating Curve= 0 ,0
Exp/Cntr=0.3,0.1

Type RM Length L Ch R = 1 ,499     ,0,0,0
BEGIN DESCRIPTION:
Mapping XS 309a9a75
END DESCRIPTION:
XS GIS Cut Line= 5
      1403087.98       6926879.7      1403605.89      6926003.25
      1403713.45      6925776.17      1403633.77      6925708.44
      1402909.34      6925230.79
#Sta/Elev= 30
  3983.1 1946.47  4340.1 1941.23  4654.2 1942.15  4728.3 1939.42  4734.1 1936.66
  4808.3 1931.25  4866.8 1934.83  4983.9 1935.26  5006.1 1932.85  5014.5  1927.2
    5015  1926.7  5021.6  1927.2  5028.8 1927.36  5034.4 1934.25  5040.1 1936.28
  5062.6  1935.8  5079.8 1939.54  5085.4 1936.03  5102.6 1938.75  5108.1 1934.23
  5125.3 1937.57  5130.9 1932.68  5148.1 1935.81  5153.6 1932.64  5170.8 1934.62
  5199.1 1929.85  5239.1 1937.23    5855 1938.51    6129 1946.48  6224.7 1945.68
#Mann= 3 ,-1 , 0
  3983.1     .07       0  5014.5     .07       0  5021.6     .07       0
Bank Sta=5014.5,5021.6
XS Rating Curve= 0 ,0
Exp/Cntr=0.3,0.1

Chan Stop Cuts=-1
Use User Specified Reach Order=0
Composite Channel Slope=5