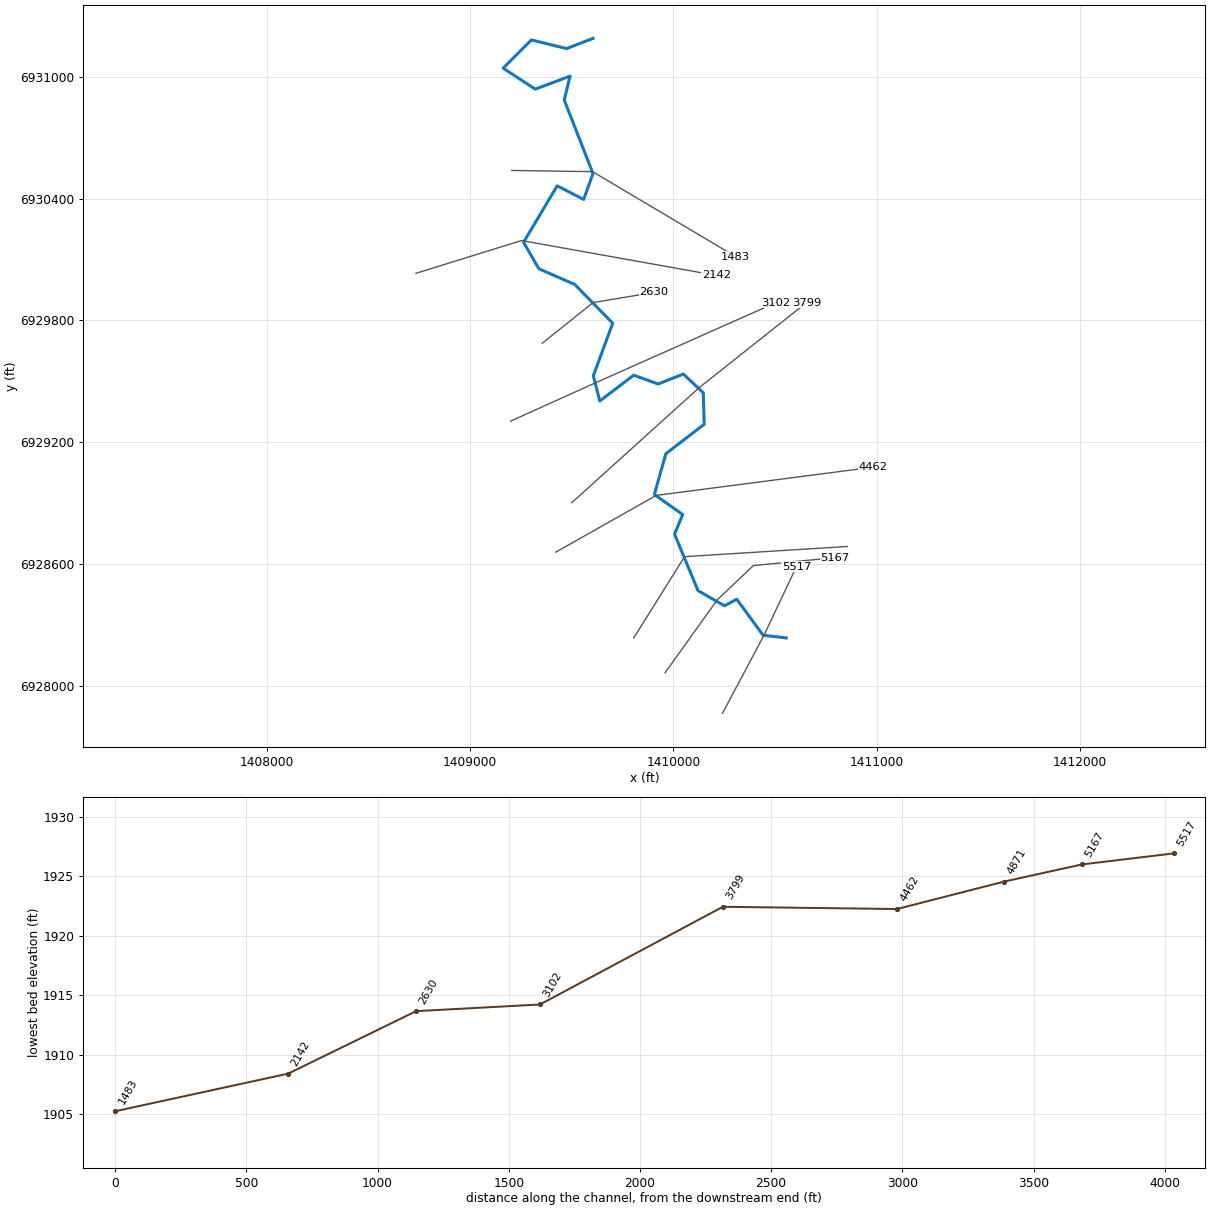
--- Plum Creek Trib9.prj (project) ---

Proj Title=Plum Creek Trib9 Base Level Engineering
Current Plan=p01
Default Exp/Contr=0.3,0.1
English Units
Geom File=g01
Flow File=f01
Plan File=p01
BEGIN DESCRIPTION:
Plum Creek Trib9
END DESCRIPTION:

--- Plum Creek Trib9.p01 (plan) ---

Plan Title=Multiple Run
Short Identifier=Multiple
Geom File=g01
Flow File=f01
Subcritical Flow
K Sum by GR= 0
Std Step Tol= 0.01
Critical Tol= 0.01
Num of Std Step Trials= 20
Max Error Tol= 0.3
Flow Tol Ratio= 0.001
Split Flow NTrial= 30
Split Flow Tol= 0.02
Split Flow Ratio= 0.02
Log Output Level= 0
Friction Slope Method= 1
Unsteady Friction Slope Method= 2
Unsteady Bridges Friction Slope Method= 1
Parabolic Critical Depth
Global Vel Dist=  1 , 1 , 1
Global Log Level= 0
CheckData=True
Encroach Param= -1, 0, 0, 0
BEGIN DESCRIPTION:
Multiple Run
END DESCRIPTION:

--- Plum Creek Trib9.f01 (steady flow) ---

Flow Title=Multiple
Number of Profiles=7
Profile Names=10-year,25-year,50-year,1pct_min,100-year,1pct_plu,500-year
River Rch & RM= Plum Creek Trib9,Reach-1,5517
     290     414     518     323     644    1285    1008
River Rch & RM= Plum Creek Trib9,Reach-1,5167
     372     535     674     422     842    1680    1333
Boundary for River Rch & Prof#=Plum Creek Trib9,Reach-1,1
Up Type=0
Dn Type=3
Dn Slope=0.005
Boundary for River Rch & Prof#=Plum Creek Trib9,Reach-1,2
Up Type=0
Dn Type=3
Dn Slope=0.005
Boundary for River Rch & Prof#=Plum Creek Trib9,Reach-1,3
Up Type=0
Dn Type=3
Dn Slope=0.005
Boundary for River Rch & Prof#=Plum Creek Trib9,Reach-1,4
Up Type=0
Dn Type=3
Dn Slope=0.005
Boundary for River Rch & Prof#=Plum Creek Trib9,Reach-1,5
Up Type=0
Dn Type=3
Dn Slope=0.005
Boundary for River Rch & Prof#=Plum Creek Trib9,Reach-1,6
Up Type=0
Dn Type=3
Dn Slope=0.005
Boundary for River Rch & Prof#=Plum Creek Trib9,Reach-1,7
Up Type=0
Dn Type=3
Dn Slope=0.005

--- Plum Creek Trib9.g01 (geometry) ---

Geom Title=Existing Conditions

River Reach=Plum Creek Trib9,Reach-1
Reach XY= 30
      1410555.00      6928238.00      1410441.31      6928251.44
      1410311.69      6928428.71      1410251.77      6928396.25
      1410121.30      6928470.86      1410005.80      6928748.71
      1410045.97      6928845.01      1409906.54      6928943.85
      1409962.85      6929144.19      1410151.56      6929289.25
      1410147.20      6929444.21      1410048.98      6929536.39
      1409925.05      6929487.43      1409804.90      6929530.68
      1409637.86      6929404.00      1409606.08      6929527.44
      1409701.54      6929786.50      1409514.68      6929977.24
      1409337.94      6930054.49      1409263.04      6930184.68
      1409428.33      6930462.33      1409558.62      6930395.49
      1409604.62      6930522.71      1409463.10      6930884.71
      1409491.87      6931002.06      1409320.41      6930938.02
      1409162.51      6931041.15      1409301.58      6931180.21
      1409475.14      6931137.59      1409605.00      6931188.00

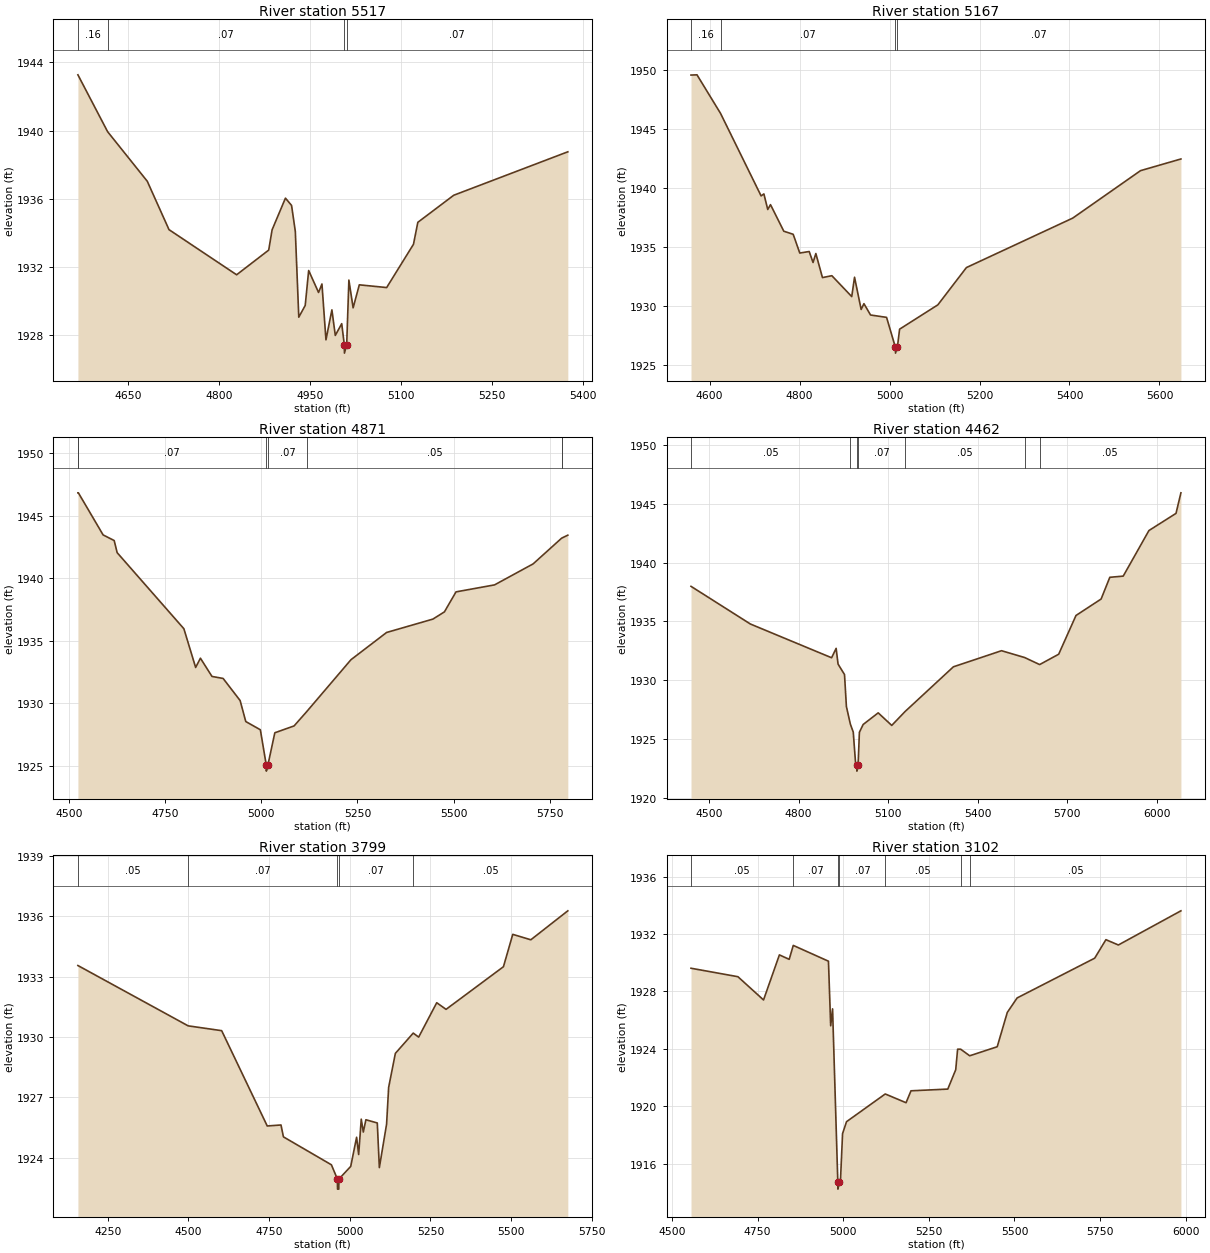
Type RM Length L Ch R = 1,5517,350,350,350
BEGIN DESCRIPTION:
Plum Creek Trib9 7.0
END DESCRIPTION:
XS GIS Cut Line= 3
      1410241.24      6927867.02      1410444.67      6928249.03
      1410605.01      6928588.02
#Sta/Elev= 30
  4567.2 1943.27  4616.2 1939.93  4681.6 1937.02  4717.4 1934.18  4828.9 1931.53
  4881.8 1932.98  4887.4 1934.17  4909.4 1936.03  4919.5 1935.60  4925.7 1934.07
  4931.4 1929.04  4942.0 1929.73  4947.7 1931.78  4964.0 1930.49  4969.6 1930.99
  4976.2 1927.71  4986.0 1929.47  4991.6 1927.97  5002.2 1928.66  5006.4 1927.43
  5006.7 1926.93  5010.4 1927.43  5014.0 1931.22  5021.0 1929.59  5031.2 1930.94
  5076.3 1930.78  5120.5 1933.32  5127.7 1934.61  5186.9 1936.20  5375.0 1938.75
#Mann=4,-1,0
  4567.2    0.16       0  4616.2    0.07       0  5006.4    0.07       0
  5010.4    0.07       0
Bank Sta=5006.4,5010.4
Exp/Cntr=0.3,0.1

Type RM Length L Ch R = 1,5167,296,296,296
BEGIN DESCRIPTION:
Mapping XS 6f2865b4
END DESCRIPTION:
XS GIS Cut Line= 4
      1409959.09      6928066.62      1410215.17      6928424.70
      1410393.13      6928593.97      1410794.40      6928633.02
#Sta/Elev= 30
  4558.7 1949.56  4572.0 1949.58  4624.4 1946.31  4714.5 1939.32  4720.7 1939.49
  4729.3 1938.17  4735.4 1938.58  4764.9 1936.33  4785.8 1936.07  4800.5 1934.48
  4821.4 1934.61  4830.0 1933.68  4836.2 1934.44  4850.9 1932.40  4871.8 1932.56
  4916.0 1930.79  4922.2 1932.43  4936.9 1929.70  4943.1 1930.19  4957.8 1929.23
  4993.4 1929.03  5013.0 1926.50  5013.3 1926.00  5017.4 1926.50  5022.4 1928.03
  5107.4 1930.09  5170.9 1933.25  5407.2 1937.44  5557.9 1941.46  5647.7 1942.45
#Mann=4,-1,0
  4558.7    0.16       0  4624.4    0.07       0  5013.0    0.07       0
  5017.4    0.07       0
Bank Sta=5013,5017.4
Exp/Cntr=0.3,0.1

Type RM Length L Ch R = 1,4871,409,409,409
BEGIN DESCRIPTION:
Plum Creek Trib9 6.0
END DESCRIPTION:
XS GIS Cut Line= 3
      1409805.00      6928238.00      1410055.00      6928638.00
      1410855.04      6928688.00
#Sta/Elev= 30
  4523.4 1946.84  4524.6 1946.84  4588.9 1943.47  4617.7 1943.02  4625.4 1942.05
  4798.8 1935.96  4829.4 1932.86  4841.8 1933.60  4871.9 1932.14  4900.8 1931.98
  4945.0 1930.21  4959.7 1928.53  4997.6 1927.87  5012.9 1925.06  5013.2 1924.56
  5017.3 1925.06  5035.2 1927.63  5085.3 1928.18  5118.5 1929.34  5233.1 1933.48
  5325.7 1935.66  5446.0 1936.73  5476.0 1937.31  5506.1 1938.91  5606.3 1939.47
  5706.5 1941.15  5781.0 1943.22  5781.1 1943.22  5781.2 1943.22  5796.7 1943.45
#Mann=8,-1,0
  4523.4    0.16       0  4524.6    0.07       0  5012.9    0.07       0
  5017.3    0.07       0  5118.5    0.05       0  5781.0    0.07       0
  5781.1   0.035       0  5781.2    0.07       0
Bank Sta=5012.9,5017.3
Exp/Cntr=0.3,0.1

Type RM Length L Ch R = 1,4462,663,663,663
BEGIN DESCRIPTION:
Mapping XS db525d75
END DESCRIPTION:
XS GIS Cut Line= 3
      1409421.50      6928660.07      1409915.81      6928939.45
      1410981.34      6929078.01
#Sta/Elev= 30
  4439.2 1937.98  4638.5 1934.77  4910.5 1931.90  4925.7 1932.70  4932.2 1931.36
  4953.8 1930.47  4960.1 1927.75  4973.4 1926.25  4983.1 1925.57  4991.4 1922.75
  4994.9 1922.75  4995.2 1922.25  4999.3 1922.75  5003.7 1925.56  5016.3 1926.22
  5066.7 1927.21  5112.1 1926.14  5156.7 1927.32  5318.8 1931.13  5480.1 1932.50
  5557.6 1931.92  5607.9 1931.32  5671.7 1932.20  5729.8 1935.50  5814.0 1936.90
  5843.2 1938.75  5888.1 1938.85  5974.3 1942.73  6065.0 1944.19  6081.5 1945.94
#Mann=7,-1,0
  4439.2    0.05       0  4973.4    0.07       0  4994.9    0.07       0
  4999.3    0.07       0  5156.7    0.05       0  5557.6    0.07       0
  5607.9    0.05       0
Bank Sta=4994.9,4999.3
Exp/Cntr=0.3,0.1

Type RM Length L Ch R = 1,3799,697,697,697
BEGIN DESCRIPTION:
Plum Creek Trib9 4.0
END DESCRIPTION:
XS GIS Cut Line= 3
      1409500.26      6928903.62      1410125.52      6929468.29
      1410654.96      6929887.97
#Sta/Elev= 30
  4157.5 1933.56  4499.1 1930.56  4603.0 1930.32  4744.2 1925.58  4786.8 1925.63
  4794.3 1925.04  4943.0 1923.65  4961.6 1922.94  4962.0 1922.44  4965.9 1922.44
  4966.2 1922.94  5002.9 1923.57  5021.1 1925.02  5027.5 1924.16  5035.5 1925.92
  5041.9 1925.28  5049.9 1925.89  5085.2 1925.73  5091.6 1923.51  5114.0 1925.67
  5120.4 1927.50  5141.2 1929.19  5196.6 1930.20  5213.4 1930.00  5269.4 1931.71
  5298.3 1931.38  5476.1 1933.50  5505.0 1935.11  5561.0 1934.84  5675.6 1936.28
#Mann=5,-1,0
  4157.5    0.05       0  4499.1    0.07       0  4961.6    0.07       0
  4966.2    0.07       0  5196.6    0.05       0
Bank Sta=4961.6,4966.2
Exp/Cntr=0.3,0.1

Type RM Length L Ch R = 1,3102,472,472,472
BEGIN DESCRIPTION:
Plum Creek Trib9 3.0
END DESCRIPTION:
XS GIS Cut Line= 3
      1409199.33      6929304.82      1409605.00      6929488.00
      1410505.00      6929888.00
#Sta/Elev= 30
  4555.8 1929.61  4692.7 1929.02  4767.5 1927.40  4813.8 1930.54  4842.4 1930.23
  4854.3 1931.20  4957.0 1930.10  4963.5 1925.60  4969.0 1926.78  4984.3 1914.72
  4984.6 1914.22  4988.9 1914.72  4992.1 1914.84  4998.2 1918.09  5009.8 1918.92
  5122.8 1920.85  5183.5 1920.24  5197.9 1921.07  5305.3 1921.19  5328.5 1922.54
  5334.0 1923.97  5342.8 1923.97  5369.3 1923.51  5449.6 1924.14  5479.0 1926.53
  5507.7 1927.54  5734.1 1930.31  5766.9 1931.60  5803.2 1931.23  5985.8 1933.61
#Mann=7,-1,0
  4555.8    0.05       0  4854.3    0.07       0  4984.3    0.07       0
  4988.9    0.07       0  5122.8    0.05       0  5342.8    0.07       0
  5369.3    0.05       0
Bank Sta=4984.3,4988.9
Exp/Cntr=0.3,0.1

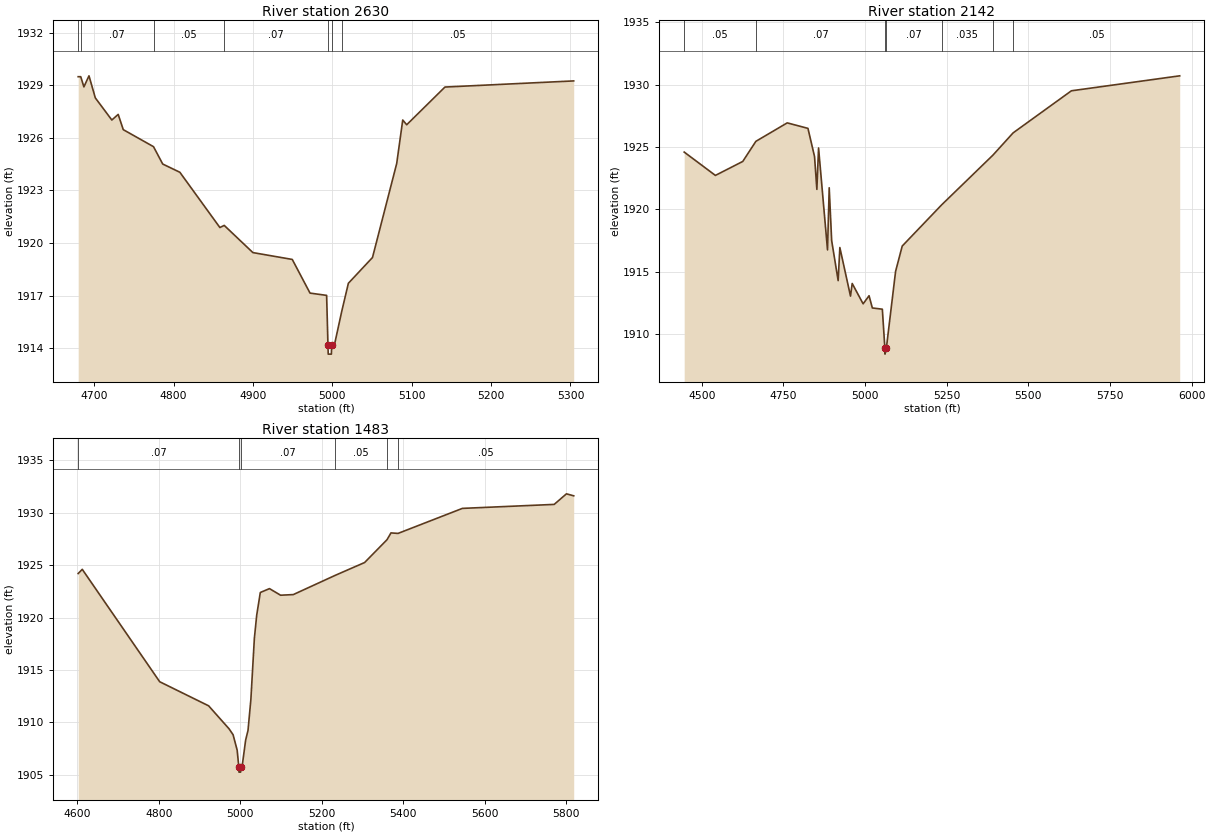
Type RM Length L Ch R = 1,2630,488,488,488
BEGIN DESCRIPTION:
Plum Creek Trib9 2.0
END DESCRIPTION:
XS GIS Cut Line= 3
      1409355.00      6929688.00      1409605.00      6929888.00
      1409905.00      6929938.00
#Sta/Elev= 30
  4679.8 1929.48  4683.0 1929.48  4687.0 1928.90  4693.4 1929.53  4701.4 1928.27
  4722.2 1927.01  4730.2 1927.33  4736.6 1926.46  4774.7 1925.49  4786.3 1924.50
  4807.9 1924.03  4858.3 1920.88  4863.8 1921.00  4899.9 1919.45  4949.5 1919.06
  4971.9 1917.14  4992.8 1917.01  4994.5 1914.16  4994.8 1913.66  4998.8 1913.66
  4999.1 1914.16  5002.5 1914.16  5011.8 1916.09  5020.2 1917.70  5050.6 1919.17
  5081.1 1924.53  5088.7 1927.01  5093.7 1926.74  5141.9 1928.89  5304.1 1929.24
#Mann=7,-1,0
  4679.8    0.05       0  4683.0    0.07       0  4774.7    0.05       0
  4863.8    0.07       0  4994.5    0.07       0  4999.1    0.07       0
  5011.8    0.05       0
Bank Sta=4994.5,4999.1
Exp/Cntr=0.3,0.1

Type RM Length L Ch R = 1,2142,659,659,659
BEGIN DESCRIPTION:
Mapping XS 66dc2118
END DESCRIPTION:
XS GIS Cut Line= 3
      1408733.70      6930032.02      1409253.10      6930193.22
      1410211.52      6930021.56
#Sta/Elev= 30
  4446.0 1924.59  4541.6 1922.72  4625.4 1923.84  4665.5 1925.45  4761.5 1926.93
  4825.0 1926.49  4845.2 1924.23  4852.3 1921.60  4857.5 1924.92  4884.9 1916.75
  4890.1 1921.73  4897.6 1917.50  4917.5 1914.29  4922.7 1916.94  4955.3 1913.05
  4960.5 1914.06  4994.0 1912.43  5012.1 1913.08  5022.2 1912.10  5052.8 1912.00
  5060.5 1908.90  5060.9 1908.40  5065.2 1908.90  5093.4 1915.03  5113.7 1917.06
  5234.4 1920.36  5391.3 1924.34  5453.4 1926.13  5631.8 1929.50  5963.5 1930.70
#Mann=7,-1,0
  4446.0    0.05       0  4665.5    0.07       0  5060.5    0.07       0
  5065.2    0.07       0  5234.4   0.035       0  5391.3    0.07       0
  5453.4    0.05       0
Bank Sta=5060.5,5065.2
Exp/Cntr=0.3,0.1

Type RM Length L Ch R = 1,1483,0,0,0
BEGIN DESCRIPTION:
Plum Creek Trib9 1.0
END DESCRIPTION:
XS GIS Cut Line= 3
      1409204.98      6930538.00      1409602.84      6930532.02
      1410306.22      6930114.43
#Sta/Elev= 30
  4602.1 1924.20  4612.1 1924.60  4802.1 1913.87  4922.2 1911.57  4972.2 1909.38
  4982.2 1908.81  4992.2 1907.34  4996.2 1905.74  4996.6 1905.24  5000.6 1905.24
  5000.9 1905.74  5004.2 1905.74  5013.0 1908.30  5018.8 1909.22  5025.8 1912.16
  5034.4 1918.01  5040.2 1920.24  5049.0 1922.39  5071.5 1922.76  5098.7 1922.13
  5129.9 1922.19  5233.0 1924.03  5304.9 1925.25  5359.9 1927.43  5369.6 1928.08
  5386.9 1928.03  5544.9 1930.42  5770.1 1930.80  5800.2 1931.81  5818.0 1931.62
#Mann=6,-1,0
  4602.1    0.07       0  4996.2    0.07       0  5000.9    0.07       0
  5233.0    0.05       0  5359.9   0.035       0  5386.9    0.05       0
Bank Sta=4996.2,5000.9
Exp/Cntr=0.3,0.1

Chan Stop Cuts=-1