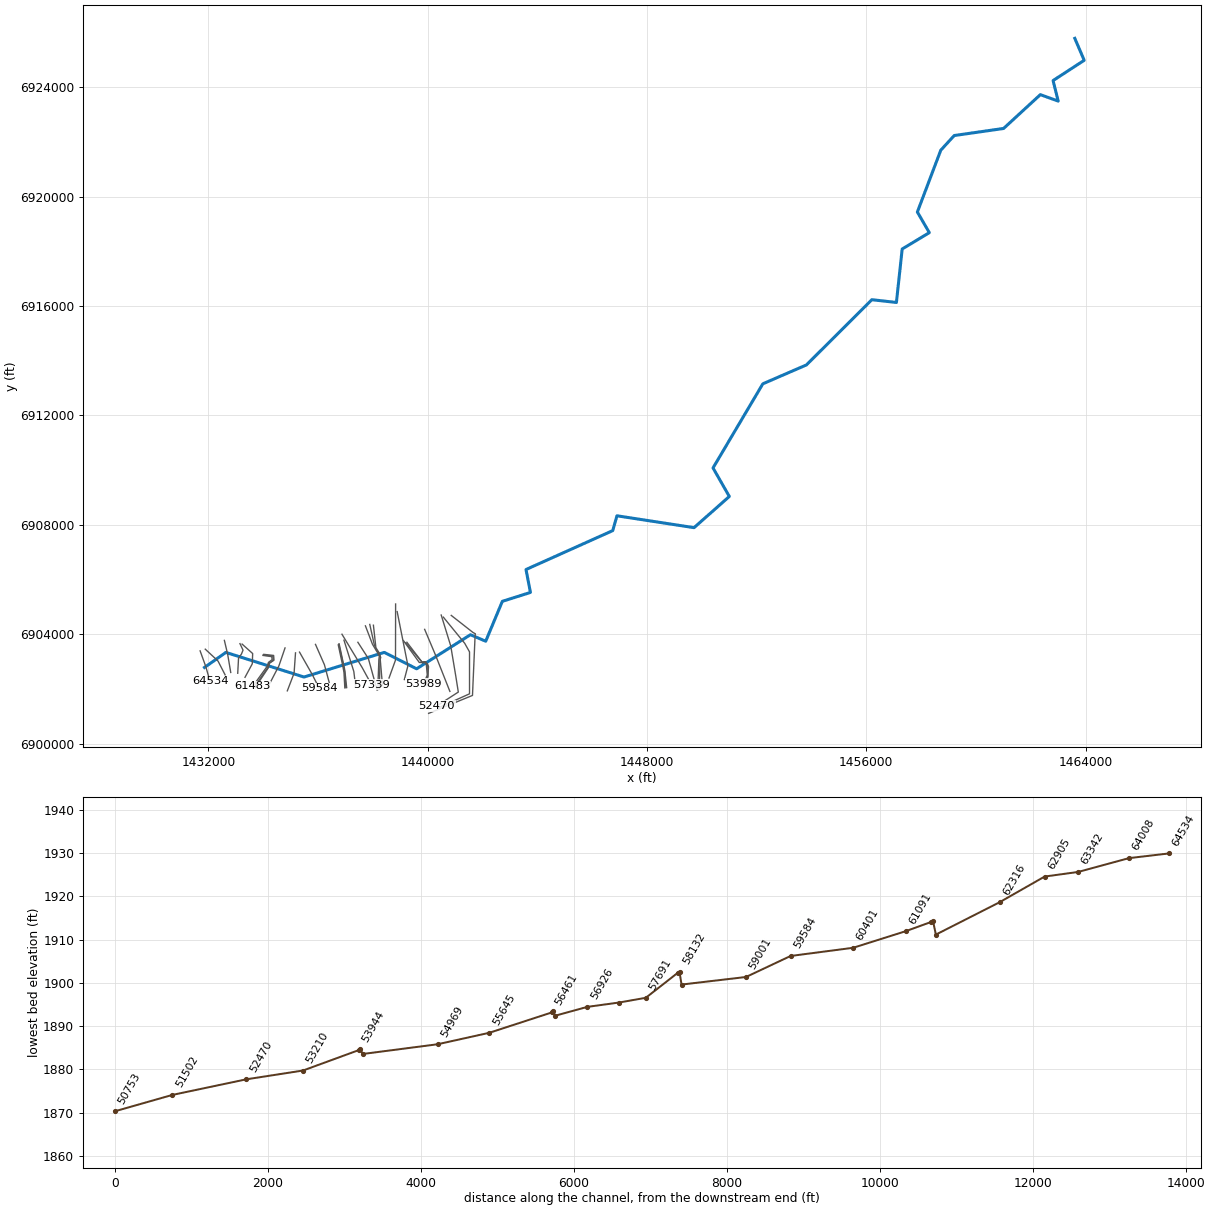
--- Raven Creek.prj (project) ---

Proj Title=Raven Creek Base Level Engineering
Current Plan=p01
Default Exp/Contr=0.3,0.1
English Units
Geom File=g01
Flow File=f01
Plan File=p01
Y Axis Title=Elevation
X Axis Title(PF)=Main Channel Distance
X Axis Title(XS)=Station
BEGIN DESCRIPTION:
Raven Creek
END DESCRIPTION:
DSS Export Rating Curves= 0
DSS Export Rating Curve Sorted= 0
DSS Export Volume Flow Curves= 0
DXF OffsetX= 0
DXF OffsetY= 0
DXF ScaleX= 1
DXF ScaleY= 10

--- Raven Creek.p01 (plan) ---

Plan Title=Multiple Run
Short Identifier=Multiple
Geom File=g01
Flow File=f01
Subcritical Flow
K Sum by GR= 0
Std Step Tol= 0.01
Critical Tol= 0.01
Num of Std Step Trials= 20
Max Error Tol= 0.3
Flow Tol Ratio= 0.001
Split Flow NTrial= 30
Split Flow Tol= 0.02
Split Flow Ratio= 0.02
Log Output Level= 0
Friction Slope Method= 1
Unsteady Friction Slope Method= 2
Unsteady Bridges Friction Slope Method= 1
Parabolic Critical Depth
Global Vel Dist=  1 , 1 , 1
Global Log Level= 0
CheckData=True
Encroach Param= -1, 0, 0, 0
BEGIN DESCRIPTION:
Multiple Run
END DESCRIPTION:

--- Raven Creek.f01 (steady flow) ---

Flow Title=Multiple
Program Version=4.10
Number of Profiles= 7
Profile Names=10-year,25-year,50-year,1pct_min,100-year,1pct_plu,500-year
River Rch & RM=Raven Creek,Reach-1         ,64534
     324     467     588     370     737    1471    1172
River Rch & RM=Raven Creek,Reach-1         ,63342
     425     619     786     497     991    1977    1594
River Rch & RM=Raven Creek,Reach-1         ,58158
     720    1067    1372     875    1746    3484    2866
River Rch & RM=Raven Creek,Reach-1         ,48361
     776    1150    1478     942    1879    3749    3078
River Rch & RM=Raven Creek,Reach-1         ,40215
     856    1267    1628    1037    2069    4129    3385
River Rch & RM=Raven Creek,Reach-1         ,38178
    1544    2336    3045    1964    3919    7819    6575
River Rch & RM=Raven Creek,Reach-1         ,28881
    1556    2353    3066    1976    3943    7867    6608
River Rch & RM=Raven Creek,Reach-1         ,25402
    1704    2580    3364    2170    4329    8638    7261
River Rch & RM=Raven Creek,Reach-1         ,19602
    1706    2576    3352    2157    4304    8588    7188
River Rch & RM=Raven Creek,Reach-1         ,17047
    1869    2825    3681    2371    4730    9438    7912
River Rch & RM=Raven Creek,Reach-1         ,5434
    1854    2800    3644    2344    4678    9333    7807
Boundary for River Rch & Prof#=Raven Creek,Reach-1         , 1
Up Type= 0
Dn Type= 3
Dn Slope=0.0036
Boundary for River Rch & Prof#=Raven Creek,Reach-1         , 2
Up Type= 0
Dn Type= 3
Dn Slope=0.0036
Boundary for River Rch & Prof#=Raven Creek,Reach-1         , 3
Up Type= 0
Dn Type= 3
Dn Slope=0.0036
Boundary for River Rch & Prof#=Raven Creek,Reach-1         , 4
Up Type= 0
Dn Type= 3
Dn Slope=0.0036
Boundary for River Rch & Prof#=Raven Creek,Reach-1         , 5
Up Type= 0
Dn Type= 3
Dn Slope=0.0036
Boundary for River Rch & Prof#=Raven Creek,Reach-1         , 6
Up Type= 0
Dn Type= 3
Dn Slope=0.0036
Boundary for River Rch & Prof#=Raven Creek,Reach-1         , 7
Up Type= 0
Dn Type= 3
Dn Slope=0.0036
DSS Import GetInterval= 0
DSS Import GetPeak= 0
DSS Import FillOption= 0

--- Raven Creek.g01 (geometry) ---

Geom Title=Existing Conditions
Program Version=4.10

River Reach=Raven Creek     ,Reach-1
Reach XY= 30
        1431855.        6902788.      1432634.66      6903338.29
      1435485.01      6902437.95      1438415.11      6903338.82
      1439593.28      6902739.05      1441556.56      6903984.26
      1442115.22       6903748.3      1442721.43      6905205.69
      1443746.17        6905531.      1443583.94      6906368.39
      1446747.42      6907790.96       1446902.7      6908332.91
      1449715.08      6907899.07       1451001.9      6909039.68
      1450407.14      6910082.03      1452224.35      6913158.04
        1453815.      6913848.61      1456202.25      6916232.71
      1457097.14      6916131.79      1457307.98      6918086.56
      1458297.52      6918684.43      1457861.92      6919438.01
      1458715.48       6921697.8      1459206.25      6922234.64
      1461007.98      6922493.39      1462348.05      6923729.16
      1462999.59      6923493.18      1462812.36      6924244.34
      1463947.36      6924984.33        1463605.        6925788.

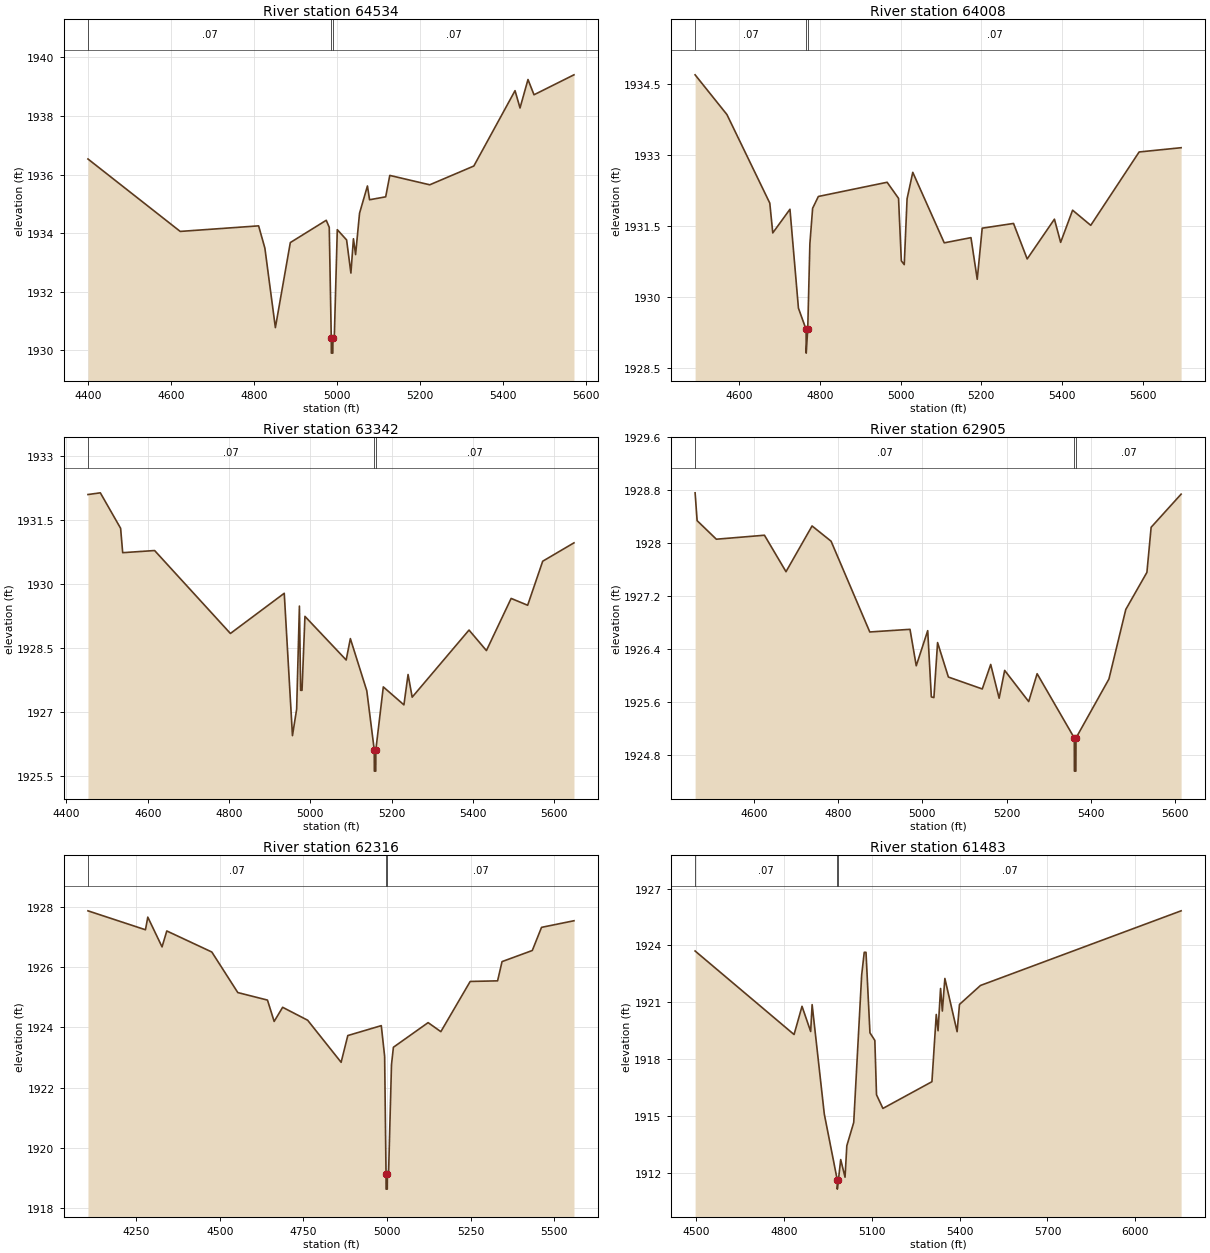
Type RM Length L Ch R = 1 ,64534   ,526,526,526
BEGIN DESCRIPTION:
Mapping XS 84fa5849
END DESCRIPTION:
XS GIS Cut Line= 3
      1431695.41      6903394.75      1431895.92      6902840.08
      1432056.99      6902281.55
#Sta/Elev= 30
  4400.3 1936.53  4622.6 1934.06  4811.5 1934.25  4826.6 1933.49  4851.9 1930.78
  4887.9 1933.68  4974.5 1934.44  4981.7  1934.2  4986.6 1930.41  4986.8 1929.91
  4990.3 1929.91  4990.6 1930.41  4993.8 1930.41  5001.1 1934.12  5023.5 1933.77
  5033.9 1932.64    5040 1933.81  5045.2 1933.27  5054.7 1934.68  5073.7 1935.61
  5078.9 1935.14  5117.7 1935.24  5127.6 1935.97  5223.9 1935.65  5330.1 1936.29
  5429.4 1938.86  5441.4 1938.27  5460.6 1939.24  5475.1 1938.72  5571.4  1939.4
#Mann= 3 ,-1 , 0
  4400.3     .07       0  4986.6     .07       0  4990.6     .07       0
Bank Sta=4986.6,4990.6
XS Rating Curve= 0 ,0
Exp/Cntr=0.3,0.1

Type RM Length L Ch R = 1 ,64008   ,666,666,666
BEGIN DESCRIPTION:
Mapping XS 022302af
END DESCRIPTION:
XS GIS Cut Line= 4
      1431882.92      6903457.24      1432250.09      6903116.12
        1432350.      6903019.56      1432606.65      6902519.05
#Sta/Elev= 30
  4491.7  1934.7  4570.5 1933.86  4676.5 1931.99  4683.9 1931.36  4726.4 1931.86
  4747.4 1929.77  4766.4 1929.32  4766.6 1928.82  4770.4 1929.32  4775.7 1931.13
  4782.5 1931.88  4796.7 1932.13  4966.8 1932.43  4995.1 1932.09    5002 1930.77
  5009.2 1930.69  5016.2 1932.08  5030.3 1932.64  5108.2 1931.15  5174.3 1931.26
  5189.8 1930.38  5202.1 1931.46  5279.6 1931.56  5313.4 1930.81  5380.8 1931.65
  5396.2 1931.16  5425.8 1931.84  5470.7 1931.52  5590.4 1933.07  5694.3 1933.16
#Mann= 3 ,-1 , 0
  4491.7     .07       0  4766.4     .07       0  4770.4     .07       0
Bank Sta=4766.4,4770.4
XS Rating Curve= 0 ,0
Exp/Cntr=0.3,0.1

Type RM Length L Ch R = 1 ,63342   ,437,437,437
BEGIN DESCRIPTION:
Mapping XS f047f833
END DESCRIPTION:
XS GIS Cut Line= 3
      1432580.82      6903777.59      1432700.61      6903267.16
       1432812.6      6902605.68
#Sta/Elev= 30
  4452.9 1932.09  4483.3 1932.13  4533.2  1931.3  4538.3 1930.73  4616.8 1930.78
  4803.2 1928.84  4935.6 1929.78  4955.8 1926.45  4966.1 1927.07  4972.9 1929.48
  4975.9 1927.51  4979.3 1927.51  4986.5 1929.24  5087.9 1928.22  5098.2 1928.72
  5138.6  1927.5  5156.9 1926.12  5157.2 1925.62  5160.7 1925.62  5160.9 1926.12
  5179.2 1927.59  5229.9 1927.17  5240.1 1927.88  5250.2 1927.35    5390 1928.92
  5432.8 1928.44  5493.6 1929.66  5534.2  1929.5  5571.2 1930.53  5648.1 1930.96
#Mann= 3 ,-1 , 0
  4452.9     .07       0  5156.9     .07       0  5160.9     .07       0
Bank Sta=5156.9,5160.9
XS Rating Curve= 0 ,0
Exp/Cntr=0.3,0.1

Type RM Length L Ch R = 1 ,62905   ,589,589,589
BEGIN DESCRIPTION:
Mapping XS 8f9614e9
END DESCRIPTION:
XS GIS Cut Line= 5
      1433148.87      6903659.35      1433260.86      6903421.05
      1433203.61      6903279.11       1433096.8      6903125.47
       1433067.8      6902577.01
#Sta/Elev= 30
    4461 1928.76  4465.8 1928.34  4511.4 1928.06  4625.5 1928.12  4676.6 1927.57
  4738.4 1928.26  4783.5 1928.03  4875.3 1926.66  4970.7  1926.7  4985.5 1926.15
  5012.7 1926.68  5021.3 1925.68  5027.4 1925.67  5036.1  1926.5  5061.7 1925.98
  5142.1  1925.8  5162.1 1926.17  5182.1 1925.66  5195.2 1926.08  5252.2 1925.61
  5272.2 1926.03  5360.4 1925.06  5360.6 1924.56  5364.1 1924.56  5364.4 1925.06
  5442.5 1925.95  5482.5    1927  5532.6 1927.56  5542.6 1928.24  5613.7 1928.74
#Mann= 3 ,-1 , 0
    4461     .07       0  5360.4     .07       0  5364.4     .07       0
Bank Sta=5360.4,5364.4
XS Rating Curve= 0 ,0
Exp/Cntr=0.3,0.1

Type RM Length L Ch R = 1 ,62316   ,833,833,833
BEGIN DESCRIPTION:
Mapping XS b8f486f6
END DESCRIPTION:
XS GIS Cut Line= 4
        1433227.      6903642.59      1433612.43      6903297.09
      1433598.35      6902920.57      1433333.45      6902428.66
#Sta/Elev= 30
  4105.6 1927.88  4277.5 1927.25  4284.5 1927.67  4327.1 1926.68  4341.3 1927.21
  4475.9 1926.51  4553.6 1925.16  4642.3 1924.91  4662.3  1924.2  4687.7 1924.67
  4762.4 1924.24  4862.5 1922.84  4882.5 1923.73  4982.6 1924.06  4992.6 1923.04
  4996.8 1919.12    4997 1918.62  5000.5 1918.62  5000.8 1919.12  5004.3 1919.12
  5013.1 1922.76  5018.8 1923.34  5122.6 1924.16  5160.7 1923.86  5248.4 1925.53
  5330.3 1925.55  5343.6 1926.19  5434.1 1926.56  5461.7 1927.33  5558.7 1927.55
#Mann= 3 ,-1 , 0
  4105.6     .07       0  4996.8      .1       0  5000.8     .07       0
Bank Sta=4996.8,5000.8
XS Rating Curve= 0 ,0
Exp/Cntr=0.3,0.1

Type RM Length L Ch R = 1 ,61483   ,36,36,36
BEGIN DESCRIPTION:
Mapping XS f06f29d6
END DESCRIPTION:
XS GIS Cut Line= 6
      1433990.89      6903227.64      1434307.38      6903182.96
      1434324.74      6903075.32      1434189.33      6902974.62
      1434140.72      6902828.79      1433613.03      6902092.81
#Sta/Elev= 30
  4496.5 1923.71  4834.5  1919.3  4861.7 1920.79  4891.2 1919.46  4896.2 1920.88
  4937.8  1915.1  4981.9 1911.64  4982.2 1911.14  4986.1 1911.64  4993.8  1912.7
  5008.6 1911.77  5014.7 1913.43  5038.3 1914.66  5065.4 1922.44  5074.2 1923.64
  5080.2 1923.64  5093.7 1919.39  5110.4 1918.99  5116.1 1916.12    5138  1915.4
  5305.4 1916.81  5320.2 1920.36  5326.3  1919.5  5334.9 1921.73    5341 1920.54
  5349.6 1922.26  5391.4 1919.45  5399.5 1920.89  5471.2 1921.89  6156.5 1925.83
#Mann= 3 ,-1 , 0
  4496.5     .07       0  4981.9     .07       0  4986.1     .07       0
Bank Sta=4981.9,4986.1
XS Rating Curve= 0 ,0
Exp/Cntr=0.3,0.1

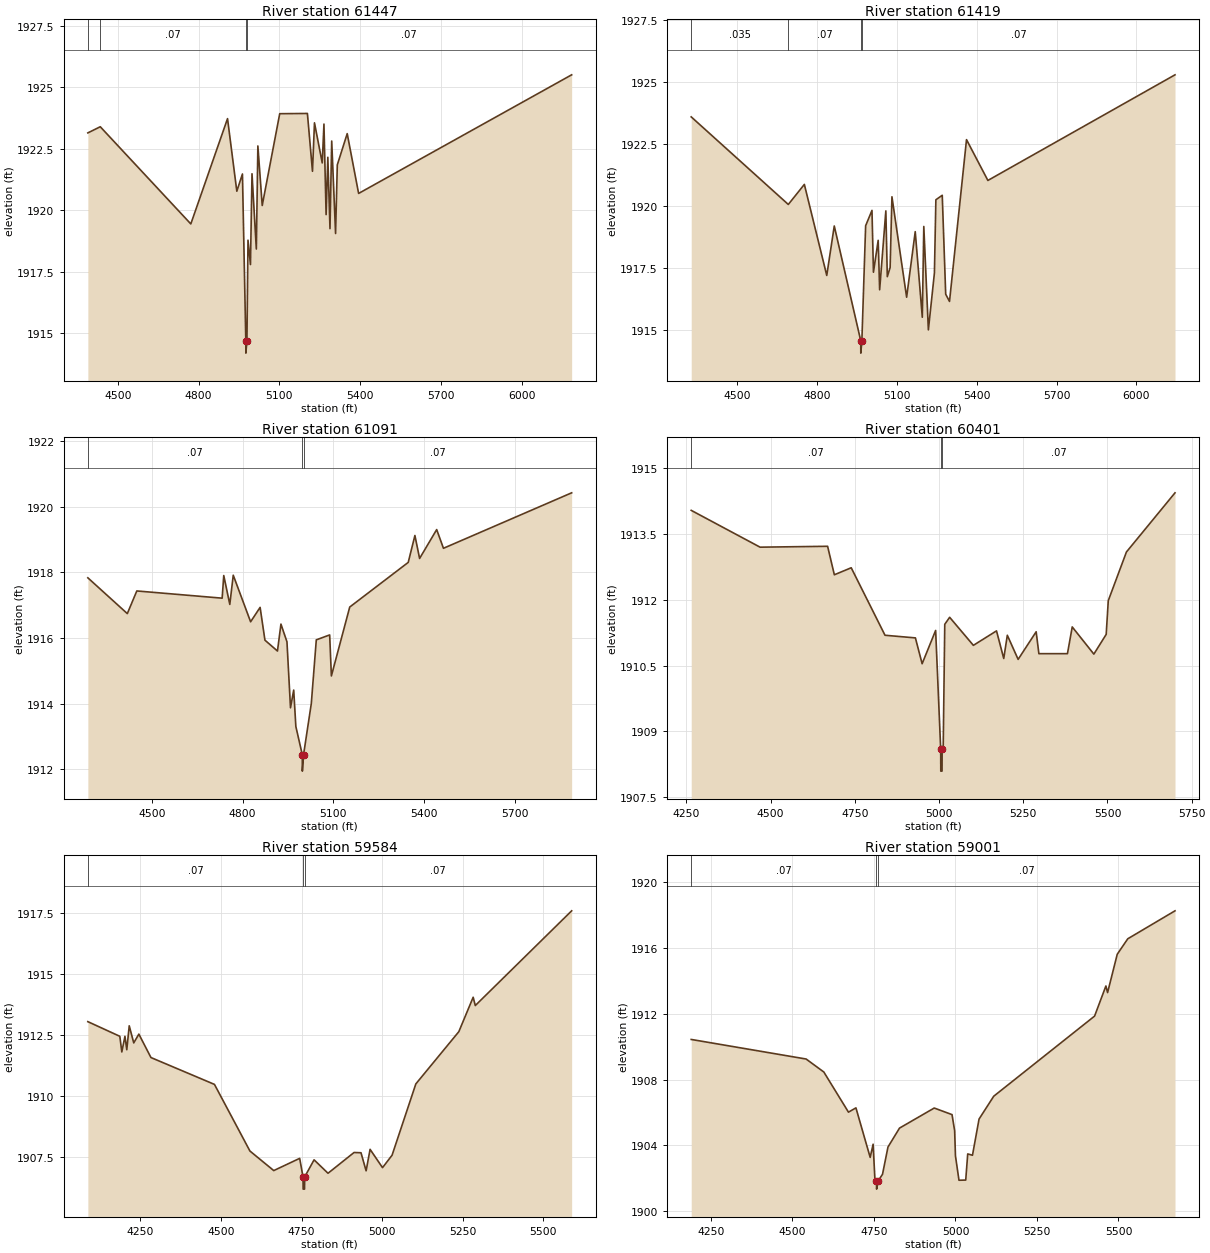
Type RM Length L Ch R = 1 ,61447   ,28,28,28
BEGIN DESCRIPTION:
Mapping XS 53c1c8f4
END DESCRIPTION:
XS GIS Cut Line= 6
       1433997.8      6903245.01      1434346.47       6903207.2
      1434366.41      6903054.49      1434196.27      6902936.43
       1434192.8      6902825.32      1433647.69      6902044.11
#Sta/Elev= 30
  4388.7 1923.14  4434.8 1923.39  4771.2 1919.44  4907.6 1923.72  4942.1 1920.77
    4963 1921.47  4975.5 1914.69  4975.7 1914.19  4979.7 1914.69  4983.6 1918.78
  4992.8 1917.79  4998.5 1921.48  5014.6 1918.42  5020.3 1922.61  5036.5 1920.19
  5101.5 1923.92  5204.3 1923.93  5223.2 1921.58  5230.6 1923.55  5259.4 1921.92
  5265.8  1923.5  5273.8 1919.82  5280.2 1922.15  5288.2 1919.25  5294.6 1922.81
    5309 1919.05  5315.4 1921.84  5352.2 1923.11  5394.6 1920.68    6186  1925.5
#Mann= 4 ,-1 , 0
  4388.7    .035       0  4434.8     .07       0  4975.5     .07       0
  4979.7     .07       0
Bank Sta=4975.5,4979.7
XS Rating Curve= 0 ,0
Exp/Cntr=0.3,0.1

Type RM Length L Ch R = 1 ,61419   ,328,328,328
BEGIN DESCRIPTION:
Mapping XS c21e49b8
END DESCRIPTION:
XS GIS Cut Line= 6
      1434018.66      6903267.58      1434377.55      6903227.47
      1434390.72      6903054.49      1434227.52      6902943.37
      1434182.38      6902773.24      1433696.25      6902044.03
#Sta/Elev= 30
  4327.3  1923.6  4692.1 1920.06  4752.4 1920.87  4836.6 1917.19  4864.8 1919.19
  4964.3 1914.55  4964.5 1914.05  4968.5 1914.55  4982.7  1919.2  5006.5 1919.82
    5012 1917.32  5029.8 1918.61  5035.3 1916.61  5058.6  1919.8  5064.1 1917.14
  5074.7 1917.51  5081.5 1920.37  5136.7 1916.31    5169 1918.96  5195.6  1915.5
  5201.2 1919.17  5218.4 1914.99  5241.1 1917.29  5246.6 1920.25  5270.5 1920.43
  5283.5 1916.43  5297.8 1916.14  5361.7 1922.68    5442 1921.03  6145.1  1925.3
#Mann= 4 ,-1 , 0
  4327.3    .035       0  4692.1     .07       0  4964.3     .07       0
  4968.5     .07       0
Bank Sta=4964.3,4968.5
XS Rating Curve= 0 ,0
Exp/Cntr=0.3,0.1

Type RM Length L Ch R = 1 ,61091   ,690,690,690
BEGIN DESCRIPTION:
Mapping XS 2bffc19c
END DESCRIPTION:
XS GIS Cut Line= 3
      1434793.49      6903502.39      1434571.27      6902849.62
      1434151.76      6902041.81
#Sta/Elev= 30
  4288.2 1917.83  4418.7 1916.74  4450.1 1917.43  4732.3 1917.21  4737.6  1917.9
  4757.6 1917.02    4769 1917.91  4826.4 1916.49  4857.8 1916.93  4873.8 1915.93
  4915.2  1915.6  4926.7 1916.42  4946.6 1915.88  4958.3 1913.87  4968.9 1914.41
    4976  1913.3  4997.3 1912.44  4997.5 1911.94  5001.5 1912.44  5027.1    1914
  5043.6 1915.94  5087.8 1916.09  5093.5 1914.84  5154.2 1916.94  5347.6  1918.3
  5369.7 1919.12  5385.2 1918.42  5441.7  1919.3  5464.1 1918.73    5888 1920.42
#Mann= 3 ,-1 , 0
  4288.2     .07       0  4997.3     .07       0  5001.5     .07       0
Bank Sta=4997.3,5001.5
XS Rating Curve= 0 ,0
Exp/Cntr=0.3,0.1

Type RM Length L Ch R = 1 ,60401   ,817,817,817
BEGIN DESCRIPTION:
Mapping XS a99b78c0
END DESCRIPTION:
XS GIS Cut Line= 3
      1435175.44      6903321.87      1435123.36      6902578.79
      1434876.82      6901932.95
#Sta/Elev= 30
  4264.4 1914.04  4468.8  1913.2  4669.3 1913.22  4689.3 1912.57  4739.4 1912.73
  4839.7 1911.19  4929.9 1911.13  4949.9 1910.54    4990  1911.3    5005 1908.59
  5005.3 1908.09    5009 1908.09  5009.3 1908.59  5012.4 1908.59  5017.1 1911.44
  5031.6  1911.6    5102 1910.96  5170.7 1911.29  5192.2 1910.66  5202.8 1911.19
  5234.9 1910.64  5288.4 1911.27  5296.5 1910.77  5381.3 1910.77  5395.5 1911.38
  5459.7 1910.76  5496.3 1911.21  5502.5 1911.98  5556.4 1913.09  5700.6 1914.44
#Mann= 3 ,-1 , 0
  4264.4     .07       0    5005     .07       0  5009.3     .07       0
Bank Sta=5005,5009.3
XS Rating Curve= 0 ,0
Exp/Cntr=0.3,0.1

Type RM Length L Ch R = 1 ,59584   ,583,583,583
BEGIN DESCRIPTION:
Mapping XS 72b3167e
END DESCRIPTION:
XS GIS Cut Line= 3
      1435321.25      6903349.66      1435772.66      6902554.49
      1436039.29      6902031.61
#Sta/Elev= 30
    4087 1913.06  4186.2 1912.46  4192.4 1911.82  4202.1 1912.46  4207.8 1911.91
  4215.4 1912.89  4229.4 1912.19  4245.3 1912.55  4282.8 1911.59  4479.9 1910.49
    4590 1907.76  4663.9 1906.96  4744.3 1907.46  4754.7  1906.7  4755.1  1906.2
  4759.4  1906.2  4759.8  1906.7    4789  1907.4  4832.3 1906.85    4913  1907.7
  4934.6 1907.69  4950.5 1906.95  4962.8 1907.83  5001.4 1907.08  5031.1 1907.59
  5104.8 1910.51  5238.2 1912.65  5282.7 1914.06  5289.3 1913.72  5588.3  1917.6
#Mann= 3 ,-1 , 0
    4087     .07       0  4754.7     .07       0  4759.8     .07       0
Bank Sta=4754.7,4759.8
XS Rating Curve= 0 ,0
Exp/Cntr=0.3,0.1

Type RM Length L Ch R = 1 ,59001   ,843,843,843
BEGIN DESCRIPTION:
Raven Creek 41.0
END DESCRIPTION:
XS GIS Cut Line= 3
      1435904.62      6903630.83        1436230.       6902888.4
      1436404.99      6902238.03
#Sta/Elev= 30
  4189.4 1910.44  4541.9 1909.25  4596.2 1908.46  4671.8 1906.02  4694.7 1906.28
  4738.4 1903.27  4747.4 1904.07  4752.8 1901.98  4757.7 1901.84  4758.1 1901.34
  4762.8 1901.84  4776.2 1902.24    4793  1903.9  4828.4 1905.05  4934.9 1906.27
  4989.5 1905.87  4997.5 1904.89    5000 1903.36  5010.8 1901.88  5031.5 1901.89
  5037.6 1903.48  5052.2  1903.4  5072.4  1905.6  5117.5 1906.99  5426.8 1911.86
  5461.5 1913.69  5466.7 1913.29  5496.3 1915.62  5528.6 1916.56  5673.5 1918.26
#Mann= 3 ,-1 , 0
  4189.4     .07       0  4757.7     .07       0  4762.8     .07       0
Bank Sta=4757.7,4762.8
XS Rating Curve= 0 ,0
Exp/Cntr=0.3,0.1

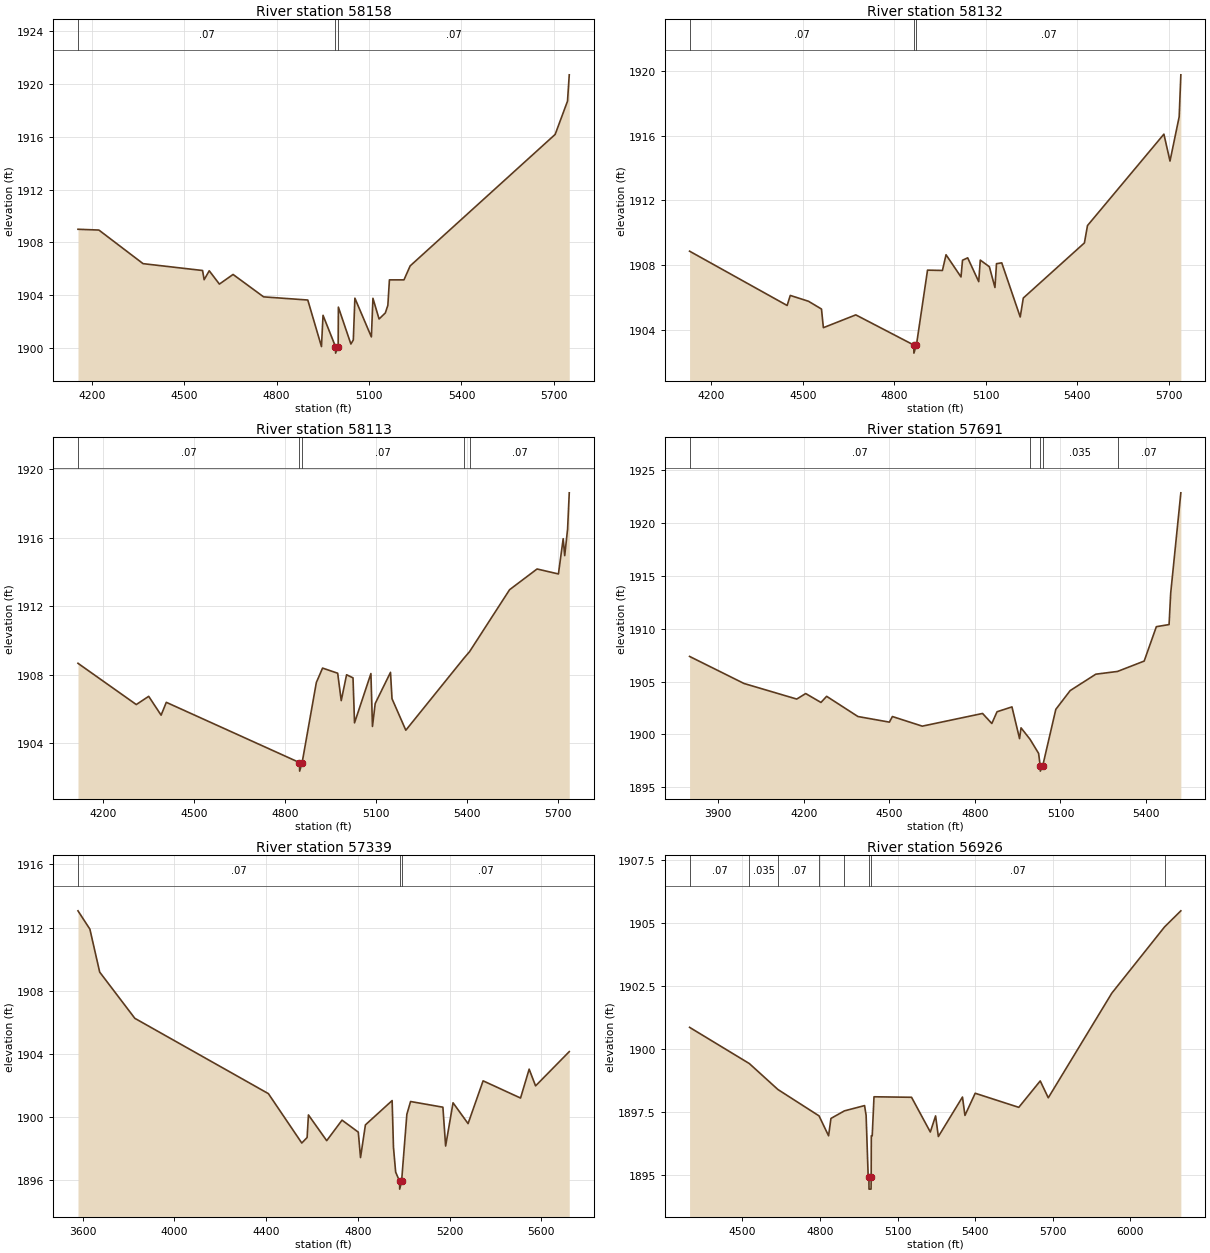
Type RM Length L Ch R = 1 ,58158   ,26,26,26
BEGIN DESCRIPTION:
Mapping XS 4ddcaaab
END DESCRIPTION:
XS GIS Cut Line= 4
       1436734.8      6903614.64      1436909.29      6902796.91
      1436943.14      6902609.41      1436974.36      6902042.34
#Sta/Elev= 30
  4155.3 1908.99  4223.2 1908.93  4366.6 1906.38  4559.7 1905.86  4564.8 1905.16
  4581.3 1905.84  4614.3 1904.83  4658.7 1905.56  4757.8 1903.86  4901.2 1903.62
  4945.6 1900.09  4950.7 1902.46    4991 1900.09  4991.5 1899.59  4999.8 1900.09
  5000.5 1903.08  5041.1 1900.28    5049 1900.59  5054.1 1903.76  5107.6 1900.82
  5112.7 1903.75  5132.6 1902.18  5152.9 1902.64  5161.1 1903.22  5166.2 1905.15
  5213.4 1905.15  5233.5 1906.21  5704.2 1916.19  5744.2 1918.71  5749.9 1920.71
#Mann= 3 ,-1 , 0
  4155.3     .07       0    4991     .07       0  4999.8     .07       0
Bank Sta=4991,4999.8
XS Rating Curve= 0 ,0
Exp/Cntr=0.3,0.1

Type RM Length L Ch R = 1 ,58132   ,19,19,19
BEGIN DESCRIPTION:
Mapping XS ca1ac798
END DESCRIPTION:
XS GIS Cut Line= 5
      1436755.63       6903640.7       1436919.7      6902893.26
      1436935.33       6902791.7      1436969.18       6902606.8
      1437010.82      6902052.52
#Sta/Elev= 30
  4128.1 1908.87  4448.2 1905.52  4458.5 1906.14  4518.2 1905.78  4560.9  1905.3
  4567.1 1904.15  4673.5 1904.94  4863.6 1903.08  4864.1 1902.58  4872.4 1903.08
  4908.8  1907.7  4957.7 1907.68  4969.5 1908.65  5018.6 1907.28  5023.6 1908.31
  5040.5 1908.46  5076.8 1906.99  5081.9 1908.32  5111.7 1907.91    5130 1906.63
  5135.1  1908.1  5152.3 1908.15  5212.9 1904.81    5223 1905.98  5423.5 1909.38
  5433.6 1910.45  5684.3 1916.09  5704.3 1914.43  5734.4 1917.16  5739.9 1919.75
#Mann= 3 ,-1 , 0
  4128.1     .07       0  4863.6     .07       0  4872.4     .07       0
Bank Sta=4863.6,4872.4
XS Rating Curve= 0 ,0
Exp/Cntr=0.3,0.1

Type RM Length L Ch R = 1 ,58113   ,422,422,422
BEGIN DESCRIPTION:
Mapping XS 3d120074
END DESCRIPTION:
XS GIS Cut Line= 5
      1436768.66      6903645.86      1436924.91       6902916.7
      1436956.16      6902778.68        1436977.      6902661.49
      1437042.06      6902052.51
#Sta/Elev= 30
  4117.6 1908.66  4309.7 1906.25  4350.6 1906.73  4391.5 1905.63  4408.6 1906.38
  4847.4 1902.86  4847.9 1902.36  4856.2 1902.86    4903 1907.54  4923.5 1908.38
  4973.3 1908.08    4985 1906.48  5002.6 1907.99  5023.8 1907.81  5028.8 1905.18
  5082.8 1908.06  5087.9 1904.97  5096.9 1906.31  5147.3 1908.13  5152.3 1906.59
  5197.8 1904.75  5389.4 1908.96  5407.8 1909.34  5539.7 1912.96  5630.2 1914.17
  5700.6 1913.88  5716.3 1915.94  5721.3 1914.95  5730.8  1916.5  5736.3 1918.62
#Mann= 5 ,-1 , 0
  4117.6     .07       0  4847.4     .07       0  4856.2     .07       0
  5389.4    .035       0  5407.8     .07       0
Bank Sta=4847.4,4856.2
XS Rating Curve= 0 ,0
Exp/Cntr=0.3,0.1

Type RM Length L Ch R = 1 ,57691   ,352,352,352
BEGIN DESCRIPTION:
Raven Creek 38.0
END DESCRIPTION:
XS GIS Cut Line= 3
      1436943.13      6903786.52      1437302.89      6902641.19
      1437364.98       6902122.7
#Sta/Elev= 30
  3799.5 1907.37  3990.6 1904.81  4175.3 1903.34  4206.7 1903.86  4260.3 1903.02
  4280.1  1903.6  4389.9 1901.69  4500.2 1901.16  4510.7 1901.69  4615.5 1900.78
  4826.9 1901.98  4859.4 1901.03  4877.6 1902.14    4930  1902.6  4956.6  1899.6
  4961.8 1900.62  4993.1 1899.55  5023.4 1898.21    5029 1897.03  5029.5 1896.53
  5037.8 1897.03  5083.8 1902.37  5134.1 1904.14  5223.9 1905.69  5300.1 1905.95
  5393.6 1906.93  5436.3 1910.18  5480.9 1910.38  5486.6 1913.35  5522.2 1922.83
#Mann= 5 ,-1 , 0
  3799.5     .07       0  4993.1    .035       0    5029    .035       0
  5037.8    .035       0  5300.1     .07       0
Bank Sta=5029,5037.8
XS Rating Curve= 0 ,0
Exp/Cntr=0.3,0.1

Type RM Length L Ch R = 1 ,57339   ,413,413,413
BEGIN DESCRIPTION:
Raven Creek 37.0
END DESCRIPTION:
XS GIS Cut Line= 3
      1436870.24      6904002.61        1437605.        6902788.
      1437950.48      6902154.55
#Sta/Elev= 30
  3580.2 1913.06  3632.1  1911.9  3674.8 1909.18    3828 1906.25    4410 1901.48
  4555.6 1898.35  4578.8  1898.7  4584.6 1900.13  4664.2  1898.5    4731  1899.8
  4801.9 1899.04  4811.6 1897.43  4832.9  1899.5  4949.3 1901.04  4955.2 1898.08
  4964.7 1896.51  4981.8 1895.93  4982.3 1895.43  4990.6 1895.93  5013.5 1900.17
  5029.7 1900.98  5170.6 1900.62  5182.5 1898.16  5214.8  1900.9  5280.3 1899.58
  5345.8 1902.29    5509  1901.2  5546.5 1903.03  5574.5 1901.97  5721.3 1904.14
#Mann= 3 ,-1 , 0
  3580.2     .07       0  4981.8     .07       0  4990.6     .07       0
Bank Sta=4981.8,4990.6
XS Rating Curve= 0 ,0
Exp/Cntr=0.3,0.1

Type RM Length L Ch R = 1 ,56926   ,417,417,417
BEGIN DESCRIPTION:
Mapping XS 0fc3bdaa
END DESCRIPTION:
XS GIS Cut Line= 3
      1437450.93       6903708.4      1437833.77      6903114.62
      1438150.13       6901963.5
#Sta/Elev= 30
  4295.7 1900.86  4526.9 1899.42  4637.3 1898.39  4796.6 1897.34  4833.4 1896.55
  4842.6 1897.24  4894.6 1897.54  4972.6 1897.75  4978.6 1897.36  4986.3 1895.02
  4989.3 1894.93  4989.8 1894.43  4997.7 1894.43  4998.2 1894.93  4998.7 1896.55
  5002.2 1896.55  5009.1  1898.1  5154.3 1898.08  5226.9  1896.7  5247.3 1897.34
    5258 1896.52  5351.3 1898.09  5360.9 1897.36  5400.5 1898.24  5569.1 1897.68
  5652.1 1898.73  5683.2 1898.06  5929.1 1902.22  6132.9 1904.85    6196 1905.49
#Mann= 8 ,-1 , 0
  4295.7     .07       0  4526.9    .035       0  4637.3     .07       0
  4796.6    .035       0  4894.6     .07       0  4989.3     .07       0
  4998.2     .07       0  6132.9     .16       0
Bank Sta=4989.3,4998.2
XS Rating Curve= 0 ,0
Exp/Cntr=0.3,0.1

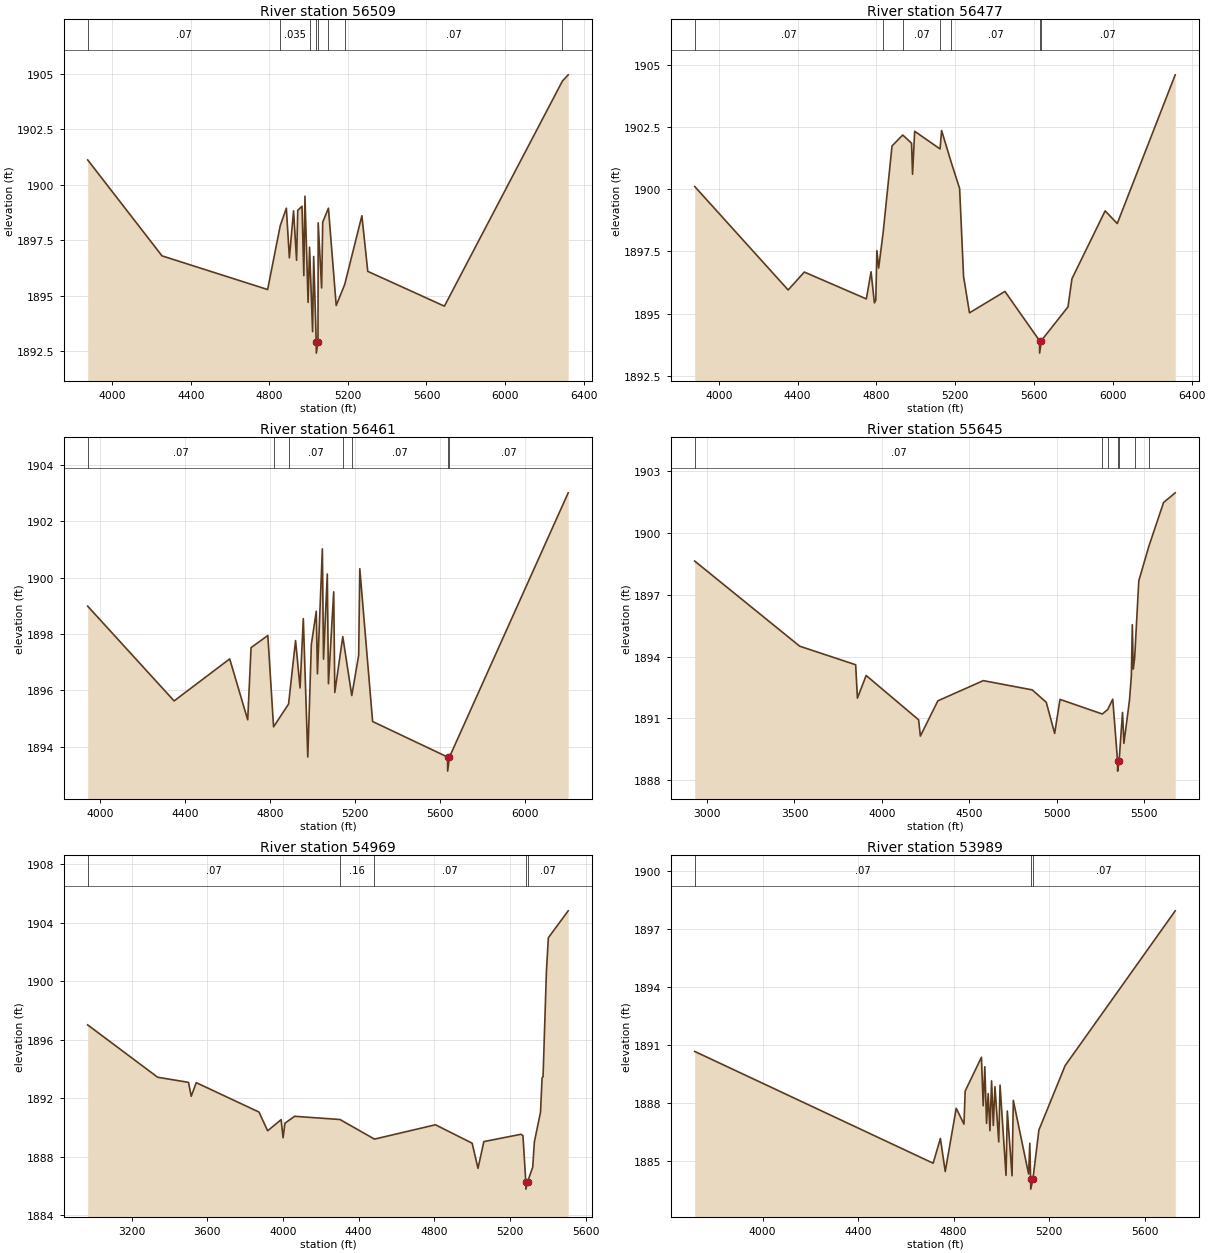
Type RM Length L Ch R = 1 ,56509   ,32,32,32
BEGIN DESCRIPTION:
Mapping XS 38dd958f
END DESCRIPTION:
XS GIS Cut Line= 6
      1437725.89      6904308.99      1437982.93      6903636.62
      1438187.93       6903294.3       1438232.2      6903197.95
      1438216.58      6903075.55      1438176.42      6901978.26
#Sta/Elev= 30
  3875.2 1901.12  4253.5 1896.79  4791.3 1895.27  4855.4 1898.15  4886.6 1898.94
    4902  1896.7  4923.3 1898.82  4938.7 1896.59  4944.6 1898.84  4966.3 1899.03
  4975.5  1895.9  4981.3 1899.48  4997.2 1894.69  5004.7 1897.18  5020.2 1893.37
  5025.7 1896.76  5038.7  1892.9  5039.2  1892.4  5047.6  1892.9  5048.7 1898.28
  5066.2 1895.34  5071.7 1898.31  5100.8 1898.94  5140.4 1894.55  5183.8  1895.5
  5271.1  1898.6  5301.1 1896.09  5691.3 1894.52  6292.1 1904.68  6321.5 1904.96
#Mann= 8 ,-1 , 0
  3875.2     .07       0  4855.4    .035       0  5004.7     .07       0
  5038.7    .035       0  5047.6     .07       0  5100.8    .035       0
  5183.8     .07       0  6292.1     .16       0
Bank Sta=5038.7,5047.6
XS Rating Curve= 0 ,0
Exp/Cntr=0.3,0.1

Type RM Length L Ch R = 1 ,56477   ,16,16,16
BEGIN DESCRIPTION:
Mapping XS 5593174c
END DESCRIPTION:
XS GIS Cut Line= 6
      1437884.75      6904361.04      1438051.42      6903613.64
      1438130.64       6903419.3      1438213.98      6903315.14
      1438260.85      6903187.53      1438233.71      6901993.84
#Sta/Elev= 30
  3877.5 1900.11  4351.9 1895.95  4433.9 1896.67  4748.7 1895.59  4772.7 1896.68
  4789.7 1895.43  4796.8 1895.54  4802.2 1897.53  4811.3 1896.83  4834.2 1898.27
  4879.1 1901.74  4933.5 1902.18  4978.3 1901.85  4983.3  1900.6  4994.1 1902.33
  5122.9 1901.62  5130.8 1902.36  5180.5 1901.06  5222.2 1900.03  5242.3 1896.49
  5272.3 1895.03  5452.3 1895.89  5627.9 1893.91  5628.4 1893.41  5636.8 1893.91
  5772.4 1895.27  5792.4  1896.4    5961 1899.13  6022.4 1898.62  6316.6  1904.6
#Mann= 7 ,-1 , 0
  3877.5     .07       0  4834.2    .035       0  4933.5     .07       0
  5122.9    .035       0  5180.5     .07       0  5627.9     .07       0
  5636.8     .07       0
Bank Sta=5627.9,5636.8
XS Rating Curve= 0 ,0
Exp/Cntr=0.3,0.1

Type RM Length L Ch R = 1 ,56461   ,816,816,816
BEGIN DESCRIPTION:
Mapping XS c386cc4b
END DESCRIPTION:
XS GIS Cut Line= 6
      1438017.56      6904332.39      1438108.02      6903511.64
      1438224.39      6903328.16      1438284.29      6903151.07
      1438266.06      6903091.18      1438348.29      6902126.67
#Sta/Elev= 30
  3941.4 1898.99  4348.2 1895.63  4609.8 1897.12  4694.6 1894.96  4710.4 1897.52
  4789.3 1897.95  4816.3 1894.71  4886.9 1895.52  4919.8 1897.77    4941 1896.09
  4956.3 1898.55  4977.4 1893.64  4994.1 1897.63  5017.3 1898.81  5022.8 1896.59
    5046 1901.02  5051.4 1897.11  5069.2 1900.13  5074.6 1896.24  5099.4  1899.5
  5104.5 1895.93  5142.1 1897.91  5184.4 1895.82  5216.9 1897.25  5222.1 1900.32
  5282.5  1894.9  5635.2 1893.64  5635.7 1893.14  5644.2 1893.64  6203.1 1903.01
#Mann= 7 ,-1 , 0
  3941.4     .07       0  4816.3    .035       0  4886.9     .07       0
  5142.1    .035       0  5184.4     .07       0  5635.2     .07       0
  5644.2     .07       0
Bank Sta=5635.2,5644.2
XS Rating Curve= 0 ,0
Exp/Cntr=0.3,0.1

Type RM Length L Ch R = 1 ,55645   ,676,676,676
BEGIN DESCRIPTION:
Mapping XS 7cb0e87f
END DESCRIPTION:
XS GIS Cut Line= 3
      1438827.29      6905108.54      1438823.35      6903057.32
      1438586.73      6902402.06
#Sta/Elev= 30
  2929.3 1898.63  3529.8  1894.5  3849.8  1893.6  3859.8 1891.98  3909.8 1893.08
  4209.8 1890.93  4219.8 1890.14  4319.8 1891.85  4579.8 1892.83  4859.8 1892.38
  4939.8 1891.78  4987.8 1890.27  5018.4 1891.92  5260.5 1891.21  5291.2 1891.43
    5320 1891.93  5347.4 1888.94  5347.9 1888.44  5356.4 1888.94  5375.8 1891.29
  5383.8 1889.79  5415.7 1891.88  5426.4 1893.06  5431.8 1895.54  5437.2 1893.39
  5445.2 1893.92  5468.9 1897.67  5526.2 1899.34  5610.5 1901.47  5677.2 1901.94
#Mann= 7 ,-1 , 0
  2929.3     .07       0  5260.5    .035       0  5291.2     .07       0
  5347.4     .07       0  5356.4     .07       0  5445.2    .035       0
  5526.2     .07       0
Bank Sta=5347.4,5356.4
XS Rating Curve= 0 ,0
Exp/Cntr=0.3,0.1

Type RM Length L Ch R = 1 ,54969   ,980,980,980
BEGIN DESCRIPTION:
Mapping XS e15c6cfc
END DESCRIPTION:
XS GIS Cut Line= 3
      1438883.71      6904830.71      1439276.48      6902851.59
      1439146.27      6902346.42
#Sta/Elev= 30
    2968 1897.02  3337.8 1893.44  3500.9 1893.09  3515.1 1892.14  3541.7 1893.07
  3873.3 1891.06  3918.9 1889.78  3990.3 1890.54  4000.5  1889.3  4010.7  1890.3
  4061.6 1890.77  4301.2 1890.55  4483.6 1889.21  4805.9 1890.19  4999.8 1888.93
  5030.7 1887.21  5061.7 1889.04  5257.9 1889.54  5268.2 1889.45  5283.3 1886.29
  5283.8 1885.79  5292.6 1886.29  5319.9 1887.29  5328.6 1889.02  5361.2 1891.06
  5369.3  1893.4  5374.5 1893.47  5392.2 1900.66  5402.5 1902.98  5507.4 1904.82
#Mann= 5 ,-1 , 0
    2968     .07       0  4301.2     .16       0  4483.6     .07       0
  5283.3     .07       0  5292.6     .07       0
Bank Sta=5283.3,5292.6
XS Rating Curve= 0 ,0
Exp/Cntr=0.3,0.1

Type RM Length L Ch R = 1 ,53989   ,29,29,29
BEGIN DESCRIPTION:
Mapping XS 96cd89ab
END DESCRIPTION:
XS GIS Cut Line= 6
      1439113.89      6903769.05      1439690.54      6902971.39
      1439898.87      6902960.97      1439945.75      6902911.49
       1439982.2      6902510.45      1439849.75      6902193.59
#Sta/Elev= 30
  3715.3 1890.66  4714.2 1884.88  4744.6 1886.16  4764.9 1884.45    4811 1887.72
  4843.4  1886.9  4848.5 1888.61  4916.6 1890.36  4923.9 1887.85  4930.7 1889.87
    4938 1886.94  4944.9 1888.48  4952.2 1886.56  4959.1 1889.14  4966.3 1886.83
  4973.2 1888.84  4989.1 1885.98  4994.5 1888.92  5019.6 1884.25    5025 1887.58
  5044.8 1884.23  5050.1 1888.13  5114.2 1884.32  5119.2 1885.91  5122.7 1884.04
  5123.2 1883.54  5132.1 1884.04  5157.4  1886.6  5267.4 1889.93  5728.4 1897.93
#Mann= 3 ,-1 , 0
  3715.3     .07       0  5122.7     .07       0  5132.1     .07       0
Bank Sta=5122.7,5132.1
XS Rating Curve= 0 ,0
Exp/Cntr=0.3,0.1

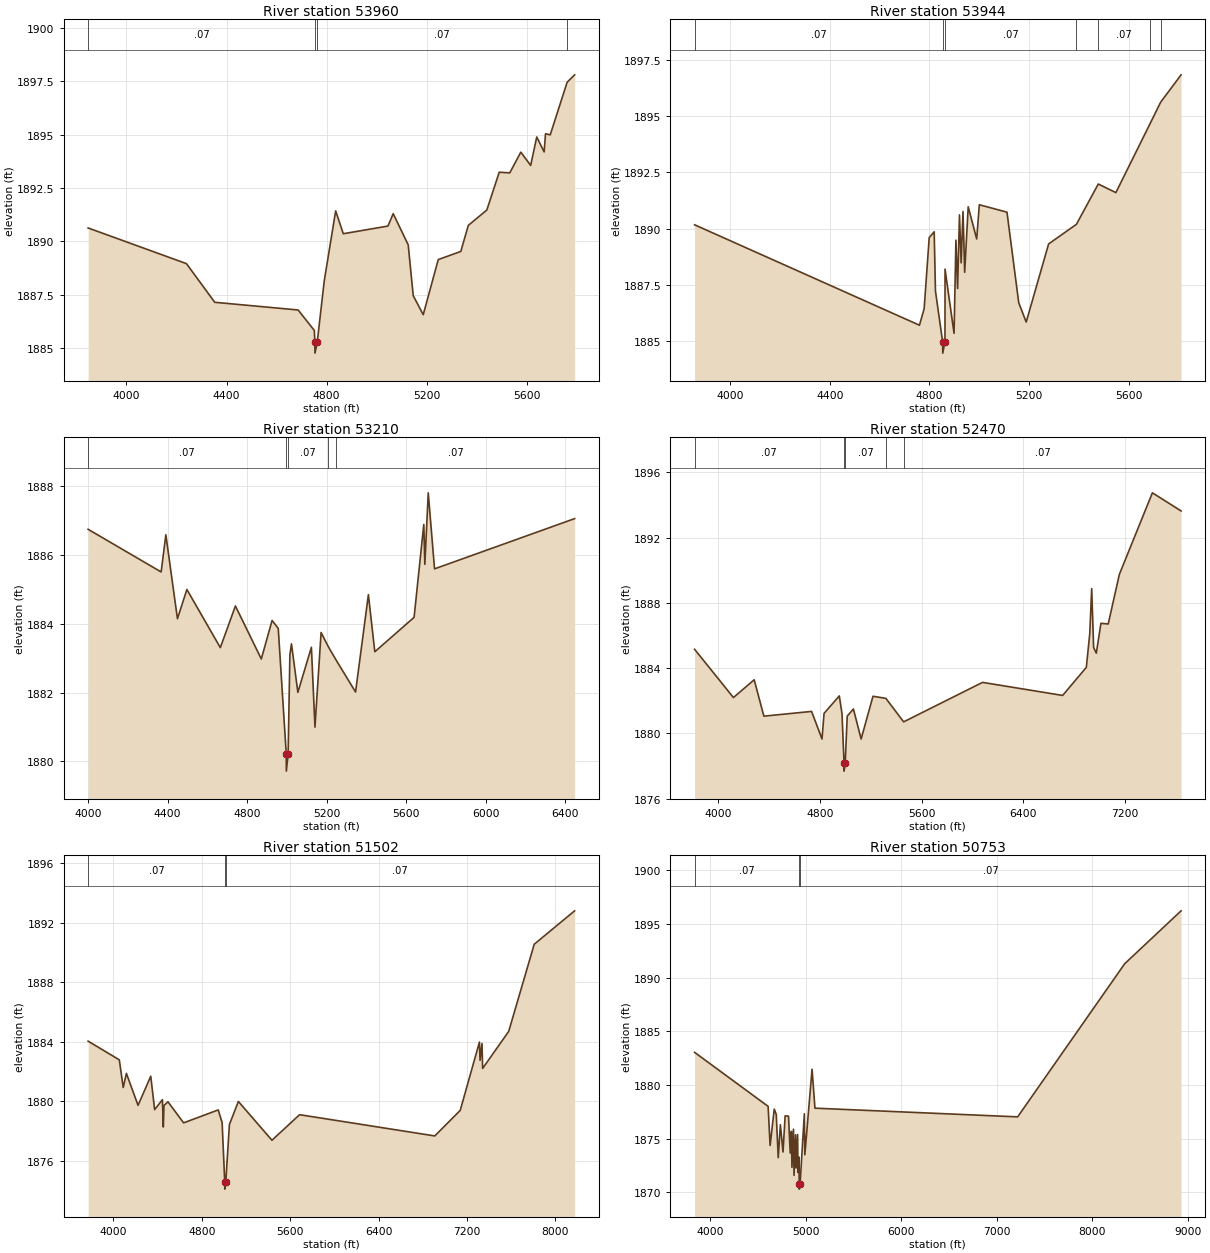
Type RM Length L Ch R = 1 ,53960   ,16,16,16
BEGIN DESCRIPTION:
Mapping XS dc62c7f0
END DESCRIPTION:
XS GIS Cut Line= 6
       1439192.6      6903688.26      1439802.52      6902966.18
      1439885.85      6902984.41      1440000.43      6902862.01
      1440005.64      6902473.99      1439875.43      6902148.47
#Sta/Elev= 30
  3847.3 1890.63    4240 1888.96  4353.1 1887.15    4686 1886.79  4750.8 1885.83
  4752.8 1885.27  4753.3 1884.77  4762.2 1885.27  4790.6 1888.17    4836 1891.43
  4866.4 1890.36  5044.9 1890.72  5065.7  1891.3  5125.7 1889.84  5145.7 1887.46
  5185.7 1886.57  5245.7 1889.15  5335.7 1889.53  5365.7 1890.75  5439.7 1891.47
  5489.2 1893.24  5531.3 1893.21  5575.4 1894.18  5614.8 1893.56    5639 1894.89
  5668.6 1894.19    5674 1895.04  5692.9 1894.99  5760.3 1897.45  5790.3  1897.8
#Mann= 4 ,-1 , 0
  3847.3     .07       0  4752.8     .07       0  4762.2     .07       0
  5760.3    .035       0
Bank Sta=4752.8,4762.2
XS Rating Curve= 0 ,0
Exp/Cntr=0.3,0.1

Type RM Length L Ch R = 1 ,53944   ,734,734,734
BEGIN DESCRIPTION:
Mapping XS c4c9a9f1
END DESCRIPTION:
XS GIS Cut Line= 6
       1439238.2      6903709.93      1439786.89      6902992.22
       1439917.1      6903000.03      1439984.81      6902924.51
      1440029.08      6902815.14      1439974.81      6902121.45
#Sta/Elev= 30
  3857.4 1890.17  4760.3 1885.71  4779.2 1886.44  4799.5  1889.6  4819.5 1889.86
  4824.6 1887.23  4853.4 1884.97  4853.9 1884.47  4862.8 1884.97  4863.1  1888.2
  4899.3 1885.35  4906.8 1889.49  4913.5 1887.34    4921 1890.61  4927.7 1888.48
  4935.2 1890.76  4941.9 1888.06  4956.1 1890.97  4990.2 1889.54  5000.8 1891.06
  5111.8 1890.73    5159 1886.71    5189 1885.85    5279 1889.32  5390.6 1890.19
  5478.4 1891.98  5549.1  1891.6  5685.4 1894.64  5728.6 1895.61  5810.9 1896.83
#Mann= 7 ,-1 , 0
  3857.4     .07       0  4853.4     .07       0  4862.8     .07       0
  5390.6     .16       0  5478.4     .07       0  5685.4    .035       0
  5728.6     .07       0
Bank Sta=4853.4,4862.8
XS Rating Curve= 0 ,0
Exp/Cntr=0.3,0.1

Type RM Length L Ch R = 1 ,53210   ,740,740,740
BEGIN DESCRIPTION:
Mapping XS a6e7ea80
END DESCRIPTION:
XS GIS Cut Line= 3
      1439887.05      6904180.89      1440273.87      6903263.05
      1440807.18       6901913.1
#Sta/Elev= 30
    4000 1886.75  4367.4 1885.51  4391.1 1886.59  4449.4 1884.15  4496.9    1885
  4665.1 1883.31  4741.1 1884.52  4871.3 1882.98  4925.5  1884.1  4956.5 1883.87
  4996.8 1880.22  4997.3 1879.72  5006.2 1880.22  5015.1  1883.1    5023 1883.42
  5055.2 1882.01  5123.3 1883.32  5141.2    1881  5172.1 1883.75  5208.1 1883.34
  5248.5 1882.94  5345.5 1882.02    5410 1884.85  5442.3 1883.19  5639.9 1884.19
  5688.7 1886.89    5694 1885.73  5711.1 1887.81  5742.8  1885.6  6447.5 1887.06
#Mann= 5 ,-1 , 0
    4000     .07       0  4996.8     .07       0  5006.2     .07       0
  5208.1    .035       0  5248.5     .07       0
Bank Sta=4996.8,5006.2
XS Rating Curve= 0 ,0
Exp/Cntr=0.3,0.1

Type RM Length L Ch R = 1 ,52470   ,968,968,968
BEGIN DESCRIPTION:
Mapping XS ba6dbc2c
END DESCRIPTION:
XS GIS Cut Line= 5
      1440490.35      6904706.05      1440838.98      6903572.95
      1441022.04      6902475.14      1441114.73      6901888.38
      1440330.37       6901380.4
#Sta/Elev= 30
  3814.4 1885.16  4120.1  1882.2  4283.2 1883.29  4359.5 1881.06  4734.8 1881.35
  4816.8 1879.66  4832.9 1881.23  4952.8  1882.3  4974.2 1881.21  4989.9 1878.19
  4990.4 1877.69  4999.3 1878.19  5015.1 1881.06  5063.8  1881.5  5124.6 1879.66
  5217.8 1882.28  5319.2 1882.15  5458.9 1880.71  6079.6 1883.13  6709.7 1882.33
    6896 1884.05  6923.1 1886.13  6938.2 1888.88  6953.4 1885.27  6974.5 1884.92
  7010.8 1886.75  7068.2 1886.71  7155.8 1889.75  7415.7 1894.75  7641.4 1893.64
#Mann= 5 ,-1 , 0
  3814.4     .07       0  4989.9     .07       0  4999.3     .07       0
  5319.2    .035       0  5458.9     .07       0
Bank Sta=4989.9,4999.3
XS Rating Curve= 0 ,0
Exp/Cntr=0.3,0.1

Type RM Length L Ch R = 1 ,51502   ,749,749,749
BEGIN DESCRIPTION:
Mapping XS 751a1bd6
END DESCRIPTION:
XS GIS Cut Line= 5
      1440568.45      6904627.95      1441349.39       6903669.3
      1441523.58      6903358.42      1441523.91      6901824.85
      1440361.61      6901300.53
#Sta/Elev= 30
  3771.9 1884.04  4054.2 1882.78  4089.4 1880.92  4118.2 1881.87  4223.7 1879.72
  4338.6 1881.68  4373.8 1879.43  4444.2  1880.1  4452.1 1878.26  4458.5 1879.71
  4494.1 1879.96    4636 1878.54    4949 1879.41  4984.3 1878.56  5007.9 1874.58
  5008.4 1874.08  5017.4 1874.58  5050.3 1878.43  5131.3 1879.98  5435.2 1877.37
  5685.2 1879.09  6908.2 1877.66  7138.5 1879.38  7312.4 1883.98  7317.8 1882.75
  7335.5 1883.88    7341  1882.2  7577.3  1884.7  7807.9 1890.56  8173.4 1892.81
#Mann= 3 ,-1 , 0
  3771.9     .07       0  5007.9     .07       0  5017.4     .07       0
Bank Sta=5007.9,5017.4
XS Rating Curve= 0 ,0
Exp/Cntr=0.3,0.1

Type RM Length L Ch R = 1 ,50753   ,36,36,36
BEGIN DESCRIPTION:
Mapping XS 102f8121
END DESCRIPTION:
XS GIS Cut Line= 6
      1440857.13      6904690.83      1441646.27      6904070.34
      1441737.41      6904018.26        1441727.      6903955.76
      1441631.84      6901765.69       1440031.8      6901109.58
#Sta/Elev= 30
  3837.2 1883.05  4607.2 1878.02    4628 1874.38  4671.3 1877.76  4692.2 1877.27
    4713 1873.24  4735.5 1876.31  4763.1 1873.77  4785.2 1877.13  4820.5 1877.11
  4838.9 1873.67  4850.8 1875.69  4856.5 1872.34  4872.5 1875.89  4878.2  1871.6
  4894.2 1875.37  4899.9 1872.28    4916 1875.39  4919.7 1871.87  4931.3 1873.29
  4932.5 1870.81    4933 1870.31    4942 1870.81  4986.5 1877.33  4991.6 1873.51
  5067.2 1881.48  5097.3 1877.85  7219.8 1877.04  8340.2  1891.3  8930.9 1896.23
#Mann= 3 ,-1 , 0
  3837.2     .07       0  4932.5     .07       0    4942     .07       0
Bank Sta=4932.5,4942
XS Rating Curve= 0 ,0
Exp/Cntr=0.3,0.1