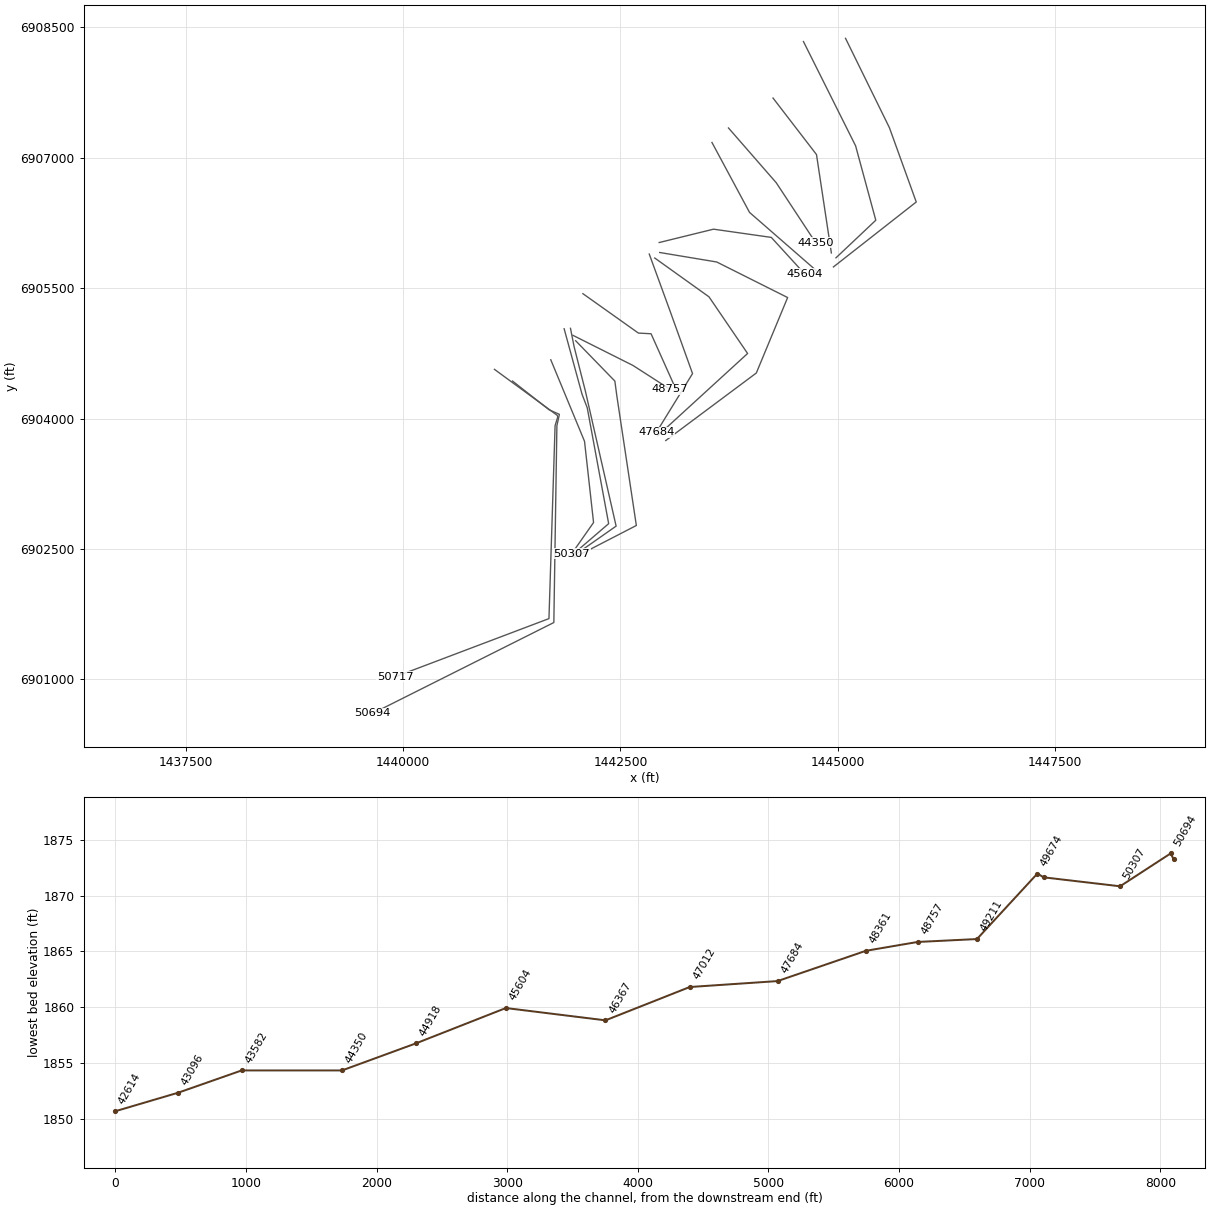
HEC-RAS study Raven Creek.prj: Raven Creek Base Level Engineering

--- Raven Creek.g01 (geometry) --- (continued)

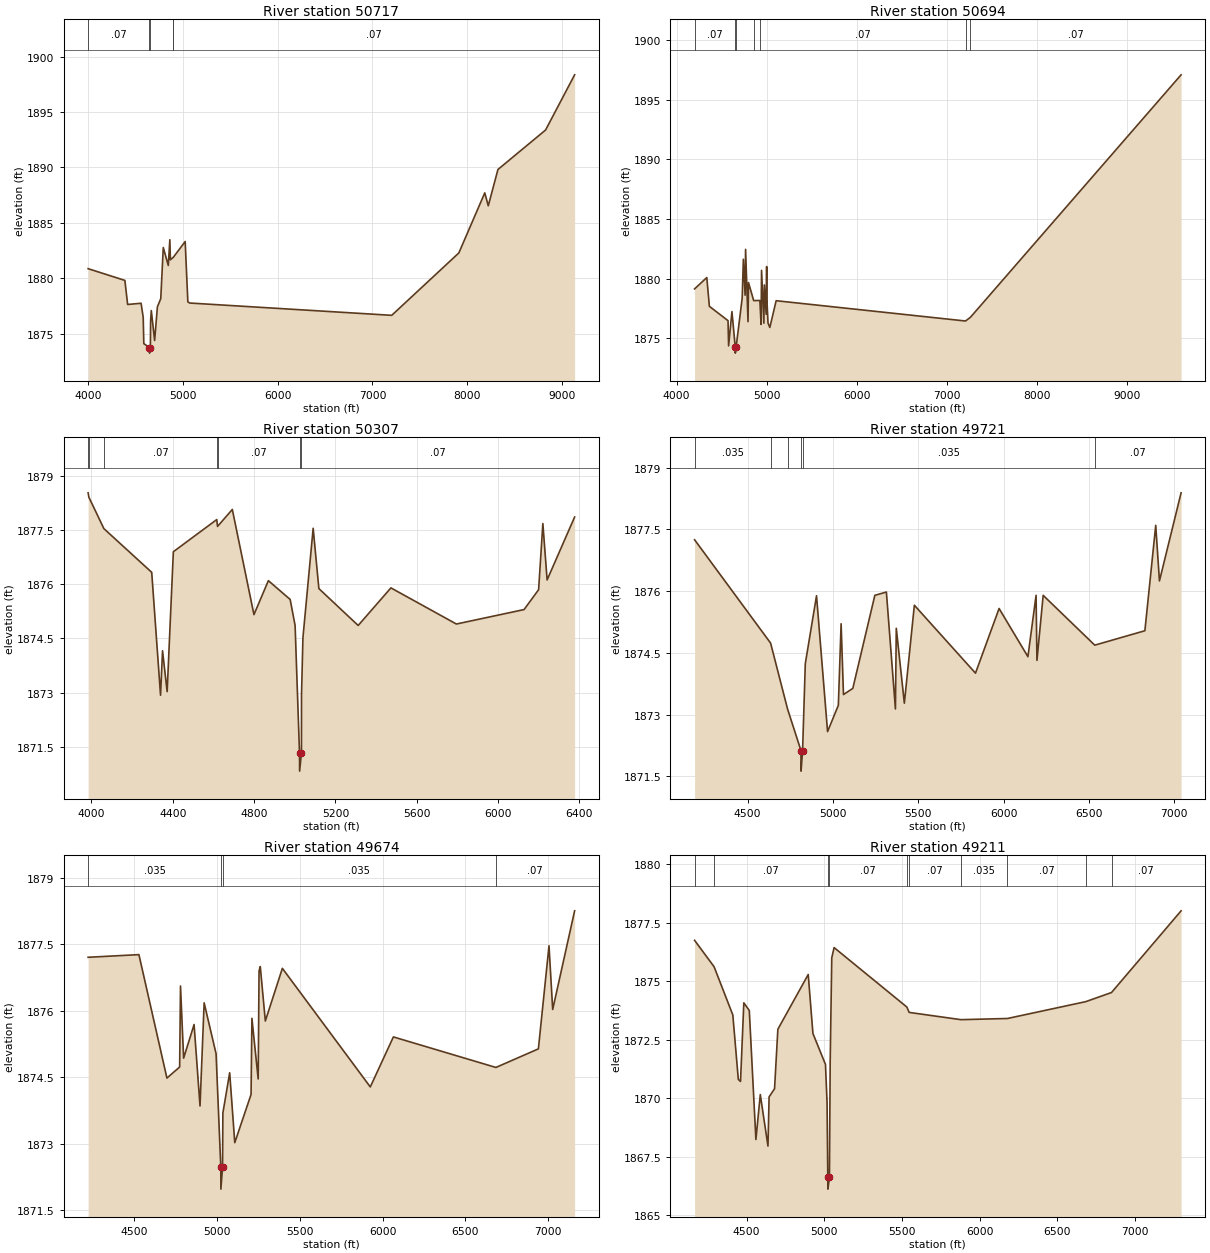
Type RM Length L Ch R = 1 ,50717   ,23,23,23
BEGIN DESCRIPTION:
Mapping XS edb62dd1
END DESCRIPTION:
XS GIS Cut Line= 6
      1441050.25      6904567.15      1441771.27      6904039.09
      1441779.08      6904020.87      1441747.83       6903919.3
      1441677.32      6901699.74      1439908.42      6901030.33
#Sta/Elev= 30
    4000 1880.86    4388  1879.8    4417 1877.63  4558.8 1877.74  4581.3 1876.47
  4587.6  1874.1  4647.3 1873.74  4647.8 1873.24  4656.8 1873.74  4659.4 1876.16
  4666.6 1877.08  4701.9 1874.38    4731 1877.42  4766.4 1878.15    4793 1882.77
    4846 1881.15  4862.3 1883.47    4868 1881.66  4894.7 1881.86  4896.5 1881.86
  5024.1 1883.31  5052.3 1877.86  5072.3 1877.76  7203.4 1876.65  7911.5 1882.28
  8185.1  1887.7  8221.9 1886.53  8324.1 1889.81  8826.6 1893.37    9133 1898.35
#Mann= 5 ,-1 , 0
    4000     .07       0  4647.3     .07       0  4656.8     .07       0
  4894.7    .035       0  4896.5     .07       0
Bank Sta=4647.3,4656.8
XS Rating Curve= 0 ,0
Exp/Cntr=0.3,0.1

Type RM Length L Ch R = 1 ,50694   ,387,387,387
BEGIN DESCRIPTION:
Mapping XS ed8b193c
END DESCRIPTION:
XS GIS Cut Line= 6
      1441258.21      6904432.35      1441680.12      6904101.59
      1441797.31      6904049.51      1441768.66       6903919.3
      1441733.53      6901654.65      1439649.88       6900609.6
#Sta/Elev= 30
  4200.1 1879.15  4335.8  1880.1  4364.3 1877.69  4571.4 1876.49  4577.7 1874.38
  4614.7 1877.25  4651.6 1874.27  4652.1 1873.77  4661.1 1874.27  4728.6 1878.39
  4741.4 1881.63  4760.9 1878.62  4766.1 1882.46  4793.2 1876.41  4798.5 1879.68
  4856.2 1878.17  4924.8 1878.18  4938.1 1876.18  4943.4  1880.7  4969.1 1876.28
  4974.4 1879.48  4994.8 1877.03  5000.1 1881.02  5002.1 1878.37  5015.3 1876.29
  5035.3 1875.92  5105.4 1878.16  7207.5 1876.46  7261.6 1876.77    9600 1897.08
#Mann= 7 ,-1 , 0
  4200.1     .07       0  4651.6     .07       0  4661.1     .07       0
  4856.2    .035       0  4924.8     .07       0  7207.5    .035       0
  7261.6     .07       0
Bank Sta=4651.6,4661.1
XS Rating Curve= 0 ,0
Exp/Cntr=0.3,0.1

Type RM Length L Ch R = 1 ,50307   ,586,586,586
BEGIN DESCRIPTION:
Mapping XS 924068fc
END DESCRIPTION:
XS GIS Cut Line= 4
      1441698.34      6904677.14      1442086.37      6903739.62
      1442190.48      6902805.03      1441939.29      6902446.59
#Sta/Elev= 30
  3983.6 1878.53  3987.3 1878.41  4061.1 1877.54  4296.4 1876.33  4339.8 1872.93
  4349.6 1874.16  4372.3 1873.03  4402.8  1876.9  4616.3 1877.79  4620.1  1877.6
  4692.8 1878.07  4799.2 1875.16  4870.1  1876.1  4977.3 1875.58  5001.6 1874.86
  5023.3 1871.33  5023.8 1870.83  5032.8 1871.33  5033.1 1872.94  5040.1 1874.52
  5090.4 1877.55  5118.5 1875.88  5311.8 1874.86  5472.8  1875.9  5794.8  1874.9
  6127.7  1875.3  6199.2 1875.85  6220.1 1877.68    6241 1876.12  6376.3 1877.86
#Mann= 7 ,-1 , 0
  3983.6     .07       0  3987.3    .035       0  4061.1     .07       0
  4616.3    .035       0  4620.1     .07       0  5023.3     .07       0
  5032.8     .07       0
Bank Sta=5023.3,5032.8
XS Rating Curve= 0 ,0
Exp/Cntr=0.3,0.1

Type RM Length L Ch R = 1 ,49721   ,47,47,47
BEGIN DESCRIPTION:
Mapping XS 4c7e33db
END DESCRIPTION:
XS GIS Cut Line= 5
        1441852.      6905033.88      1442057.73      6904281.28
      1442117.62      6904125.03      1442364.17      6902791.91
      1441948.84      6902434.84
#Sta/Elev= 30
  4188.9 1877.25  4634.4 1874.74  4733.7 1873.14  4812.3 1872.13  4812.8 1871.63
  4821.8 1872.13  4837.7 1874.24  4903.5 1875.89  4968.2 1872.59  5031.4 1873.23
  5047.6 1875.21  5061.5 1873.49  5116.2 1873.64  5245.3  1875.9  5312.9 1875.98
  5365.9 1873.14  5370.9  1875.1  5418.2 1873.28  5476.8 1875.66  5835.1 1874.01
  5973.4 1875.58  6142.3 1874.41  6190.1  1875.9  6195.2 1874.32  6231.7  1875.9
    6534 1874.69  6827.7 1875.04  6891.3  1877.6  6913.1 1876.25  7039.9 1878.39
#Mann= 6 ,-1 , 0
  4188.9    .035       0  4634.4     .07       0  4733.7    .035       0
  4812.3    .035       0  4821.8    .035       0    6534     .07       0
Bank Sta=4812.3,4821.8
XS Rating Curve= 0 ,0
Exp/Cntr=0.3,0.1

Type RM Length L Ch R = 1 ,49674   ,463,463,463
BEGIN DESCRIPTION:
Mapping XS 41a96f45
END DESCRIPTION:
XS GIS Cut Line= 5
      1441924.91      6905039.09      1441966.58      6904828.16
      1442096.79      6904315.14       1442449.9       6902763.8
      1441958.39      6902419.35
#Sta/Elev= 30
  4223.3 1877.21  4529.8 1877.27  4698.8 1874.48  4775.6 1874.73  4780.7 1876.56
  4799.6 1874.93  4862.7 1875.69  4898.5 1873.85  4923.4 1876.18  4995.4 1875.03
  5023.9 1872.47  5024.4 1871.97  5034.5 1872.47  5036.4 1873.69  5077.5  1874.6
  5108.2 1873.02  5206.5 1874.11  5211.6 1875.83  5249.5 1874.46  5254.7  1876.9
  5262.1    1877  5292.6 1875.77  5395.4 1876.96  5925.9 1874.28  6065.3 1875.41
  6683.9 1874.72  6940.2 1875.14  7004.2 1877.47  7026.5 1876.03  7158.8 1878.26
#Mann= 4 ,-1 , 0
  4223.3    .035       0  5023.9    .035       0  5034.5    .035       0
  6683.9     .07       0
Bank Sta=5023.9,5034.5
XS Rating Curve= 0 ,0
Exp/Cntr=0.3,0.1

Type RM Length L Ch R = 1 ,49211   ,454,454,454
BEGIN DESCRIPTION:
Mapping XS 250efc7e
END DESCRIPTION:
XS GIS Cut Line= 5
      1441984.79      6904895.89      1442435.33      6904432.32
      1442458.77      6904257.84      1442682.64        6902771.
      1441966.84      6902401.34
#Sta/Elev= 30
  4164.8 1876.74  4290.5 1875.61    4411 1873.55  4446.3  1870.8  4460.5 1870.71
  4481.8 1874.07    4517 1873.74  4559.5 1868.23  4587.8 1870.15  4637.2 1867.95
  4644.4 1870.05  4679.6  1870.4  4700.9 1872.94  4896.3 1875.28  4926.6 1872.76
  5007.3 1871.44  5017.5 1869.83  5022.3 1866.61  5022.8 1866.11  5032.9 1866.61
  5037.7 1871.52  5047.8 1875.99  5062.8 1876.43  5531.2 1873.89  5546.1 1873.66
  5879.4 1873.35  6178.8  1873.4    6683 1874.12  6848.7 1874.51  7296.5    1878
#Mann= 10 ,-1 , 0
  4164.8    .035       0  4290.5     .07       0  5022.3     .07       0
  5032.9     .07       0  5531.2    .035       0  5546.1     .07       0
  5879.4    .035       0  6178.8     .07       0    6683    .035       0
  6848.7     .07       0
Bank Sta=5022.3,5032.9
XS Rating Curve= 0 ,0
Exp/Cntr=0.3,0.1

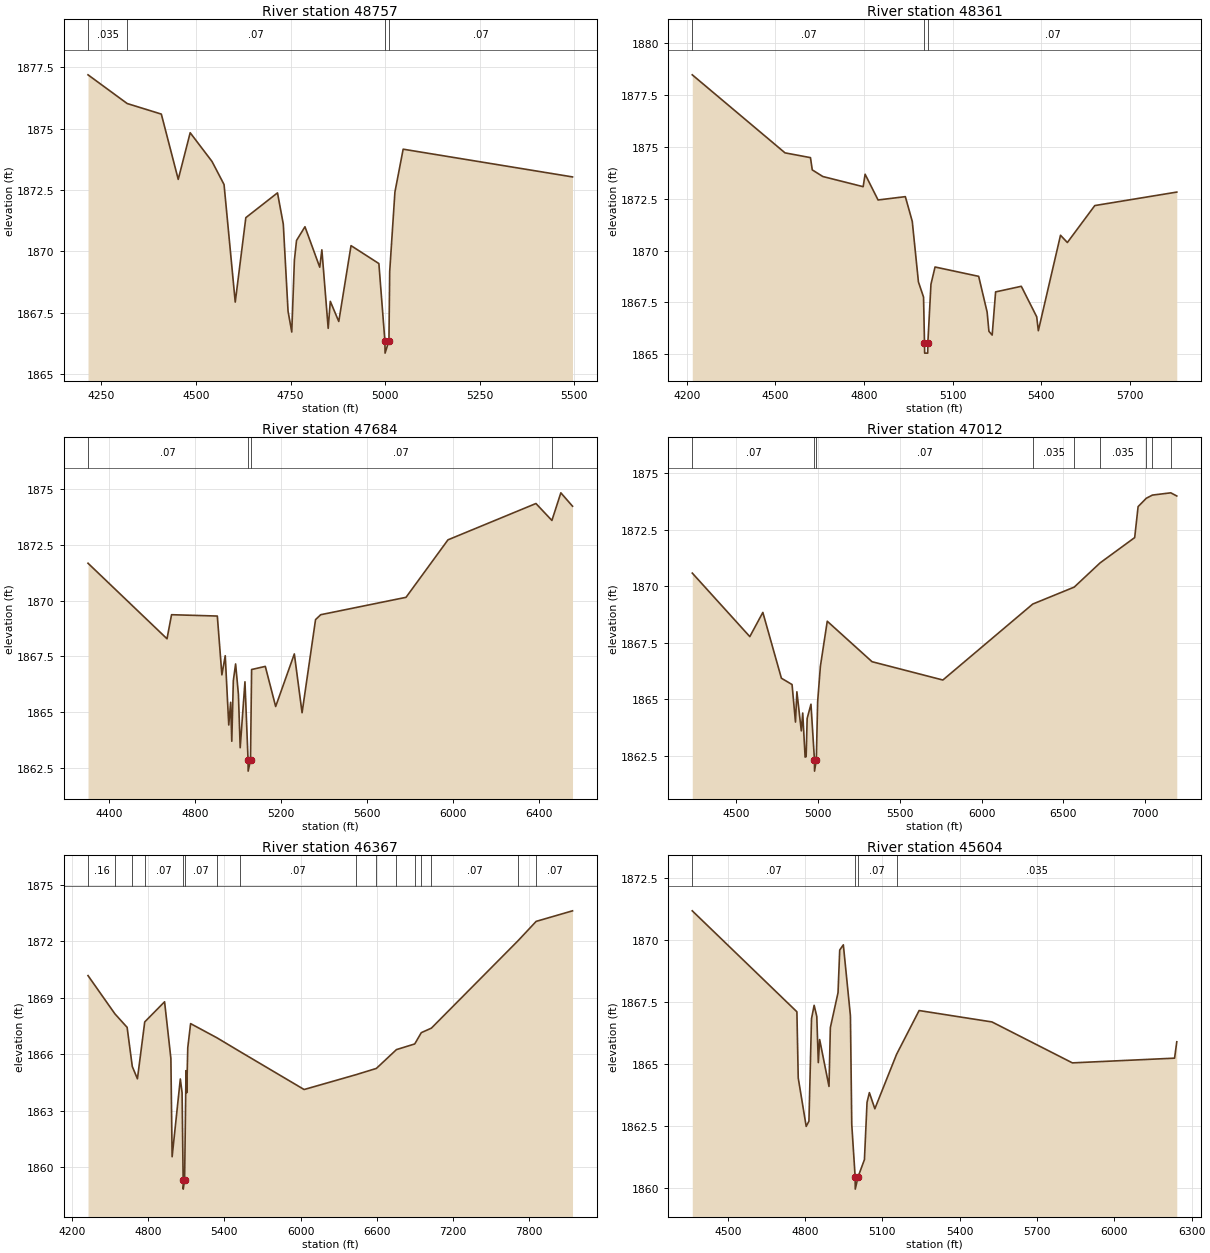
Type RM Length L Ch R = 1 ,48757   ,396,396,396
BEGIN DESCRIPTION:
Mapping XS 5621d85c
END DESCRIPTION:
XS GIS Cut Line= 3
       1441953.6      6904958.34      1442643.66      6904612.01
      1443071.66      6904337.06
#Sta/Elev= 30
  4214.4 1877.19    4318 1876.02  4408.2 1875.59  4452.9 1872.93  4484.5 1874.83
  4542.2 1873.66    4574 1872.72  4603.6 1867.93  4631.6 1871.37  4715.3 1872.38
  4730.6 1871.11  4743.2 1867.56    4753 1866.71    4760 1869.64  4765.6 1870.44
  4787.9    1871    4827 1869.35  4832.6 1870.06  4849.3 1866.86  4854.9 1867.96
  4877.3 1867.14  4909.7 1870.23  4983.3  1869.5  4999.2 1866.35  4999.7 1865.85
  5009.9 1866.35  5011.9 1869.17  5025.7 1872.41  5047.5 1874.16  5495.2 1873.03
#Mann= 4 ,-1 , 0
  4214.4    .035       0    4318     .07       0  4999.2     .07       0
  5009.9     .07       0
Bank Sta=4999.2,5009.9
XS Rating Curve= 0 ,0
Exp/Cntr=0.3,0.1

Type RM Length L Ch R = 1 ,48361   ,677,677,677
BEGIN DESCRIPTION:
Mapping XS b4dfedc0
END DESCRIPTION:
XS GIS Cut Line= 4
      1442068.18      6905437.51      1442706.16      6904984.41
        1442852.      6904976.59       1443142.6      6904327.98
#Sta/Elev= 30
  4218.8 1878.47  4532.6 1874.71  4618.7 1874.48  4624.8 1873.89  4660.5 1873.57
    4797 1873.08  4803.6 1873.68  4847.4 1872.44  4939.7  1872.6  4963.1 1871.41
    4984 1868.49  5001.3 1867.76  5004.5 1865.56    5005 1865.06  5015.4 1865.06
  5015.9 1865.56  5026.4 1868.38  5040.2 1869.21  5187.8 1868.76  5216.4 1867.04
  5222.5 1866.11  5233.5 1865.93  5245.1 1868.01  5332.1 1868.28  5384.2 1866.81
  5389.7 1866.14  5464.7 1870.74  5487.9 1870.39  5580.7 1872.17  5858.1 1872.82
#Mann= 3 ,-1 , 0
  4218.8     .07       0  5004.5     .07       0  5015.9     .07       0
Bank Sta=5004.5,5015.9
XS Rating Curve= 0 ,0
Exp/Cntr=0.3,0.1

Type RM Length L Ch R = 1 ,47684   ,672,672,672
BEGIN DESCRIPTION:
Raven Creek 31.0
END DESCRIPTION:
XS GIS Cut Line= 4
      1442831.16      6905893.26      1443070.18      6905238.53
      1443329.13      6904518.49      1442913.43      6903843.64
#Sta/Elev= 30
    4303 1871.68  4670.6 1868.29  4691.8 1869.37  4904.8 1869.31    4926 1866.67
  4941.6 1867.53    4958 1864.42  4966.8 1865.44  4972.1 1863.69  4979.3 1866.41
  4989.9 1867.16  5002.9  1865.8  5011.2  1863.4  5033.4 1866.36  5047.8 1862.85
  5048.3 1862.35  5059.2 1862.85  5064.3 1866.91  5128.1 1867.05  5176.3 1865.25
  5263.2 1867.61  5299.2 1864.97  5361.9 1869.15    5386 1869.37    5783 1870.15
  5978.2 1872.73  6387.6 1874.36  6461.9  1873.6  6503.5 1874.84  6557.8 1874.24
#Mann= 4 ,-1 , 0
    4303     .07       0  5047.8     .07       0  5059.2     .07       0
  6461.9    .035       0
Bank Sta=5047.8,5059.2
XS Rating Curve= 0 ,0
Exp/Cntr=0.3,0.1

Type RM Length L Ch R = 1 ,47012   ,645,645,645
BEGIN DESCRIPTION:
Raven Creek 30.0
END DESCRIPTION:
XS GIS Cut Line= 4
      1442894.47      6905847.66      1443518.42      6905401.26
      1443962.47      6904749.58      1442926.98      6903802.45
#Sta/Elev= 30
  4232.8 1870.58  4584.2 1867.77  4663.8 1868.84  4777.1 1865.93  4842.2 1865.65
  4863.1 1863.99  4871.7 1865.33  4898.7  1863.6  4907.3 1864.39    4922 1862.44
  4928.2 1862.46  4934.4 1864.15  4957.7 1864.78    4979 1862.32  4979.5 1861.82
  4990.4 1862.32  4998.5 1864.89  5015.3 1866.46  5057.2 1868.45  5330.7 1866.66
  5763.3 1865.85  6312.2 1869.21  6565.6 1869.96  6723.4 1871.03  6934.8 1872.15
  6955.7 1873.52  7005.8 1873.89  7043.1 1874.03  7155.3 1874.13  7191.9 1873.99
#Mann= 9 ,-1 , 0
  4232.8     .07       0    4979     .07       0  4990.4     .07       0
  6312.2    .035       0  6565.6     .07       0  6723.4    .035       0
  7005.8     .07       0  7043.1    .035       0  7155.3     .07       0
Bank Sta=4979,4990.4
XS Rating Curve= 0 ,0
Exp/Cntr=0.3,0.1

Type RM Length L Ch R = 1 ,46367   ,763,763,763
BEGIN DESCRIPTION:
Mapping XS 12097135
END DESCRIPTION:
XS GIS Cut Line= 5
      1442950.99      6905911.48       1443607.2      6905802.12
      1444422.97      6905393.11      1444062.73      6904525.05
       1443021.1      6903748.17
#Sta/Elev= 30
  4325.4 1870.18  4537.1 1868.15  4633.6 1867.43  4674.3 1865.35  4714.7  1864.7
  4772.3 1867.72  4928.6 1868.79  4978.3 1865.78    4988 1860.56  5052.7 1864.69
  5066.5 1863.96  5074.9 1859.34  5075.4 1858.84  5086.4 1859.34  5097.4 1865.13
    5103 1863.96  5111.3 1866.35  5133.6 1867.63  5342.9 1866.87  5523.9 1866.14
  6027.9 1864.13  6432.8 1864.91    6597 1865.25  6755.4 1866.25  6899.4 1866.55
  6951.1 1867.15  7030.7 1867.39  7713.1 1872.03  7856.2 1873.06  8142.5 1873.62
#Mann= 16 ,-1 , 0
  4325.4     .16       0  4537.1     .07       0  4674.3     .16       0
  4772.3     .07       0  5074.9     .07       0  5086.4     .07       0
  5342.9    .035       0  5523.9     .07       0  6432.8    .035       0
    6597     .07       0  6755.4    .035       0  6899.4     .07       0
  6951.1    .035       0  7030.7     .07       0  7713.1    .035       0
  7856.2     .07       0
Bank Sta=5074.9,5086.4
XS Rating Curve= 0 ,0
Exp/Cntr=0.3,0.1

Type RM Length L Ch R = 1 ,45604   ,686,686,686
BEGIN DESCRIPTION:
Mapping XS d27cc80f
END DESCRIPTION:
XS GIS Cut Line= 4
      1442945.73      6906026.07      1443570.75      6906179.72
      1444235.11      6906084.99      1444616.65      6905667.61
#Sta/Elev= 30
  4362.1 1871.16  4768.1 1867.09  4773.3 1864.42  4804.2 1862.47  4814.8 1862.68
  4824.8 1866.81    4835 1867.35  4845.3  1866.9  4851.2 1865.04  4856.4 1865.97
  4892.7 1864.08  4897.9 1866.45  4927.7 1867.86  4934.3 1869.58  4948.3 1869.79
  4975.8 1866.93    4981 1862.55  4994.1 1860.44  4994.6 1859.94  5005.6 1860.44
  5030.2 1861.13  5040.3 1863.44  5049.4 1863.83  5070.6 1863.18  5154.7 1865.37
  5242.4 1867.14  5525.2 1866.68  5837.2 1865.03  6233.7 1865.22  6242.3 1865.88
#Mann= 4 ,-1 , 0
  4362.1     .07       0  4994.1     .07       0  5005.6     .07       0
  5154.7    .035       0
Bank Sta=4994.1,5005.6
XS Rating Curve= 0 ,0
Exp/Cntr=0.3,0.1

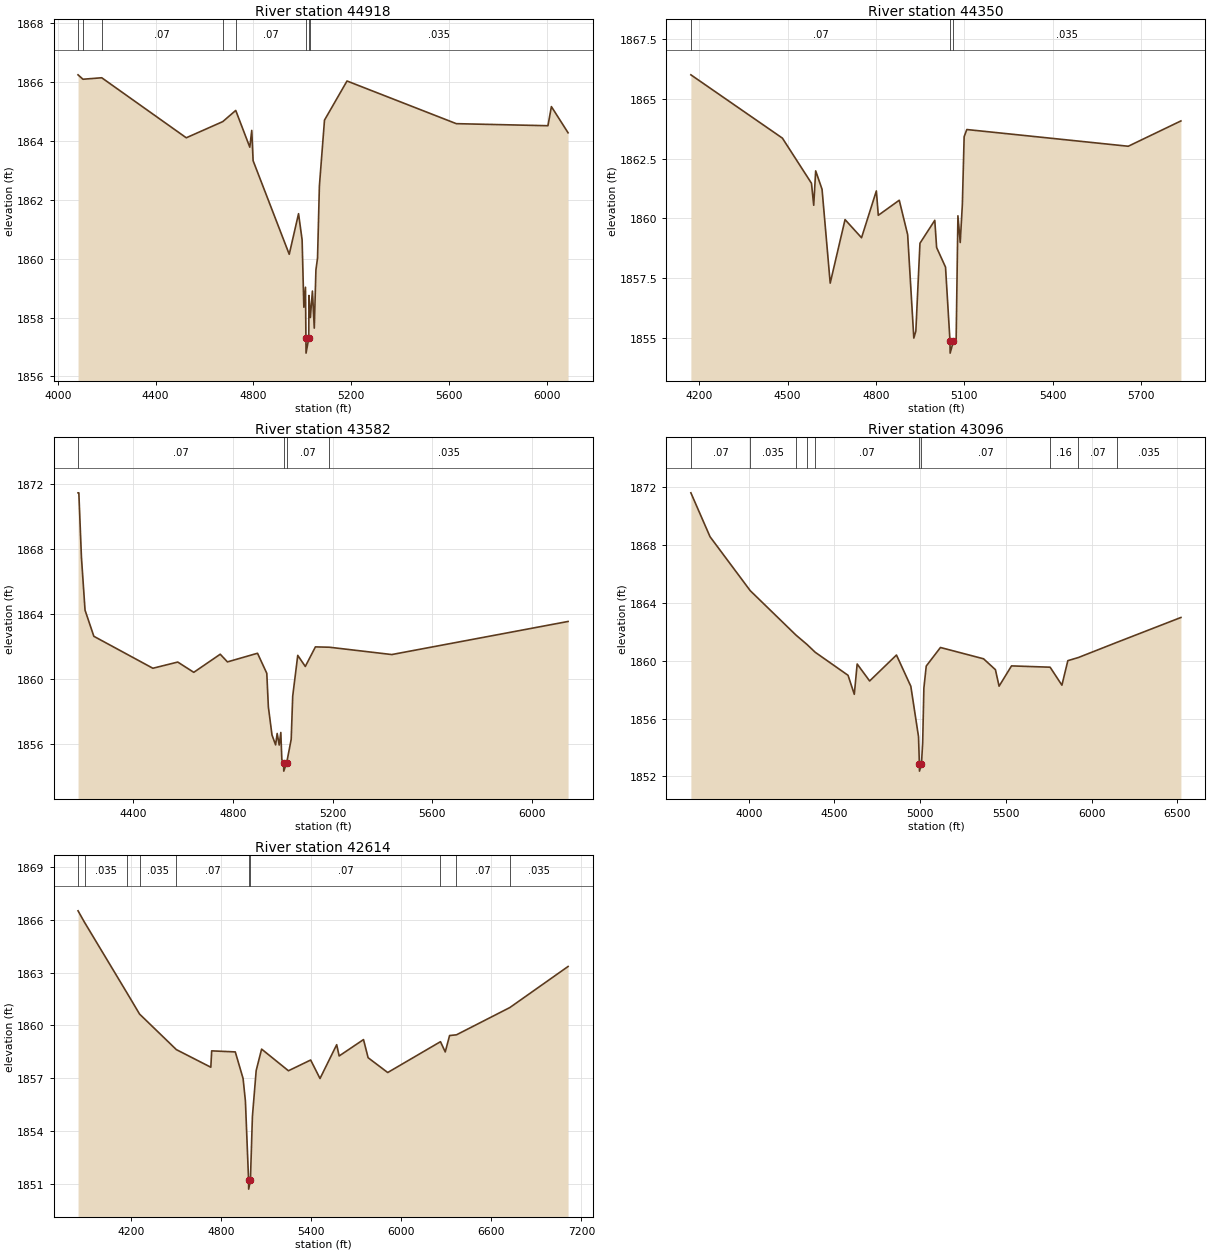
Type RM Length L Ch R = 1 ,44918   ,568,568,568
BEGIN DESCRIPTION:
Mapping XS 7f7ed171
END DESCRIPTION:
XS GIS Cut Line= 3
      1443552.54      6907177.08      1443984.81      6906372.43
      1444808.04      6905655.28
#Sta/Elev= 30
  4082.4 1866.25  4102.5  1866.1  4179.4 1866.15  4525.3 1864.11  4674.7 1864.66
  4727.7 1865.04  4785.2 1863.79  4793.2 1864.36  4798.8 1863.33  4946.6 1860.15
  4984.7 1861.53  4999.3 1860.64  5006.4 1858.35  5013.1 1859.03  5014.9 1857.29
  5015.4 1856.79  5026.5 1857.29  5027.3 1858.75    5033    1858  5041.5  1858.9
  5049.1 1857.64  5055.8 1859.62  5062.4 1860.02    5070 1862.47  5090.9 1864.71
    5183 1866.04  5630.2 1864.59  6005.2 1864.52  6019.4 1865.17  6087.6 1864.28
#Mann= 8 ,-1 , 0
  4082.4     .07       0  4102.5     .16       0  4179.4     .07       0
  4674.7    .035       0  4727.7     .07       0  5014.9     .07       0
  5026.5     .07       0    5033    .035       0
Bank Sta=5014.9,5026.5
XS Rating Curve= 0 ,0
Exp/Cntr=0.3,0.1

Type RM Length L Ch R = 1 ,44350   ,768,768,768
BEGIN DESCRIPTION:
Mapping XS 03004315
END DESCRIPTION:
XS GIS Cut Line= 3
      1443742.65      6907343.74       1444292.1      6906713.57
      1444747.15       6906021.9
#Sta/Elev= 30
  4171.4 1866.01  4482.2 1863.36  4580.9 1861.47  4588.5 1860.55  4595.2 1861.99
  4616.8 1861.22  4644.5 1857.29  4694.9 1859.95  4750.9 1859.19  4801.2 1861.15
  4807.8 1860.13    4879 1860.76  4907.5 1859.32  4928.4 1854.99  4935.3 1855.28
  4949.3 1858.96  4999.6 1859.92  5005.9 1858.78  5036.1 1857.96  5051.3 1854.86
  5051.8 1854.36  5062.9 1854.86  5072.2 1854.95  5078.2 1860.11    5086 1858.99
  5093.3 1860.59  5099.3 1863.42  5108.4 1863.72  5656.6 1863.02  5835.4 1864.08
#Mann= 3 ,-1 , 0
  4171.4     .07       0  5051.3     .07       0  5062.9    .035       0
Bank Sta=5051.3,5062.9
XS Rating Curve= 0 ,0
Exp/Cntr=0.3,0.1

Type RM Length L Ch R = 1 ,43582   ,486,486,486
BEGIN DESCRIPTION:
Raven Creek 29.0
END DESCRIPTION:
XS GIS Cut Line= 3
      1444254.97      6907688.04        1444755.        6907038.
      1444925.92      6905906.44
#Sta/Elev= 30
  4179.9 1871.43  4183.1 1871.43  4193.5 1867.48    4208 1864.23  4243.3 1862.63
  4479.9 1860.67  4579.6 1861.05  4643.9 1860.42  4749.9 1861.53  4778.9 1861.06
  4899.4 1861.59  4936.6 1860.36  4942.9  1858.3  4957.4 1856.58  4971.9 1855.97
  4978.2 1856.67  4986.4 1855.96  4992.8 1856.73  4996.9 1855.07  5004.1 1854.86
  5004.6 1854.36  5016.2 1854.86  5034.4 1856.31  5040.5 1858.96  5060.7 1861.46
    5091 1860.78  5131.5 1861.98  5187.2 1861.96  5437.6 1861.51  6144.4 1863.54
#Mann= 4 ,-1 , 0
  4179.9     .07       0  5004.1     .07       0  5016.2     .07       0
  5187.2    .035       0
Bank Sta=5004.1,5016.2
XS Rating Curve= 0 ,0
Exp/Cntr=0.3,0.1

Type RM Length L Ch R = 1 ,43096   ,482,482,482
BEGIN DESCRIPTION:
Raven Creek 28.0
END DESCRIPTION:
XS GIS Cut Line= 4
      1444604.99      6908338.03        1445205.        6907138.
      1445437.17      6906282.34      1444978.99      6905850.04
#Sta/Elev= 30
  3662.5 1871.57  3774.3 1868.54  4008.7 1864.82  4275.9 1861.75  4339.7 1861.11
  4387.7 1860.57  4579.3 1858.98  4615.7 1857.67  4632.4 1859.76  4705.1 1858.59
  4861.6 1860.38  4945.5 1858.22  4990.2 1854.75  4995.3 1852.87  4995.8 1852.37
  5007.4 1852.87  5014.5 1854.33  5021.5  1858.1  5035.3 1859.62  5118.2  1860.9
  5369.5 1860.12  5438.8 1859.37  5460.1 1858.23  5532.6 1859.63  5757.9 1859.54
  5826.6  1858.3  5861.2 1859.99  5923.1 1860.21  6146.4 1861.25  6520.7 1862.97
#Mann= 10 ,-1 , 0
  3662.5     .07       0  4008.7    .035       0  4275.9     .07       0
  4339.7    .035       0  4387.7     .07       0  4995.3     .07       0
  5007.4     .07       0  5757.9     .16       0  5923.1     .07       0
  6146.4    .035       0
Bank Sta=4995.3,5007.4
XS Rating Curve= 0 ,0
Exp/Cntr=0.3,0.1

Type RM Length L Ch R = 1 ,42614   ,835,835,835
BEGIN DESCRIPTION:
Mapping XS 7178e980
END DESCRIPTION:
XS GIS Cut Line= 4
      1445088.98      6908375.03      1445594.18      6907346.39
      1445902.49      6906492.34      1444949.69       6905745.2
#Sta/Elev= 30
  3846.7 1866.51  3889.8 1865.86  4172.8 1861.85  4256.5 1860.65  4501.8 1858.63
  4731.4 1857.63    4737 1858.56  4894.3  1858.5  4946.3 1856.99  4961.8 1855.71
    4983 1851.21  4983.5 1850.71  4995.1 1851.21  5008.4 1854.83  5033.5 1857.44
  5069.7 1858.66  5248.5 1857.43  5396.5 1858.04  5458.8 1856.99  5569.9 1858.91
  5586.4 1858.27  5748.6  1859.2  5779.3 1858.17  5909.9 1857.33  6261.4 1859.08
  6293.2  1858.5  6322.1 1859.43  6367.8 1859.47  6723.8 1861.02  7111.5 1863.35
#Mann= 10 ,-1 , 0
  3846.7     .07       0  3889.8    .035       0  4172.8     .07       0
  4256.5    .035       0  4501.8     .07       0    4983     .07       0
  4995.1     .07       0  6261.4     .16       0  6367.8     .07       0
  6723.8    .035       0
Bank Sta=4983,4995.1
XS Rating Curve= 0 ,0
Exp/Cntr=0.3,0.1