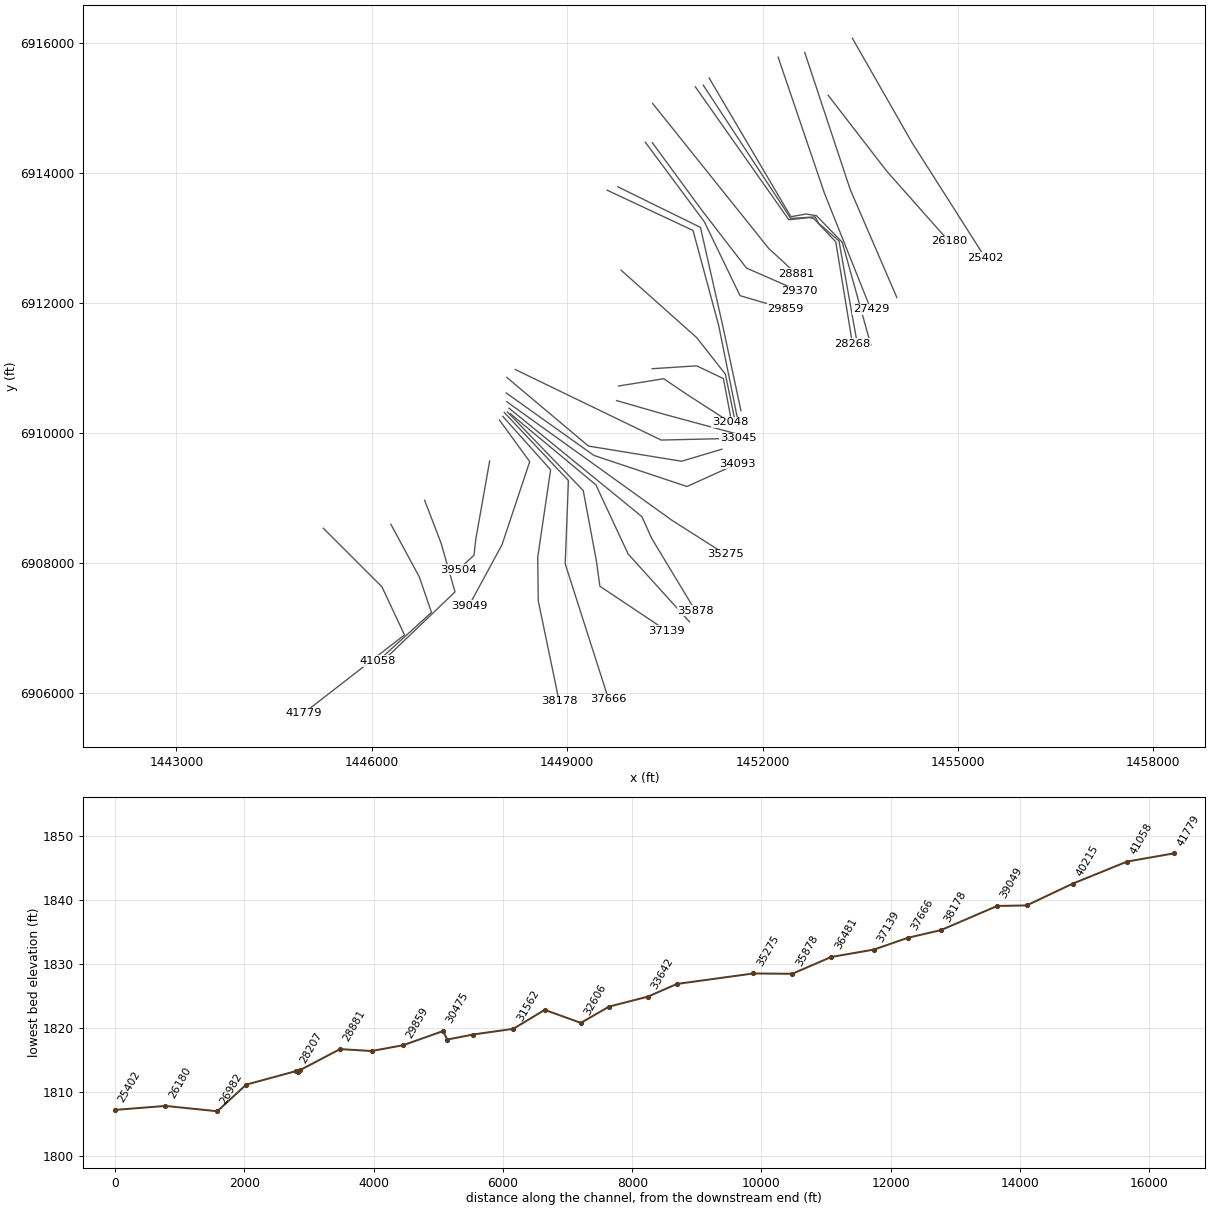
HEC-RAS study Raven Creek.prj: Raven Creek Base Level Engineering

--- Raven Creek.g01 (geometry) --- (continued)

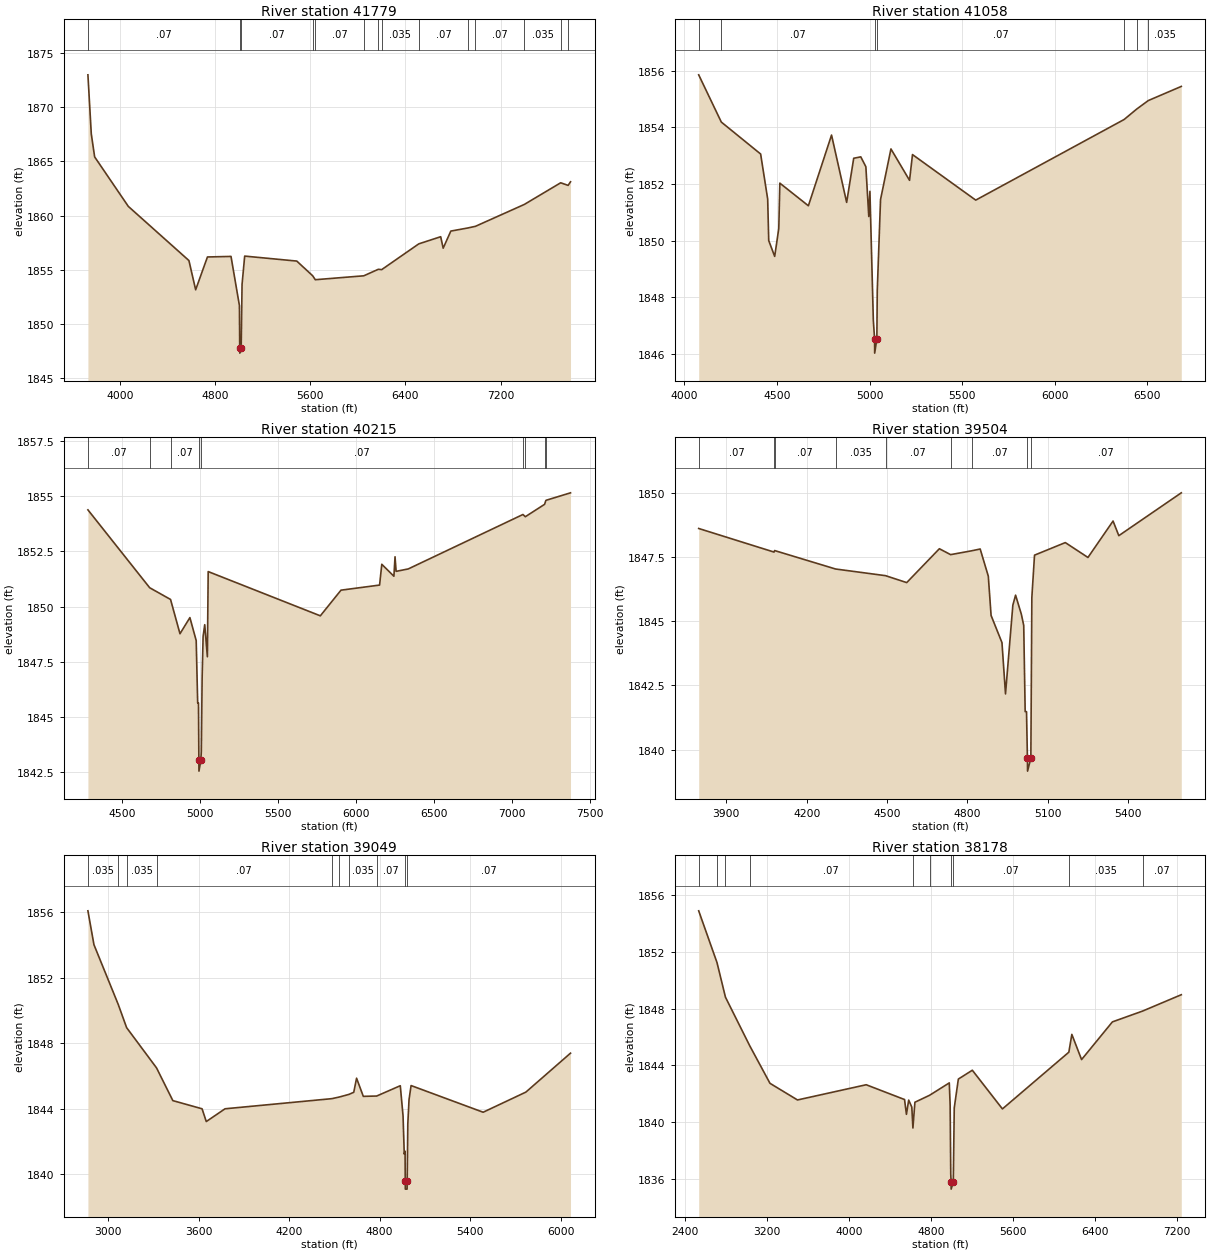
Type RM Length L Ch R = 1 ,41779   ,721,721,721
BEGIN DESCRIPTION:
Raven Creek 27.0
END DESCRIPTION:
XS GIS Cut Line= 4
        1445255.        6908538.        1446155.        6907638.
      1446501.45      6906898.59      1444949.78      6905693.19
#Sta/Elev= 30
  3732.3    1873  3760.6 1867.54  3788.9 1865.42  4071.7 1860.85  4580.8 1855.85
  4637.4 1853.15  4736.4 1856.18  4934.4 1856.23  5005.1 1851.69  5007.6  1847.8
  5008.1  1847.3  5019.8  1847.8  5027.2 1853.65  5049.3 1856.26  5486.9  1855.8
  5620.8 1854.44  5642.4 1854.08  6049.6 1854.44  6171.7 1855.04  6200.1 1855.01
  6511.9 1857.39  6695.9 1858.05  6716.8 1856.99    6781 1858.57  6925.2 1858.86
  6987.9 1859.01  7398.4 1861.03  7703.9 1863.03  7766.4 1862.79  7786.5 1863.12
#Mann= 14 ,-1 , 0
  3732.3     .07       0  5007.6     .07       0  5019.8     .07       0
  5620.8    .035       0  5642.4     .07       0  6049.6    .035       0
  6171.7     .07       0  6200.1    .035       0  6511.9     .07       0
  6925.2     .16       0  6987.9     .07       0  7398.4    .035       0
  7703.9     .07       0  7766.4    .035       0
Bank Sta=5007.6,5019.8
XS Rating Curve= 0 ,0
Exp/Cntr=0.3,0.1

Type RM Length L Ch R = 1 ,41058   ,843,843,843
BEGIN DESCRIPTION:
Mapping XS 4f9c22e2
END DESCRIPTION:
XS GIS Cut Line= 4
      1446292.08      6908599.02       1446729.6      6907789.09
      1446915.51      6907244.95      1446095.21      6906497.56
#Sta/Elev= 30
  4077.7 1855.86  4199.8 1854.19  4412.1 1853.06  4450.1 1851.47  4455.8    1850
    4488 1849.44  4510.1 1850.43  4515.8 1852.03  4669.9 1851.23  4794.9 1853.73
  4876.5 1851.35  4914.6 1852.91  4952.7 1852.96  4980.2 1852.61    4996 1850.85
  5002.1 1851.74  5020.5 1847.18  5027.3 1846.52  5027.8 1846.02  5039.5 1846.52
  5041.7 1848.22  5059.4 1851.45  5115.6 1853.24    5216 1852.13  5231.9 1853.04
  5573.3 1851.43  6374.3 1854.28  6442.5 1854.65  6504.9 1854.95    6683 1855.45
#Mann= 7 ,-1 , 0
  4077.7    .035       0  4199.8     .07       0  5027.3     .07       0
  5039.5     .07       0  6374.3    .035       0  6442.5     .07       0
  6504.9    .035       0
Bank Sta=5027.3,5039.5
XS Rating Curve= 0 ,0
Exp/Cntr=0.3,0.1

Type RM Length L Ch R = 1 ,40215   ,711,711,711
BEGIN DESCRIPTION:
Mapping XS 0a29a4a3
END DESCRIPTION:
XS GIS Cut Line= 4
      1446810.33      6908968.78      1447062.93      6908309.93
      1447277.49      6907560.05      1446116.06      6906445.49
#Sta/Elev= 30
  4282.9 1854.37    4679 1850.85  4812.9 1850.32  4873.4 1848.77    4937  1849.5
  4977.4 1848.46  4986.9 1845.64  4992.1 1845.64  4994.6 1843.06  4995.1 1842.56
  5007.3 1843.06  5010.2 1843.44  5015.4 1846.75  5021.7 1848.65  5032.1 1849.18
  5049.1 1847.73  5054.3 1851.58  5773.6 1849.58  5906.1 1850.74  6153.6 1850.97
  6167.8 1851.91  6245.5 1851.37  6252.7 1852.25  6259.6 1851.59  6337.6  1851.7
    7073 1854.16  7088.5 1854.06  7211.9 1854.62  7220.4  1854.8  7378.2 1855.14
#Mann= 9 ,-1 , 0
  4282.9     .07       0    4679    .035       0  4812.9     .07       0
  4994.6     .07       0  5007.3     .07       0    7073    .035       0
  7088.5     .07       0  7211.9    .035       0  7220.4     .07       0
Bank Sta=4994.6,5007.3
XS Rating Curve= 0 ,0
Exp/Cntr=0.3,0.1

Type RM Length L Ch R = 1 ,39504   ,455,455,455
BEGIN DESCRIPTION:
Mapping XS f7468962
END DESCRIPTION:
XS GIS Cut Line= 4
      1447809.33      6909572.44      1447596.79      6908372.43
      1447568.43      6908122.94      1447325.02      6907898.31
#Sta/Elev= 30
  3797.1 1848.62  4078.3  1847.7  4080.3 1847.76  4307.9 1847.04  4494.5 1846.78
  4573.4 1846.51  4695.3 1847.83  4737.3  1847.6  4815.8 1847.75  4847.6 1847.82
  4877.9 1846.76  4888.3 1845.23  4928.9 1844.17  4942.1 1842.17  4969.5 1845.63
  4979.7 1846.02  5001.2 1845.28  5010.1 1844.84  5015.5 1841.48  5020.5 1841.48
  5023.9 1839.66  5024.4 1839.16  5036.7 1839.66  5040.4 1845.93  5050.4 1847.58
  5165.3 1848.07  5249.8 1847.49  5343.5 1848.91    5365 1848.34  5598.1 1850.01
#Mann= 9 ,-1 , 0
  3797.1     .07       0  4078.3    .035       0  4080.3     .07       0
  4307.9    .035       0  4494.5     .07       0  4737.3    .035       0
  4815.8     .07       0  5023.9     .07       0  5036.7     .07       0
Bank Sta=5023.9,5036.7
XS Rating Curve= 0 ,0
Exp/Cntr=0.3,0.1

Type RM Length L Ch R = 1 ,39049   ,871,871,871
BEGIN DESCRIPTION:
Mapping XS 2452d025
END DESCRIPTION:
XS GIS Cut Line= 4
      1447959.91      6910200.13      1448424.33      6909562.09
      1447999.34      6908285.54      1447491.18      6907348.57
#Sta/Elev= 30
  2865.4 1856.09  2905.4 1854.02  3066.4 1850.37  3122.1 1848.95  3320.5 1846.49
  3428.6 1844.49  3622.5 1843.99  3650.3 1843.21  3774.8 1843.99  4483.5 1844.61
  4532.6 1844.71  4596.5 1844.87  4628.5    1845    4647 1845.86  4691.8 1844.75
  4780.4 1844.77    4937  1845.4  4955.3 1843.56  4963.4 1841.22  4968.7  1841.4
  4969.9 1839.58  4970.4 1839.08  4982.2 1839.08  4982.7 1839.58  4986.9 1843.07
    4995 1844.55  5008.6 1845.41  5486.6 1843.78  5769.9 1845.01  6065.9 1847.39
#Mann= 10 ,-1 , 0
  2865.4    .035       0  3066.4     .07       0  3122.1    .035       0
  3320.5     .07       0  4483.5    .035       0  4532.6     .07       0
  4596.5    .035       0  4780.4     .07       0  4969.9     .07       0
  4982.7     .07       0
Bank Sta=4969.9,4982.7
XS Rating Curve= 0 ,0
Exp/Cntr=0.3,0.1

Type RM Length L Ch R = 1 ,38178   ,512,512,512
BEGIN DESCRIPTION:
Mapping XS 1d946fbd
END DESCRIPTION:
XS GIS Cut Line= 5
      1448012.02      6910256.51      1448745.51      6909436.22
      1448547.31      6908091.18      1448555.85      6907421.25
      1448877.03      6905876.13
#Sta/Elev= 30
  2534.7 1854.87  2713.4 1851.23  2795.7  1848.8  3030.5 1845.41  3230.2 1842.74
  3498.6 1841.57    4169 1842.64    4543  1841.6  4561.4 1840.56  4583.5 1841.56
  4613.8 1841.07  4624.6  1839.6  4644.1 1841.41  4787.4  1841.9  4979.5 1842.77
  4987.8 1841.21  4993.8 1836.35  4997.2  1835.8  4997.7  1835.3  5018.5  1835.8
  5027.9 1841.01  5067.9 1843.04  5204.3 1843.66  5497.9 1840.94  6145.9 1844.93
    6175 1846.18  6270.1 1844.41  6570.7 1847.06  6864.9 1847.82  7242.8 1848.97
#Mann= 10 ,-1 , 0
  2534.7    .035       0  2713.4     .07       0  2795.7    .035       0
  3030.5     .07       0  4624.6    .035       0  4787.4     .07       0
  4997.2     .07       0  5018.5     .07       0  6145.9    .035       0
  6864.9     .07       0
Bank Sta=4997.2,5018.5
XS Rating Curve= 0 ,0
Exp/Cntr=0.3,0.1

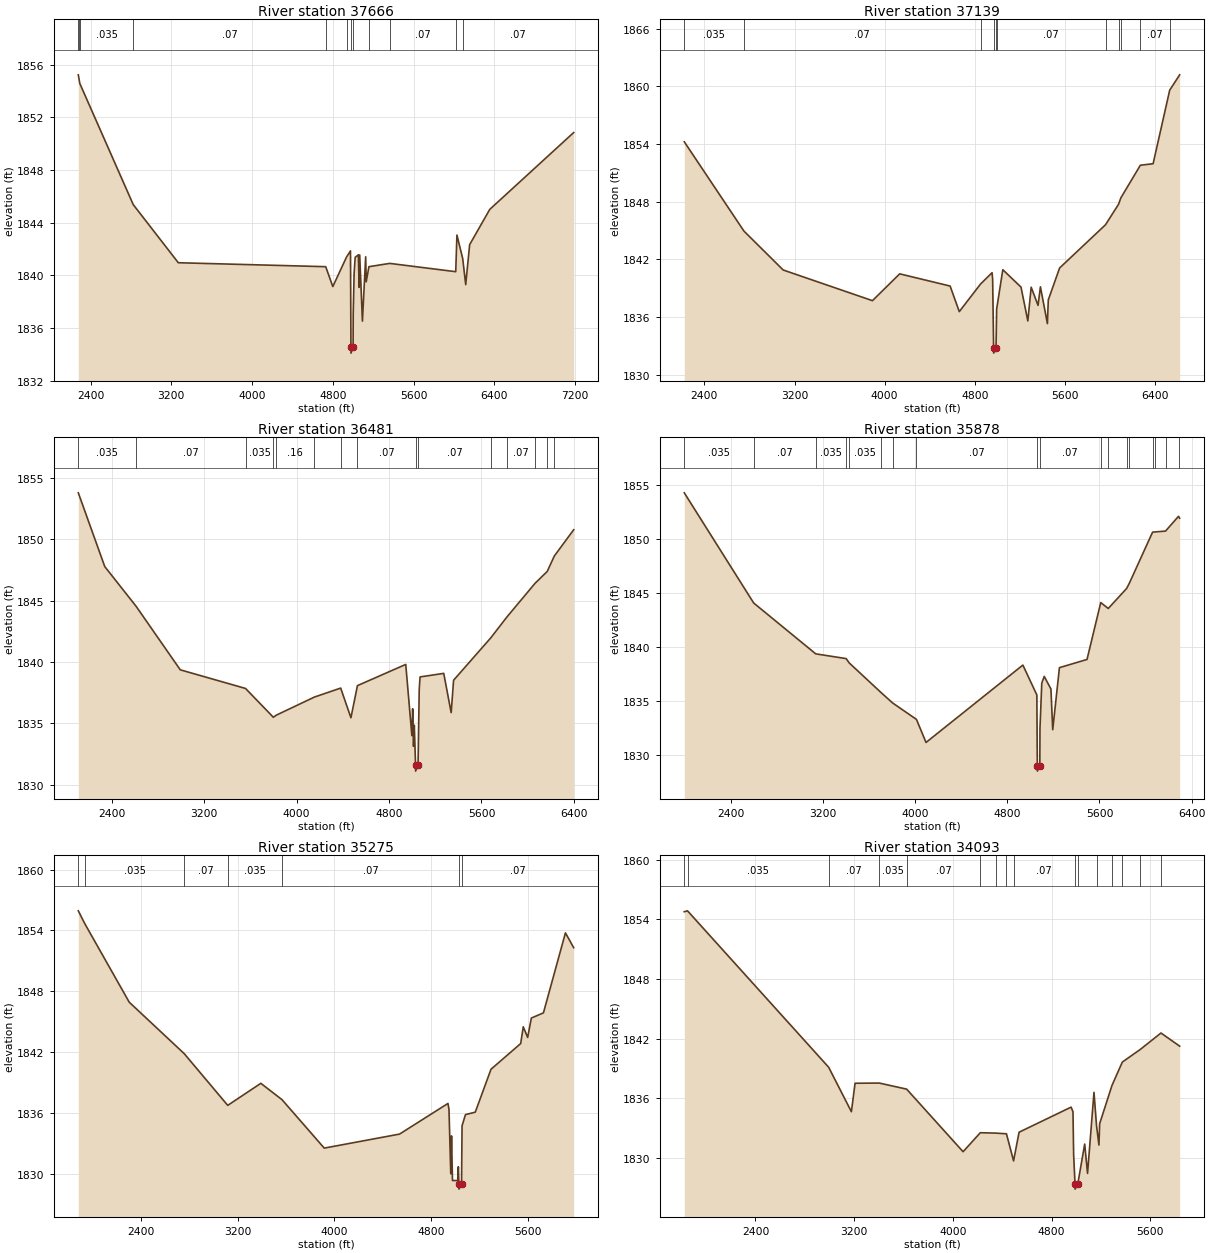
Type RM Length L Ch R = 1 ,37666   ,527,527,527
BEGIN DESCRIPTION:
Mapping XS da95783f
END DESCRIPTION:
XS GIS Cut Line= 4
      1448033.74      6910317.27      1449018.95      6909271.29
      1448969.18      6907992.22       1449636.6      6905906.45
#Sta/Elev= 30
  2278.4 1855.22  2289.9 1854.71  2293.5 1854.56  2822.6 1845.37    3269 1840.96
    4729 1840.66  4799.4 1839.15  4935.1 1841.39  4974.5 1841.86  4978.9  1834.6
  4979.4  1834.1  5000.3  1834.6  5001.5 1837.07  5010.3 1840.15  5020.8 1841.37
  5052.3 1841.56  5060.6 1839.09  5065.8 1841.55  5092.7 1836.53  5124.9 1841.41
  5130.1 1839.51    5157 1840.66  5363.4 1840.91  6016.9 1840.28  6028.7 1843.06
    6086 1841.28  6115.8  1839.3  6154.7 1842.33  6354.2 1845.01  7185.3 1850.84
#Mann= 12 ,-1 , 0
  2278.4    .035       0  2289.9     .07       0  2293.5    .035       0
  2822.6     .07       0    4729    .035       0  4935.1     .07       0
  4978.9     .07       0  5000.3     .07       0    5157     .16       0
  5363.4     .07       0  6016.9    .035       0    6086     .07       0
Bank Sta=4978.9,5000.3
XS Rating Curve= 0 ,0
Exp/Cntr=0.3,0.1

Type RM Length L Ch R = 1 ,37139   ,658,658,658
BEGIN DESCRIPTION:
Mapping XS 62409763
END DESCRIPTION:
XS GIS Cut Line= 5
      1448081.46      6910325.97      1449245.96       6909118.3
      1449448.35      6908036.49      1449502.03      6907646.94
        1450521.      6906966.19
#Sta/Elev= 30
  2221.6 1854.24  2751.2 1844.95  3099.6  1840.9  3891.7 1837.71  4133.5  1840.5
  4581.2 1839.23  4662.6 1836.57  4851.1 1839.44  4953.5 1840.62  4958.6 1839.92
  4967.2 1832.75  4967.7 1832.25  4988.6 1832.75  4994.1 1836.83  5048.8 1840.93
  5210.3 1839.12  5270.9  1835.6  5300.5 1839.11  5361.7 1837.22  5382.6 1839.15
  5444.7 1835.32  5452.5 1837.79    5553 1841.11  5960.5 1845.61  6076.1 1847.74
  6096.8 1848.41  6269.6  1851.8  6382.8 1851.96    6530 1859.61  6618.5 1861.21
#Mann= 11 ,-1 , 0
  2221.6    .035       0  2751.2     .07       0  4851.1    .035       0
  4967.2     .07       0  4988.6    .035       0  4994.1     .07       0
  5960.5    .035       0  6076.1     .07       0  6096.8    .035       0
  6269.6     .07       0    6530    .035       0
Bank Sta=4967.2,4988.6
XS Rating Curve= 0 ,0
Exp/Cntr=0.3,0.1

Type RM Length L Ch R = 1 ,36481   ,603,603,603
BEGIN DESCRIPTION:
Mapping XS 5b828571
END DESCRIPTION:
XS GIS Cut Line= 4
      1448124.84      6910299.95      1449439.95      6909206.19
      1449935.33      6908143.26      1450876.59      6907101.52
#Sta/Elev= 30
    2111 1853.79  2339.8 1847.78  2612.7 1844.52  2993.4 1839.36  3558.3 1837.84
  3799.1 1835.49  3823.9 1835.66  4154.7 1837.14  4381.7 1837.87  4470.4 1835.45
  4526.7 1838.07  4944.8  1839.8  4997.9 1833.99  5004.6 1836.18  5012.1 1833.12
  5018.8 1834.84  5029.6  1831.6  5030.1  1831.1  5051.3  1831.6  5061.4 1837.75
  5068.7 1838.78  5273.6 1839.07  5337.9 1835.87  5358.8 1838.51  5681.1 1841.97
  5821.4 1843.68  6063.6 1846.41  6169.2 1847.38  6230.7 1848.64  6398.2 1850.78
#Mann= 15 ,-1 , 0
    2111    .035       0  2612.7     .07       0  3558.3    .035       0
  3799.1     .07       0  3823.9     .16       0  4154.7     .07       0
  4381.7    .035       0  4526.7     .07       0  5029.6     .07       0
  5051.3     .07       0  5681.1    .035       0  5821.4     .07       0
  6063.6    .035       0  6169.2     .07       0  6230.7    .035       0
Bank Sta=5029.6,5051.3
XS Rating Curve= 0 ,0
Exp/Cntr=0.3,0.1

Type RM Length L Ch R = 1 ,35878   ,603,603,603
BEGIN DESCRIPTION:
Mapping XS 874a6de2
END DESCRIPTION:
XS GIS Cut Line= 4
       1448107.5       6910382.4      1450146.59      6908717.25
      1450297.31      6908382.84      1450969.02      6907269.38
#Sta/Elev= 30
  1996.3 1854.29  2598.6 1844.07  3137.3 1839.35  3401.5 1838.91  3426.9 1838.52
  3701.2 1835.79  3803.9  1834.8  4011.4 1833.27  4094.6 1831.13  4935.2 1838.31
  5056.5 1835.54  5060.6 1828.97  5061.1 1828.47  5082.3 1828.97  5083.7 1832.45
  5099.2 1836.63  5120.5 1837.26  5178.8 1836.09  5194.3 1832.31  5252.5 1838.07
  5491.9 1838.83  5611.2 1844.11  5676.4 1843.56  5836.1 1845.42  5860.5 1845.93
    6061 1850.64  6078.8 1850.66  6173.5 1850.74    6286 1852.11  6296.1 1851.94
#Mann= 18 ,-1 , 0
  1996.3    .035       0  2598.6     .07       0  3137.3    .035       0
  3401.5     .07       0  3426.9    .035       0  3701.2     .07       0
  3803.9     .16       0  4011.4     .07       0  5060.6     .07       0
  5082.3     .07       0  5611.2    .035       0  5676.4     .07       0
  5836.1    .035       0  5860.5     .07       0    6061    .035       0
  6078.8     .07       0  6173.5    .035       0    6286     .07       0
Bank Sta=5060.6,5082.3
XS Rating Curve= 0 ,0
Exp/Cntr=0.3,0.1

Type RM Length L Ch R = 1 ,35275   ,1182,1182,1182
BEGIN DESCRIPTION:
Mapping XS 8bd4e618
END DESCRIPTION:
XS GIS Cut Line= 3
      1448072.75      6910482.24      1450605.01      6908663.02
      1451429.15      6908137.37
#Sta/Elev= 30
    1882 1855.93  1934.9 1854.68  2303.2 1846.93  2757.9 1841.86  3117.3 1836.77
    3391 1838.94  3566.2 1837.33  3915.3 1832.56  4537.8 1833.94  4938.4 1836.96
  4946.6 1836.36  4961.3 1830.03  4967.5 1833.76  4975.4 1829.37  5018.2 1829.36
  5024.1 1830.73  5028.4 1829.02  5028.9 1828.52  5050.3 1829.02  5054.6 1834.76
    5083 1835.86  5163.8  1836.1  5294.1 1840.33  5539.5 1842.86  5560.6 1844.51
    5597 1843.46  5627.5 1845.37  5727.4 1845.88  5909.3 1853.76  5977.5  1852.3
#Mann= 7 ,-1 , 0
    1882     .07       0  1934.9    .035       0  2757.9     .07       0
  3117.3    .035       0  3566.2     .07       0  5028.4     .07       0
  5050.3     .07       0
Bank Sta=5028.4,5050.3
XS Rating Curve= 0 ,0
Exp/Cntr=0.3,0.1

Type RM Length L Ch R = 1 ,34093   ,451,451,451
BEGIN DESCRIPTION:
Mapping XS 543aaa4a
END DESCRIPTION:
XS GIS Cut Line= 4
      1448064.12      6910616.76      1449409.57      6909657.58
      1450838.98      6909179.72      1451617.66       6909531.3
#Sta/Elev= 30
  1823.3 1854.76  1849.5 1854.85  2993.1 1839.13  3177.4 1834.66    3207 1837.52
    3403 1837.54    3625 1836.93  4082.4 1830.64  4221.9 1832.55  4345.8 1832.51
  4433.8 1832.44  4491.4 1829.72    4536  1832.6  4957.5 1835.12  4972.9 1834.66
  4978.1 1830.33  4989.5 1827.38    4990 1826.88  5011.4 1827.38  5067.7 1831.41
  5090.8 1828.46    5143 1836.61  5163.4 1833.28  5183.3 1831.31  5188.8 1833.45
  5288.5 1837.29  5372.7 1839.65  5519.2 1840.93  5685.8 1842.57  5837.2 1841.25
#Mann= 16 ,-1 , 0
  1823.3     .07       0  1849.5    .035       0  2993.1     .07       0
    3403    .035       0    3625     .07       0  4221.9     .16       0
  4345.8     .07       0  4433.8     .16       0  4491.4     .07       0
  4989.5     .07       0  5011.4     .07       0  5163.4    .035       0
  5288.5     .07       0  5372.7    .035       0  5519.2     .07       0
  5685.8    .035       0
Bank Sta=4989.5,5011.4
XS Rating Curve= 0 ,0
Exp/Cntr=0.3,0.1

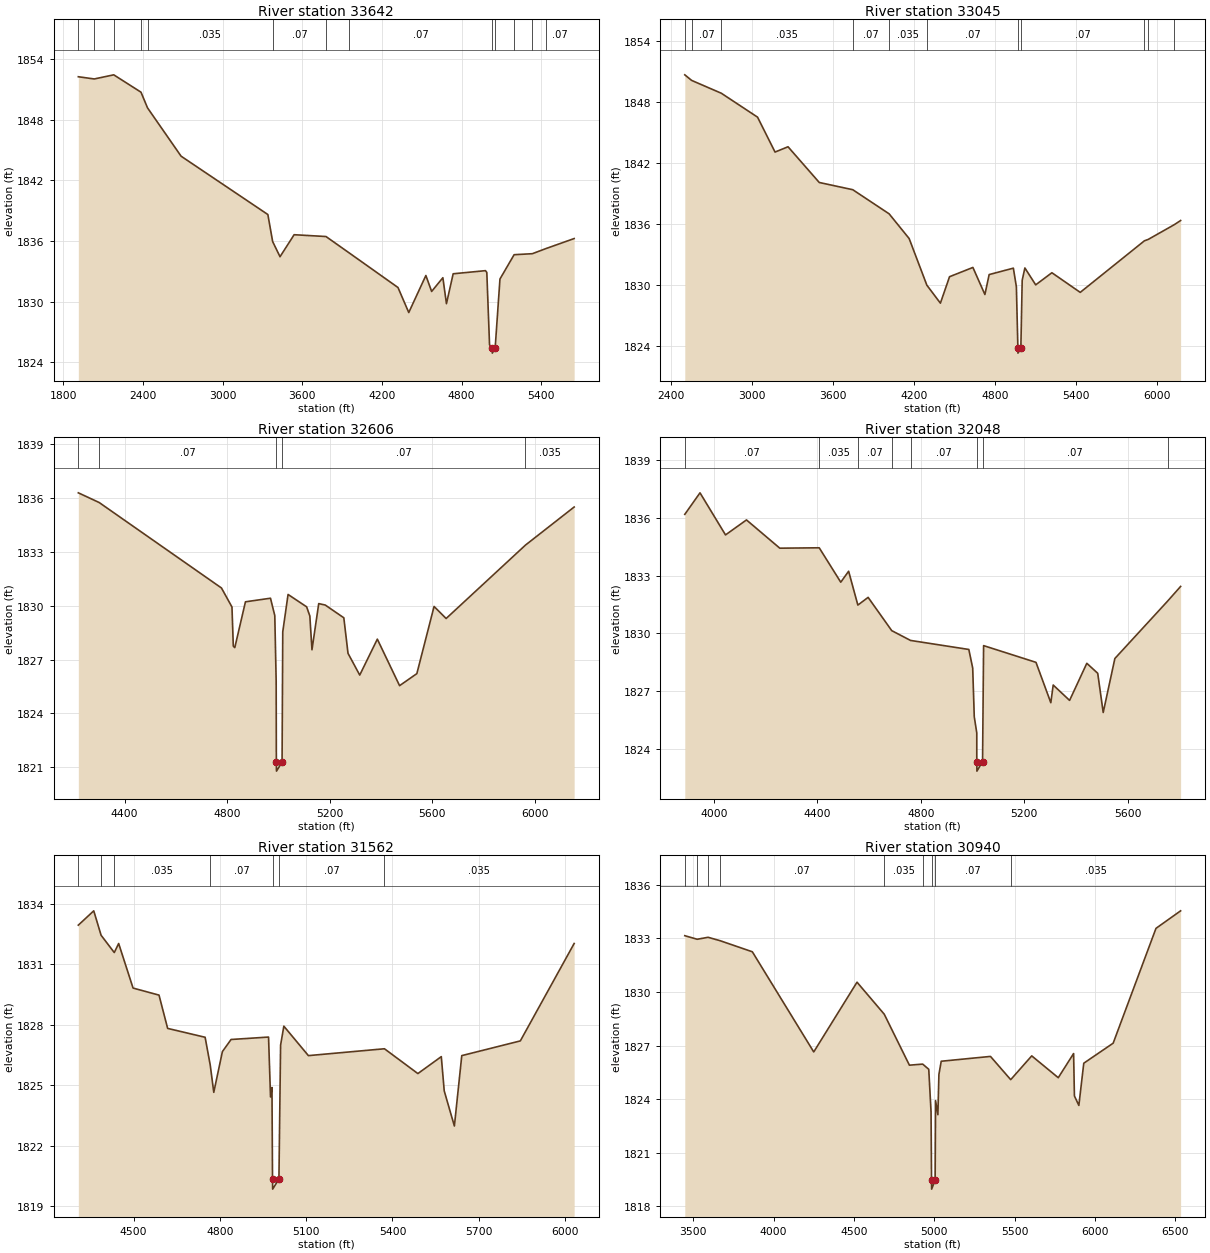
Type RM Length L Ch R = 1 ,33642   ,597,597,597
BEGIN DESCRIPTION:
Mapping XS 7b27995b
END DESCRIPTION:
XS GIS Cut Line= 4
      1448072.78      6910855.48      1449327.11      6909800.81
      1450755.64      6909567.74      1451375.42      6909752.63
#Sta/Elev= 30
    1914 1852.27    2034 1852.05  2180.6 1852.46  2385.8 1850.74  2434.8 1849.19
  2687.7  1844.4  3340.9 1838.62  3377.1 1835.94  3432.5 1834.44  3538.7 1836.62
  3778.7 1836.44  3955.2  1834.8  4320.7 1831.39  4401.8 1828.91  4530.6 1832.58
    4574    1831  4658.6 1832.36  4685.5 1829.79  4736.1 1832.75  4979.3 1833.06
  4989.4 1832.88    5010 1825.71  5030.3 1825.39  5030.8 1824.89  5052.2 1825.39
  5088.4 1832.23  5194.9 1834.64  5332.4 1834.74  5435.1 1835.25    5647 1836.24
#Mann= 13 ,-1 , 0
    1914    .035       0    2034     .07       0  2180.6    .035       0
  2385.8     .07       0  2434.8    .035       0  3377.1     .07       0
  3778.7    .035       0  3955.2     .07       0  5030.3     .07       0
  5052.2     .07       0  5194.9     .07       0  5332.4    .035       0
  5435.1     .07       0
Bank Sta=5030.3,5052.2
XS Rating Curve= 0 ,0
Exp/Cntr=0.3,0.1

Type RM Length L Ch R = 1 ,33045   ,439,439,439
BEGIN DESCRIPTION:
Mapping XS 9e95816b
END DESCRIPTION:
XS GIS Cut Line= 3
      1448202.99      6910977.01      1450443.14      6909893.26
      1451628.78      6909921.25
#Sta/Elev= 30
  2499.2 1850.69  2550.1 1850.14  2769.9 1848.88  3038.4 1846.53    3168  1843.1
  3264.3 1843.62  3495.7 1840.11    3744  1839.4  4013.4 1837.03  4161.9  1834.6
    4293 1830.02  4393.4 1828.25  4461.2 1830.85  4634.3 1831.76  4723.2  1829.1
  4754.8 1831.06  4934.2 1831.69  4956.5 1829.86  4967.7 1823.84  4968.2 1823.34
  4989.7 1823.84  4999.6  1830.5  5019.6 1831.71  5099.6 1830.05  5219.7 1831.24
  5429.7 1829.31  5905.5 1834.38  5934.3 1834.52  6123.6 1835.94  6173.7 1836.37
#Mann= 11 ,-1 , 0
  2499.2    .035       0  2550.1     .07       0  2769.9    .035       0
    3744     .07       0  4013.4    .035       0    4293     .07       0
  4967.7     .07       0  4989.7     .07       0  5905.5    .035       0
  5934.3     .07       0  6123.6    .035       0
Bank Sta=4967.7,4989.7
XS Rating Curve= 0 ,0
Exp/Cntr=0.3,0.1

Type RM Length L Ch R = 1 ,32606   ,558,558,558
BEGIN DESCRIPTION:
Mapping XS ba10b23c
END DESCRIPTION:
XS GIS Cut Line= 3
       1449758.2      6910500.04      1450500.43      6910286.49
      1451622.65       6909982.5
#Sta/Elev= 30
  4219.5 1836.29  4300.9 1835.75  4778.1 1830.99  4819.1 1829.93  4824.3 1827.75
  4830.1 1827.67  4871.7 1830.22  4969.4 1830.42  4986.2 1829.45  4991.6 1825.79
  4992.3 1821.29  4992.8 1820.79  5014.6 1821.29  5017.3 1828.55    5038 1830.63
  5110.5 1829.94    5123 1829.43  5131.3 1827.55  5157.7 1830.12  5183.1 1830.04
  5255.6 1829.33    5272 1827.35  5317.7 1826.14  5386.4 1828.14  5473.2 1825.55
  5540.6 1826.22  5607.8 1829.96  5654.9 1829.29  5964.6 1833.38  6154.5  1835.5
#Mann= 5 ,-1 , 0
  4219.5    .035       0  4300.9     .07       0  4992.3     .07       0
  5014.6     .07       0  5964.6    .035       0
Bank Sta=4992.3,5014.6
XS Rating Curve= 0 ,0
Exp/Cntr=0.3,0.1

Type RM Length L Ch R = 1 ,32048   ,486,486,486
BEGIN DESCRIPTION:
Mapping XS 350e3a90
END DESCRIPTION:
XS GIS Cut Line= 4
      1449789.54        6910724.       1450482.2      6910835.97
      1450836.37      6910596.39      1451498.59      6910168.63
#Sta/Elev= 30
    3887 1836.19  3945.8 1837.31  4044.5 1835.12  4125.5  1835.9  4254.4 1834.43
  4406.9 1834.45  4490.2 1832.66  4520.6 1833.23  4556.3 1831.47    4596 1831.87
  4687.3 1830.14    4760 1829.63  4985.5 1829.16  5000.5 1828.19  5006.5 1825.66
  5016.2 1824.82  5016.3 1823.33  5016.8 1822.83  5038.6 1823.33  5042.6 1829.36
  5245.2 1828.49  5302.6 1826.39  5311.8 1827.31  5375.2 1826.51  5441.8 1828.44
    5484 1827.92  5505.2 1825.88  5550.3 1828.69  5753.9 1831.67  5804.6 1832.44
#Mann= 8 ,-1 , 0
    3887     .07       0  4406.9    .035       0  4556.3     .07       0
  4687.3    .035       0    4760     .07       0  5016.3     .07       0
  5038.6     .07       0  5753.9    .035       0
Bank Sta=5016.3,5038.6
XS Rating Curve= 0 ,0
Exp/Cntr=0.3,0.1

Type RM Length L Ch R = 1 ,31562   ,622,622,622
BEGIN DESCRIPTION:
Mapping XS c27e9f28
END DESCRIPTION:
XS GIS Cut Line= 4
      1450305.11      6910989.61      1450987.41      6911033.89
      1451398.87      6910838.57      1451507.25       6910264.1
#Sta/Elev= 30
  4307.9 1832.95  4361.5 1833.66    4387 1832.45  4432.9 1831.59  4448.1 1832.04
  4498.2 1829.83  4588.4 1829.48  4618.4 1827.83  4748.7 1827.39  4766.5 1826.01
  4778.8 1824.66  4808.8 1826.68  4838.9 1827.28  4969.2  1827.4  4976.1 1824.43
  4981.1  1824.9    4983 1820.36  4983.5 1819.86  5005.3 1820.36  5011.1    1827
  5022.4 1827.94  5107.7 1826.48  5372.2 1826.82  5488.4 1825.59  5569.8 1826.43
    5580 1824.73  5615.3 1822.99    5641 1826.48  5844.6 1827.21  6031.7 1832.04
#Mann= 7 ,-1 , 0
  4307.9    .035       0    4387     .07       0  4432.9    .035       0
  4766.5     .07       0    4983     .07       0  5005.3     .07       0
  5372.2    .035       0
Bank Sta=4983,5005.3
XS Rating Curve= 0 ,0
Exp/Cntr=0.3,0.1

Type RM Length L Ch R = 1 ,30940   ,401,401,401
BEGIN DESCRIPTION:
Mapping XS d94777e5
END DESCRIPTION:
XS GIS Cut Line= 4
      1449827.53      6912503.74      1450987.41      6911468.78
      1451429.12      6910906.49      1451594.05      6910107.88
#Sta/Elev= 30
  3447.2 1833.14  3524.3 1832.94  3592.1 1833.05  3666.9 1832.86  3867.4 1832.24
  4249.5 1826.64  4518.7 1830.54  4688.2 1828.75  4844.7  1825.9  4927.3 1825.96
  4965.1 1825.67  4979.4 1823.29  4982.4 1819.47  4982.9 1818.97  5004.8 1819.47
  5007.5 1823.92  5021.9 1823.13  5028.3 1825.38  5042.7 1826.12  5349.1 1826.39
    5475 1825.09  5605.8 1826.42  5770.9  1825.2  5866.3 1826.55  5871.4 1824.18
    5899 1823.65  5929.6 1826.01  6112.5 1827.13  6378.9 1833.55  6532.2 1834.53
#Mann= 9 ,-1 , 0
  3447.2    .035       0  3524.3     .07       0  3592.1    .035       0
  3666.9     .07       0  4688.2    .035       0  4927.3     .07       0
  4982.4     .07       0  5004.8     .07       0    5475    .035       0
Bank Sta=4982.4,5004.8
XS Rating Curve= 0 ,0
Exp/Cntr=0.3,0.1

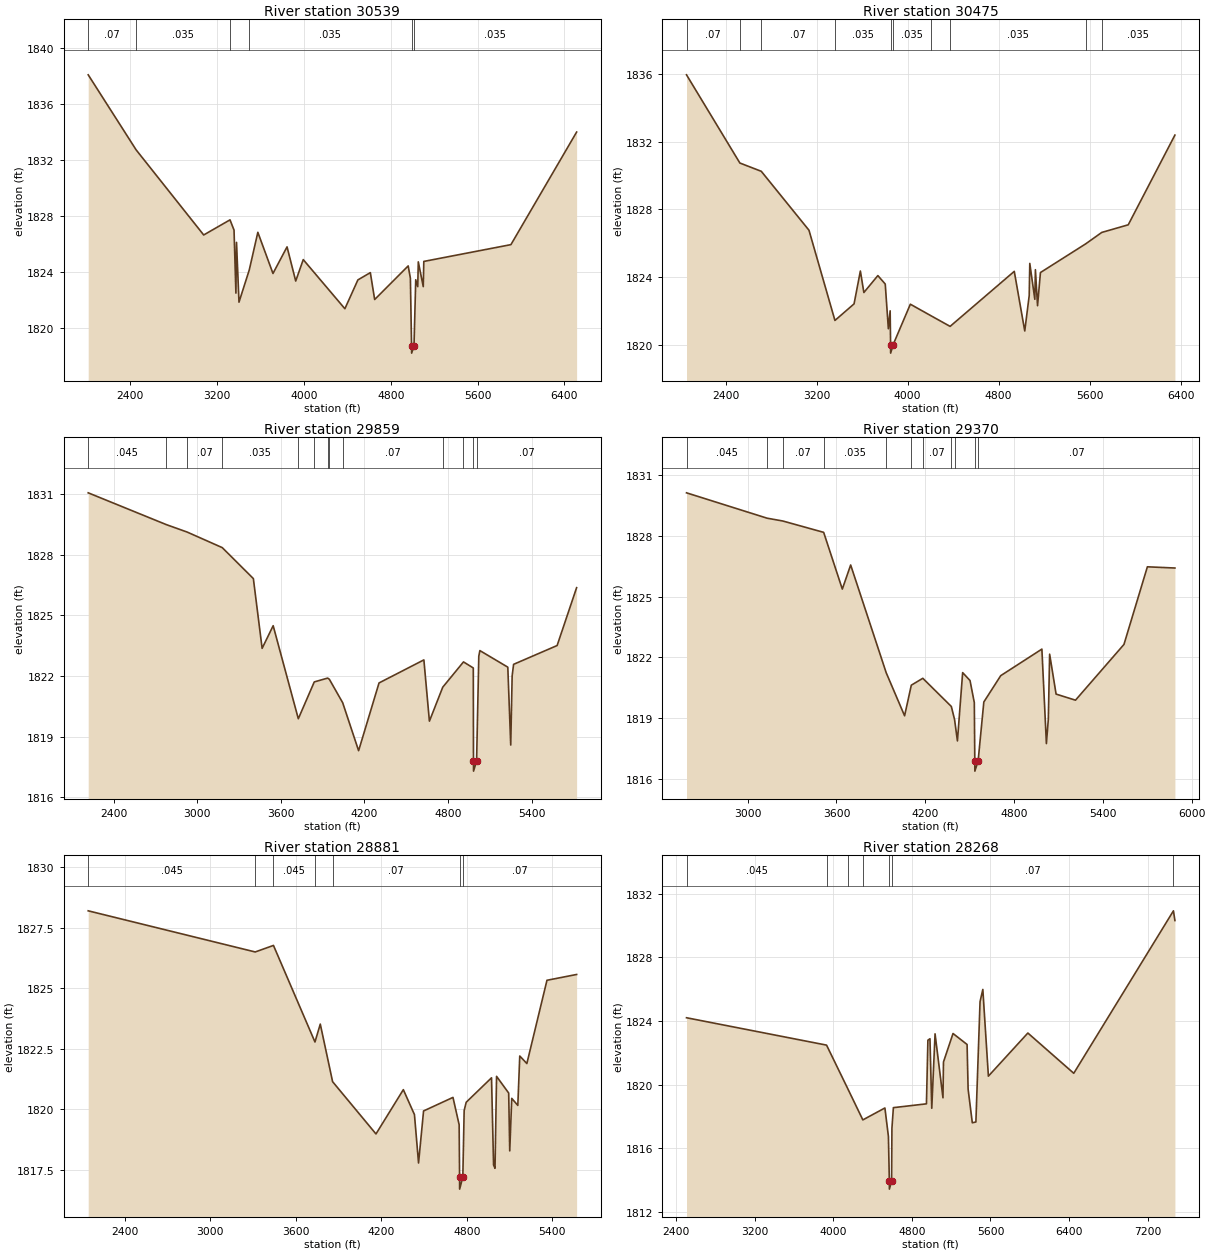
Type RM Length L Ch R = 1 ,30539   ,64,64,64
BEGIN DESCRIPTION:
Mapping XS 6832e713
END DESCRIPTION:
XS GIS Cut Line= 4
      1449613.55      6913733.11      1450932.45      6913114.29
      1451325.95      6911656.28      1451628.76      6910155.66
#Sta/Elev= 30
  2014.3 1838.06  2455.6  1832.7  3077.9 1826.62  3320.2  1827.7  3357.2 1826.97
  3374.5 1822.47  3380.1 1826.09  3402.9 1821.82  3497.5 1824.12  3576.5 1826.81
  3715.9 1823.87  3845.5 1825.77  3925.3 1823.33  3994.7 1824.86  4378.2 1821.35
  4497.9 1823.41  4612.5 1823.93  4652.4 1822.01  4961.2 1824.41  4981.3 1823.53
  4992.2 1818.68  4992.7 1818.18  5014.6 1818.68  5030.6 1823.42  5049.1 1822.93
  5054.2  1824.7  5099.9 1822.93    5105 1824.73  5907.3 1825.93  6512.2 1833.97
#Mann= 6 ,-1 , 0
  2014.3     .07       0  2455.6    .035       0  3320.2     .07       0
  3497.5    .035       0  4992.2    .035       0  5014.6    .035       0
Bank Sta=4992.2,5014.6
XS Rating Curve= 0 ,0
Exp/Cntr=0.3,0.1

Type RM Length L Ch R = 1 ,30475   ,616,616,616
BEGIN DESCRIPTION:
Mapping XS 5e0a81b5
END DESCRIPTION:
XS GIS Cut Line= 4
      1449778.54      6913785.16      1451046.44       6913161.3
      1451383.25      6911674.51      1451667.83      6910346.59
#Sta/Elev= 30
  2055.2 1835.95  2524.5 1830.74    2713 1830.25  3132.3 1826.77  3360.7 1821.44
  3528.9 1822.42  3584.4 1824.36  3615.1 1823.09  3738.2 1824.09  3803.1 1823.59
  3830.5 1820.95  3846.2 1822.01  3850.1 1820.01  3850.6 1819.51  3872.5 1820.01
  4023.9  1822.4  4207.5 1821.71  4373.6 1821.09  4937.9 1824.34  5030.1 1820.82
  5069.3 1822.91  5074.4 1824.81  5118.7 1822.69  5123.8 1824.44  5142.6 1822.31
  5168.1 1824.27    5565 1825.96  5707.5 1826.64  5940.3 1827.09  6350.8 1832.39
#Mann= 10 ,-1 , 0
  2055.2     .07       0  2524.5    .035       0    2713     .07       0
  3360.7    .035       0  3850.1    .035       0  3872.5    .035       0
  4207.5     .07       0  4373.6    .035       0    5565     .07       0
  5707.5    .035       0
Bank Sta=3850.1,3872.5
XS Rating Curve= 0 ,0
Exp/Cntr=0.3,0.1

Type RM Length L Ch R = 1 ,29859   ,489,489,489
BEGIN DESCRIPTION:
Mapping XS 9fa232e0
END DESCRIPTION:
XS GIS Cut Line= 4
      1450199.48      6914470.98      1451106.62      6913246.99
      1451654.08      6912112.01       1452349.4      6911908.88
#Sta/Elev= 30
  2215.9 1831.06  2776.2 1829.49  2926.5 1829.12  3178.9 1828.35  3402.1 1826.82
  3465.1 1823.37  3544.4 1824.49    3725 1819.89  3839.6 1821.71  3935.5  1821.9
  3948.1 1821.84  4043.8 1820.68  4158.1 1818.31  4304.8 1821.66  4626.9  1822.8
  4666.6 1819.77  4762.4 1821.45  4911.4  1822.7  4981.8  1822.4  4983.1  1817.8
  4983.6  1817.3  5005.5  1817.8  5021.3 1822.98  5029.1 1823.26  5229.7 1822.44
  5250.7 1818.59  5260.9 1822.01  5271.3 1822.58  5583.9 1823.51  5723.9 1826.37
#Mann= 13 ,-1 , 0
  2215.9    .045       0  2776.2    .035       0  2926.5     .07       0
  3178.9    .035       0    3725     .07       0  3839.6    .035       0
  3935.5     .07       0  3948.1    .035       0  4043.8     .07       0
  4762.4    .035       0  4911.4     .07       0  4983.1     .07       0
  5005.5     .07       0
Bank Sta=4983.1,5005.5
XS Rating Curve= 0 ,0
Exp/Cntr=0.3,0.1

Type RM Length L Ch R = 1 ,29370   ,489,489,489
BEGIN DESCRIPTION:
Mapping XS 375e84b9
END DESCRIPTION:
XS GIS Cut Line= 4
      1450307.99      6914462.29      1451054.54       6913442.3
      1451753.04      6912536.49      1452570.34      6912178.31
#Sta/Elev= 30
  2586.7 1830.12  3130.5 1828.87  3237.2 1828.73  3513.5 1828.17  3639.5 1825.37
  3695.9 1826.56  3936.2 1821.24  4060.3 1819.12  4105.7 1820.63  4183.4 1820.97
  4376.1 1819.58  4397.9 1818.94  4417.3 1817.88  4452.6 1821.25  4502.4 1820.86
  4531.4 1819.77  4534.7 1816.89  4535.2 1816.39  4557.1 1816.89  4595.7  1819.8
  4709.9  1821.1    4988 1822.41  5018.5 1817.75  5031.5 1818.95  5040.4 1822.16
    5084 1820.19  5215.1 1819.89  5542.6 1822.64  5700.9 1826.47  5886.9 1826.41
#Mann= 11 ,-1 , 0
  2586.7    .045       0  3130.5    .035       0  3237.2     .07       0
  3513.5    .035       0  3936.2     .07       0  4105.7    .035       0
  4183.4     .07       0  4376.1    .035       0  4397.9     .07       0
  4534.7     .07       0  4557.1     .07       0
Bank Sta=4534.7,4557.1
XS Rating Curve= 0 ,0
Exp/Cntr=0.3,0.1

Type RM Length L Ch R = 1 ,28881   ,613,613,613
BEGIN DESCRIPTION:
Mapping XS 176309da
END DESCRIPTION:
XS GIS Cut Line= 3
      1450312.38      6915065.53      1452094.18      6912838.57
      1452518.65      6912447.96
#Sta/Elev= 30
  2142.1 1828.19  3314.6 1826.49  3442.7 1826.76  3734.1 1822.77  3771.4 1823.51
  3857.9 1821.13  4162.4 1818.97  4354.5  1820.8  4432.5 1819.77  4461.3 1817.77
  4496.5 1819.92    4703 1820.48  4746.3 1819.35  4749.3 1817.19  4749.8 1816.69
  4772.1 1817.19  4781.5 1819.94  4795.9 1820.28  4973.6 1821.29    4988 1817.69
  4998.1 1817.55    5009 1821.35  5094.1 1820.66  5101.5 1818.27  5115.6 1820.44
  5158.2 1820.15  5171.9 1822.19  5221.7 1821.88  5362.9 1825.32    5571 1825.56
#Mann= 7 ,-1 , 0
  2142.1    .045       0  3314.6    .035       0  3442.7    .045       0
  3734.1    .035       0  3857.9     .07       0  4749.3     .07       0
  4772.1     .07       0
Bank Sta=4749.3,4772.1
XS Rating Curve= 0 ,0
Exp/Cntr=0.3,0.1

Type RM Length L Ch R = 1 ,28268   ,37,37,37
BEGIN DESCRIPTION:
Mapping XS fc34ebb1
END DESCRIPTION:
XS GIS Cut Line= 6
      1450967.73      6915321.64      1452404.08      6913278.68
      1452719.18      6913312.53      1452786.89      6913296.91
      1453124.56      6912938.78      1453380.84      6911372.52
#Sta/Elev= 30
  2508.4  1824.2    3933 1822.48  4146.6 1819.77  4302.1 1817.78  4526.5 1818.53
  4562.2 1816.74  4571.7 1813.93  4572.2 1813.43  4594.5 1813.93  4597.9 1817.25
  4612.7 1818.55    4949 1818.79  4963.8 1822.79  4984.8 1822.88  5003.1 1818.51
  5036.7 1823.19  5117.2 1819.17  5122.3 1821.42  5219.4 1823.21  5362.4 1822.52
  5372.9 1819.71  5415.6  1817.6    5452 1817.65  5494.3 1825.21  5522.6 1825.98
  5579.2 1820.53  5980.7 1823.24  6447.5 1820.71  7461.6 1830.92  7476.5 1830.31
#Mann= 7 ,-1 , 0
  2508.4    .045       0    3933     .07       0  4146.6    .035       0
  4302.1     .07       0  4571.7     .07       0  4594.5     .07       0
  7461.6    .035       0
Bank Sta=4571.7,4594.5
XS Rating Curve= 0 ,0
Exp/Cntr=0.3,0.1

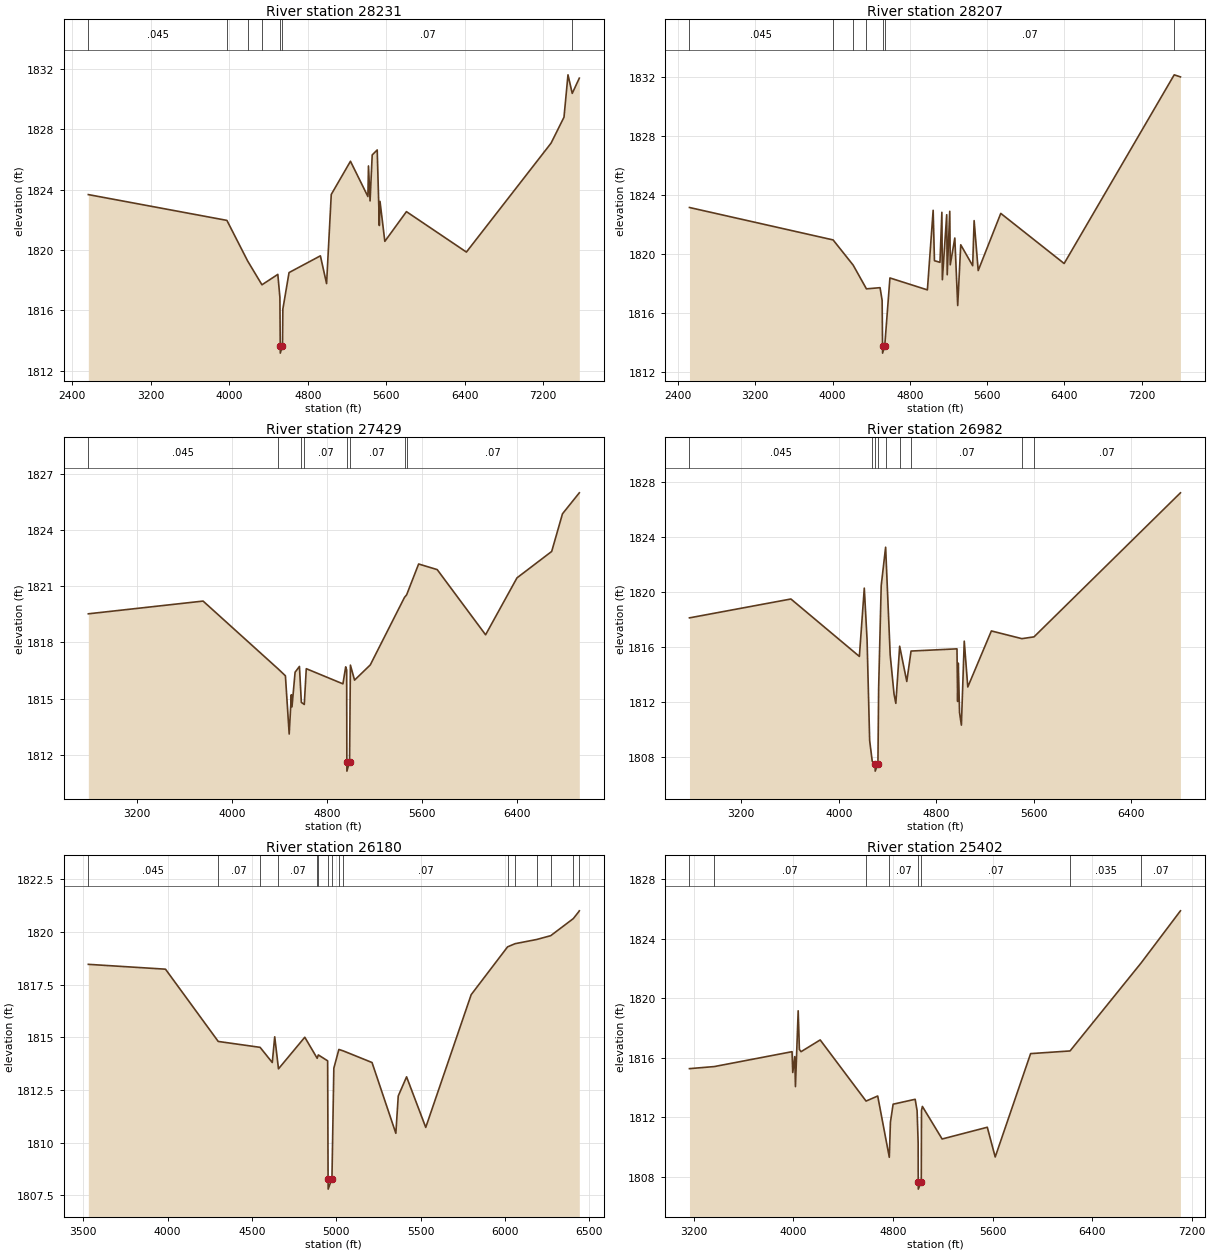
Type RM Length L Ch R = 1 ,28231   ,24,24,24
BEGIN DESCRIPTION:
Mapping XS db58fbbb
END DESCRIPTION:
XS GIS Cut Line= 6
      1451089.27      6915347.66      1452432.73      6913299.51
      1452807.73      6913322.95      1452859.81      6913226.59
      1453173.89       6912952.7      1453463.39      6911324.26
#Sta/Elev= 30
  2562.2 1823.68  3975.4 1821.97  4186.8 1819.28  4332.9  1817.7  4494.7 1818.39
  4515.8 1816.88  4519.5 1813.67    4520 1813.17  4542.3 1813.67    4546 1816.09
  4609.2 1818.51  4928.8 1819.62    4992 1817.78  5039.7 1823.69  5235.6 1825.89
  5413.5 1823.55  5419.2 1825.58  5435.4 1823.26  5457.3 1826.31  5508.3 1826.64
  5530.1 1821.63  5536.8 1823.23  5586.1 1820.58  5806.4 1822.55    6418 1819.87
  7281.3 1827.09  7413.3 1828.81    7454 1831.62  7497.4 1830.39  7569.5  1831.4
#Mann= 7 ,-1 , 0
  2562.2    .045       0  3975.4     .07       0  4186.8    .035       0
  4332.9     .07       0  4519.5     .07       0  4542.3     .07       0
  7497.4    .035       0
Bank Sta=4519.5,4542.3
XS Rating Curve= 0 ,0
Exp/Cntr=0.3,0.1

Type RM Length L Ch R = 1 ,28207   ,778,778,778
BEGIN DESCRIPTION:
Mapping XS f75a9ce8
END DESCRIPTION:
XS GIS Cut Line= 6
       1451180.4      6915456.19      1452435.33      6913325.55
       1452669.7      6913367.22      1452828.56      6913341.18
      1453224.49      6912931.55      1453663.04      6911354.63
#Sta/Elev= 30
  2519.1 1823.15  4006.2 1820.95  4213.9 1819.24  4351.3 1817.63  4492.3 1817.71
  4513.7 1816.85    4518 1813.77  4518.5 1813.27  4540.8 1813.77  4594.4 1818.37
  4982.3 1817.56  5041.9 1822.96  5055.4 1819.54  5112.4 1819.43  5132.2 1822.82
  5137.2 1818.25  5182.2 1822.66  5187.5 1818.59  5213.8 1822.89  5219.1 1819.26
  5266.2 1821.08  5296.2  1816.5  5327.5 1820.62  5451.1  1819.2  5466.1 1822.26
  5508.4 1818.87    5742 1822.75  6398.1 1819.35  7537.6 1832.15  7602.1 1832.01
#Mann= 7 ,-1 , 0
  2519.1    .045       0  4006.2     .07       0  4213.9    .035       0
  4351.3     .07       0    4518     .07       0  4540.8     .07       0
  7537.6    .035       0
Bank Sta=4518,4540.8
XS Rating Curve= 0 ,0
Exp/Cntr=0.3,0.1

Type RM Length L Ch R = 1 ,27429   ,447,447,447
BEGIN DESCRIPTION:
Mapping XS 174277de
END DESCRIPTION:
XS GIS Cut Line= 3
      1452239.42      6915777.41      1452950.03      6913687.94
      1453662.76      6911902.22
#Sta/Elev= 30
    2793 1819.53  3758.2 1820.21  4390.9 1816.58  4450.7 1816.22  4482.4 1813.11
  4500.6 1815.21  4505.9 1814.56    4532 1816.41  4568.6 1816.72  4584.7  1814.8
  4609.4 1814.69  4626.1  1816.6  4934.5 1815.79  4957.7  1816.7  4965.9 1816.53
  4967.4 1811.63  4967.9 1811.13  4990.2 1811.63  4997.3 1816.79  5032.3 1815.99
  5164.3  1816.8  5452.5 1820.41    5470 1820.54  5571.2 1822.19  5727.5 1821.89
  6134.4 1818.41  6398.5 1821.45  6690.4 1822.86  6781.1 1824.87  6922.7 1825.99
#Mann= 8 ,-1 , 0
    2793    .045       0  4390.9     .07       0  4584.7    .035       0
  4609.4     .07       0  4967.4     .07       0  4990.2     .07       0
  5452.5    .035       0    5470     .07       0
Bank Sta=4967.4,4990.2
XS Rating Curve= 0 ,0
Exp/Cntr=0.3,0.1

Type RM Length L Ch R = 1 ,26982   ,802,802,802
BEGIN DESCRIPTION:
Mapping XS 30b86287
END DESCRIPTION:
XS GIS Cut Line= 3
      1452647.43      6915851.13      1453346.79      6913742.22
      1454062.37      6912083.76
#Sta/Elev= 30
  2775.1  1818.1  3607.4 1819.47  4169.1  1815.3  4209.4 1820.26  4232.3 1816.49
  4253.4 1809.19  4274.6 1807.69  4298.4 1807.47  4298.9 1806.97  4321.2 1807.47
  4327.1 1812.98  4348.2 1820.44  4384.4 1823.23  4421.9 1815.41  4453.5 1812.56
  4468.2 1811.89  4499.6 1816.04    4558 1813.48    4593 1815.69  4969.8 1815.85
  4975.2 1812.03  4980.5 1814.81  4990.9 1811.22    5006 1810.31  5029.5 1816.41
  5058.5 1813.08    5252 1817.15  5502.2 1816.59  5601.8 1816.72  6803.2 1827.18
#Mann= 9 ,-1 , 0
  2775.1    .045       0  4274.6     .07       0  4298.4     .07       0
  4321.2     .07       0  4384.4    .045       0  4499.6    .035       0
    4593     .07       0  5502.2    .035       0  5601.8     .07       0
Bank Sta=4298.4,4321.2
XS Rating Curve= 0 ,0
Exp/Cntr=0.3,0.1

Type RM Length L Ch R = 1 ,26180   ,778,778,778
BEGIN DESCRIPTION:
Mapping XS 858b2c76
END DESCRIPTION:
XS GIS Cut Line= 3
       1453007.8      6915191.84      1453905.41      6914027.83
      1454860.97      6912948.16
#Sta/Elev= 30
  3530.1 1818.47  3987.7 1818.24  4300.4 1814.81  4548.7 1814.53  4620.9 1813.81
  4635.4 1815.03  4657.8 1813.51  4813.8 1815.01  4887.3 1814.01    4894 1814.17
  4949.3 1813.89  4951.9  1808.3  4952.4  1807.8  4974.8  1808.3    4986 1813.54
  5015.9 1814.43  5042.4 1814.36  5212.5 1813.81  5353.8 1810.45    5368 1812.22
  5417.4 1813.13  5531.1 1810.73  5800.5 1817.03  6016.4  1819.3  6060.8 1819.45
  6189.1 1819.65  6272.1 1819.83  6406.1 1820.64  6438.7 1820.97  6441.8 1821.01
#Mann= 16 ,-1 , 0
  3530.1    .045       0  4300.4     .07       0  4548.7    .035       0
  4657.8     .07       0  4887.3    .035       0    4894     .07       0
  4951.9     .07       0  4974.8     .07       0  5015.9    .035       0
  5042.4     .07       0  6016.4    .035       0  6060.8     .07       0
  6189.1    .035       0  6272.1     .07       0  6406.1    .035       0
  6438.7     .07       0
Bank Sta=4951.9,4974.8
XS Rating Curve= 0 ,0
Exp/Cntr=0.3,0.1

Type RM Length L Ch R = 1 ,25402   ,610,610,610
BEGIN DESCRIPTION:
Mapping XS 71fc5df2
END DESCRIPTION:
XS GIS Cut Line= 3
      1453380.19      6916066.85       1454292.1      6914468.78
       1455421.9      6912691.78
#Sta/Elev= 30
  3164.1 1815.28  3363.9 1815.42  3988.5 1816.42  3994.2 1815.02  4010.1 1816.09
  4015.8 1814.07  4037.8 1819.17  4047.5 1816.57  4060.8 1816.42  4214.6 1817.21
  4583.3  1813.1  4676.9 1813.44  4770.1 1809.32  4779.1 1811.68  4800.7 1812.89
  4977.9 1813.22  4993.4 1812.46  5001.9  1810.3  5002.6 1807.68  5003.1 1807.18
    5027 1807.68  5028.7 1812.47    5036 1812.74  5194.6 1810.55  5557.6 1811.34
  5621.2 1809.34  5905.6 1816.29  6222.6 1816.47  6794.1 1822.39  7109.8 1825.89
#Mann= 8 ,-1 , 0
  3164.1    .035       0  3363.9     .07       0  4583.3    .035       0
  4770.1     .07       0  5002.6     .07       0    5027     .07       0
  6222.6    .035       0  6794.1     .07       0
Bank Sta=5002.6,5027
XS Rating Curve= 0 ,0
Exp/Cntr=0.3,0.1