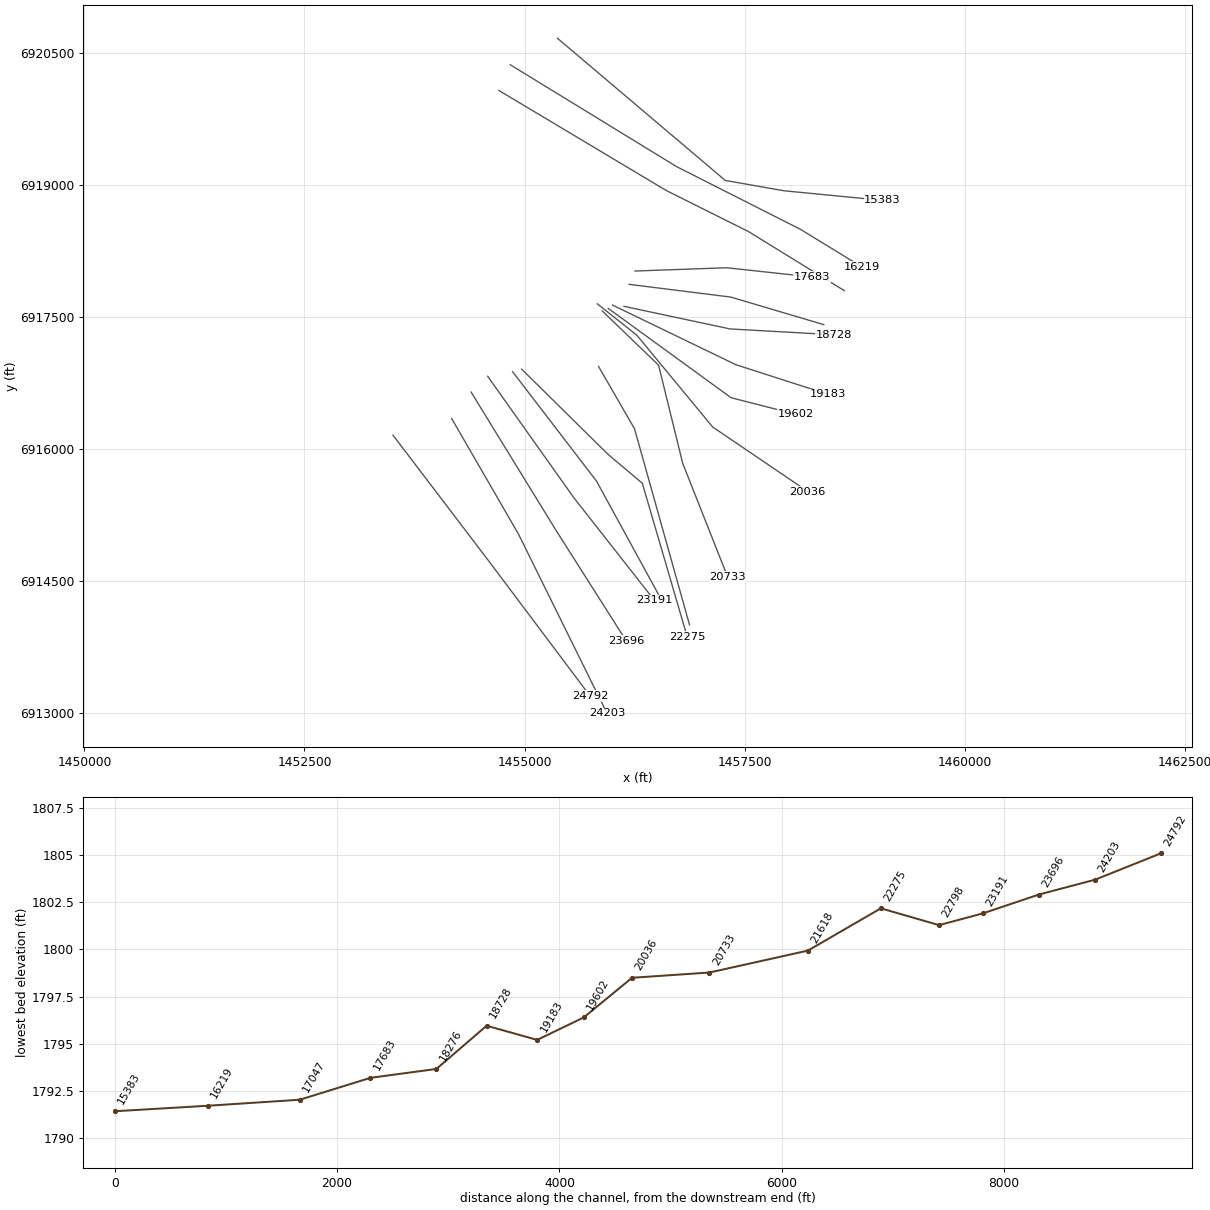
HEC-RAS study Raven Creek.prj: Raven Creek Base Level Engineering

--- Raven Creek.g01 (geometry) --- (continued)

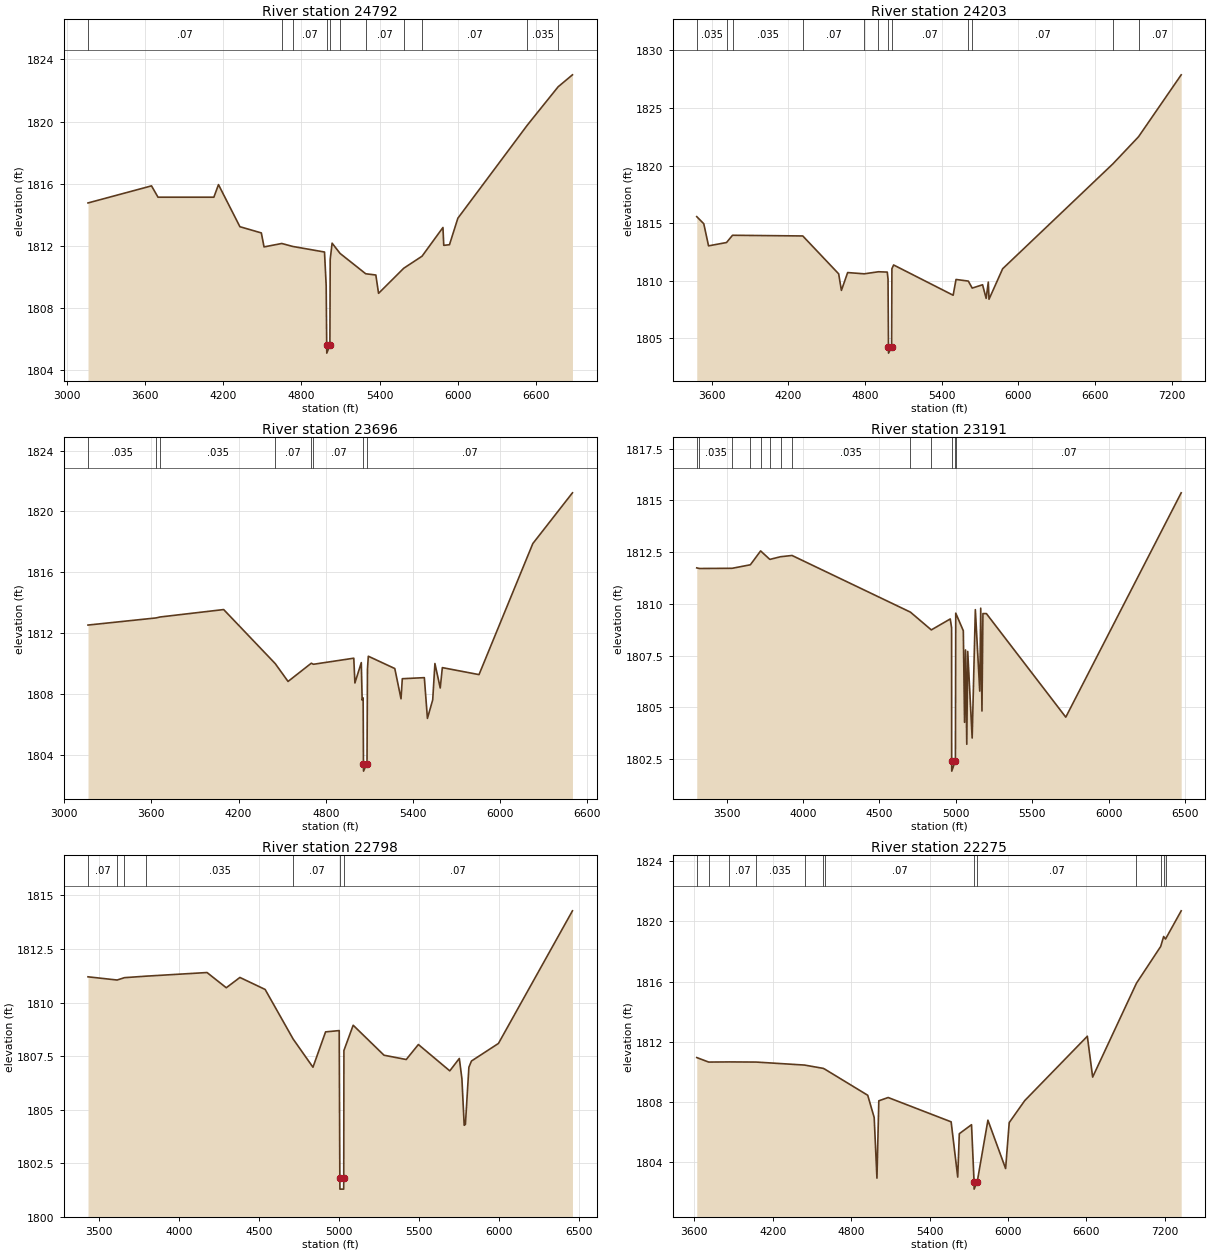
Type RM Length L Ch R = 1 ,24792   ,589,589,589
BEGIN DESCRIPTION:
Mapping XS f783b950
END DESCRIPTION:
XS GIS Cut Line= 3
      1453505.21      6916160.56      1454612.41      6914705.76
      1455744.78      6913197.04
#Sta/Elev= 30
    3164 1814.76  3650.9 1815.86  3700.8 1815.13  4129.1 1815.13  4164.4 1815.94
  4328.7 1813.23  4492.9 1812.83  4513.8 1811.93  4649.9 1812.15  4733.3 1811.96
  4977.4  1811.6  4990.2 1809.45  4994.3 1805.59  4994.8 1805.09  5018.7 1805.59
  5021.1 1811.13  5035.7 1812.17  5096.8 1811.51  5293.4  1810.2    5371 1810.12
  5391.9 1808.94  5585.6 1810.56  5725.2 1811.33  5885.6 1813.18  5891.8 1812.03
  5935.6 1812.07  6000.1 1813.78  6533.4 1819.78  6768.9 1822.24  6878.6 1823.01
#Mann= 11 ,-1 , 0
    3164     .07       0  4649.9    .035       0  4733.3     .07       0
  4994.3     .07       0  5018.7     .07       0  5096.8    .035       0
  5293.4     .07       0  5585.6    .035       0  5725.2     .07       0
  6533.4    .035       0  6768.9     .07       0
Bank Sta=4994.3,5018.7
XS Rating Curve= 0 ,0
Exp/Cntr=0.3,0.1

Type RM Length L Ch R = 1 ,24203   ,507,507,507
BEGIN DESCRIPTION:
Mapping XS 46451dd0
END DESCRIPTION:
XS GIS Cut Line= 3
      1454171.97      6916349.72      1454932.73      6915033.89
      1455937.52      6912999.08
#Sta/Elev= 30
  3484.6 1815.56  3539.6 1814.94  3576.9 1813.02  3717.6 1813.31  3764.4 1813.94
    4314 1813.88  4594.6 1810.59  4616.1 1809.15    4665  1810.7  4794.5 1810.59
  4905.9 1810.77    4975 1810.74  4980.8 1810.13  4984.3  1804.2  4984.8  1803.7
  5008.7  1804.2  5011.1 1811.03  5024.4 1811.36  5490.2 1808.73  5512.6  1810.1
  5608.8 1809.96  5639.3 1809.35  5720.2 1809.64  5748.2 1808.46  5765.1 1809.87
  5770.7 1808.38  5877.3 1811.03  6740.2 1820.15  6940.2  1822.5  7273.9 1827.88
#Mann= 12 ,-1 , 0
  3484.6    .035       0  3717.6     .07       0  3764.4    .035       0
    4314     .07       0  4794.5    .035       0  4905.9     .07       0
  4984.3     .07       0  5008.7     .07       0  5608.8    .035       0
  5639.3     .07       0  6740.2    .035       0  6940.2     .07       0
Bank Sta=4984.3,5008.7
XS Rating Curve= 0 ,0
Exp/Cntr=0.3,0.1

Type RM Length L Ch R = 1 ,23696   ,505,505,505
BEGIN DESCRIPTION:
Mapping XS 07f7fbc1
END DESCRIPTION:
XS GIS Cut Line= 3
      1454392.78      6916650.35        1455352.      6915088.57
      1456155.96      6913822.49
#Sta/Elev= 30
  3164.2 1812.52  3632.8 1812.99    3659 1813.05  4097.5 1813.54  4452.5 1809.98
  4540.3 1808.81  4700.3 1810.01  4714.9 1809.94  4992.5 1810.34  5000.3 1808.71
  5044.2 1810.05  5050.1 1807.58  5056.9 1807.73  5059.1 1803.41  5059.6 1802.91
  5083.5 1803.41  5086.6 1809.62  5092.5 1810.47  5274.6 1809.66  5317.5 1807.67
  5326.3 1808.99  5477.9 1809.06  5499.1 1806.38  5535.5  1807.6  5550.7 1809.99
  5587.2 1808.38  5601.8 1809.72    5854 1809.26  6224.1 1817.88  6496.8 1821.22
#Mann= 8 ,-1 , 0
  3164.2    .035       0  3632.8     .07       0    3659    .035       0
  4452.5     .07       0  4700.3    .035       0  4714.9     .07       0
  5059.1     .07       0  5083.5     .07       0
Bank Sta=5059.1,5083.5
XS Rating Curve= 0 ,0
Exp/Cntr=0.3,0.1

Type RM Length L Ch R = 1 ,23191   ,393,393,393
BEGIN DESCRIPTION:
Mapping XS 27b64d96
END DESCRIPTION:
XS GIS Cut Line= 3
      1454581.69      6916829.15      1455557.73      6915453.16
      1456473.97      6914285.55
#Sta/Elev= 30
  3303.8 1811.74    3321 1811.71  3535.5 1811.72  3654.8 1811.89  3721.9 1812.56
  3782.3 1812.15  3852.7 1812.28  3927.6 1812.34  4702.5  1809.6  4839.3 1808.74
  4963.3 1809.27    4972 1808.85  4972.6 1802.41  4973.1 1801.91    4997 1802.41
  4999.2 1809.55  5048.8  1808.7  5056.9 1804.27  5063.3 1807.77  5071.4 1803.21
  5077.7  1807.7  5106.7 1803.51  5127.5 1809.72  5156.4 1805.78  5162.7 1809.79
  5170.8 1804.82  5177.2 1809.53  5199.7 1809.53  5719.5 1804.52    6475 1815.37
#Mann= 13 ,-1 , 0
  3303.8     .07       0    3321    .035       0  3535.5     .07       0
  3654.8    .035       0  3721.9     .07       0  3782.3    .035       0
  3852.7     .07       0  3927.6    .035       0  4702.5     .07       0
  4839.3    .035       0  4972.6     .07       0    4997    .035       0
  4999.2     .07       0
Bank Sta=4972.6,4997
XS Rating Curve= 0 ,0
Exp/Cntr=0.3,0.1

Type RM Length L Ch R = 1 ,22798   ,523,523,523
BEGIN DESCRIPTION:
Mapping XS dc012078
END DESCRIPTION:
XS GIS Cut Line= 3
      1454864.92      6916880.86      1455818.14      6915638.05
      1456520.42      6914354.03
#Sta/Elev= 30
  3431.9  1811.2  3614.1 1811.05  3659.6 1811.16  3794.4 1811.23  4176.2  1811.4
  4296.7 1810.69  4381.9 1811.17  4539.7 1810.61  4714.5  1808.3  4838.8 1806.98
  4917.7 1808.63    5003 1808.69  5006.9 1801.79  5007.4 1801.29  5030.8 1801.29
  5031.3 1801.79  5032.4 1807.76  5090.3 1808.94  5283.2 1807.54  5422.2 1807.34
  5498.1 1808.04  5694.5 1806.81  5754.2 1807.39  5770.4 1806.44  5784.7 1804.27
  5792.2 1804.31    5814 1806.98  5830.1 1807.27  5998.9 1808.09  6461.7 1814.28
#Mann= 7 ,-1 , 0
  3431.9     .07       0  3614.1    .035       0  3659.6     .07       0
  3794.4    .035       0  4714.5     .07       0  5006.9     .07       0
  5031.3     .07       0
Bank Sta=5006.9,5031.3
XS Rating Curve= 0 ,0
Exp/Cntr=0.3,0.1

Type RM Length L Ch R = 1 ,22275   ,657,657,657
BEGIN DESCRIPTION:
Mapping XS a84044bb
END DESCRIPTION:
XS GIS Cut Line= 4
       1454967.7      6916910.31      1455945.75      6915945.34
      1456338.55      6915613.68      1456848.98      6913868.85
#Sta/Elev= 30
  3619.2 1810.94  3710.6 1810.64  3869.4 1810.65  4074.4 1810.64  4443.9 1810.44
    4587 1810.22  4600.3 1810.16  4927.1 1808.43  4976.6 1806.95  4997.7 1802.91
    5012 1808.06  5083.5 1808.28  5565.3 1806.66  5615.7 1802.98  5627.8 1805.87
  5721.2 1806.47  5740.6 1802.68  5741.1 1802.18  5765.1 1802.68  5846.6 1806.77
    5982 1803.55  6009.6 1806.61  6127.9 1808.07  6607.2 1812.36  6647.9 1809.64
    6983 1815.89  7168.5 1818.34    7191    1819  7205.2 1818.83  7325.2 1820.71
#Mann= 13 ,-1 , 0
  3619.2     .07       0  3710.6    .035       0  3869.4     .07       0
  4074.4    .035       0  4443.9     .07       0    4587     .16       0
  4600.3     .07       0  5740.6     .07       0  5765.1     .07       0
    6983    .035       0  7168.5     .07       0    7191    .035       0
  7205.2     .07       0
Bank Sta=5740.6,5765.1
XS Rating Curve= 0 ,0
Exp/Cntr=0.3,0.1

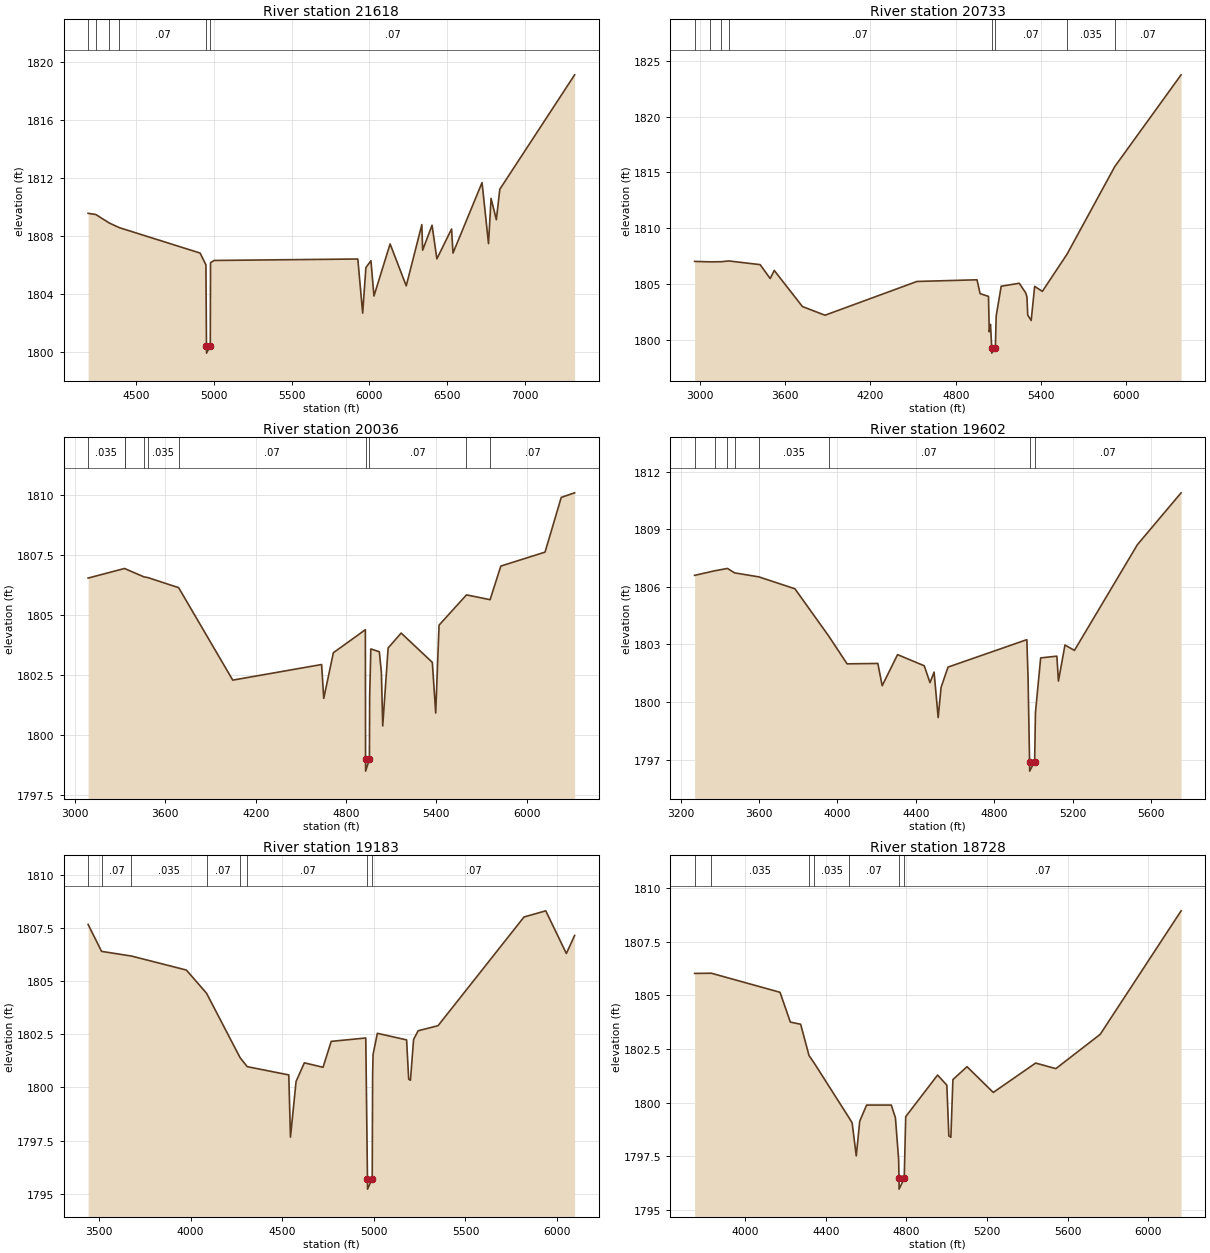
Type RM Length L Ch R = 1 ,21618   ,885,885,885
BEGIN DESCRIPTION:
Mapping XS 0f858b86
END DESCRIPTION:
XS GIS Cut Line= 3
      1455841.61      6916940.73      1456250.43       6916231.8
      1456875.02      6914004.27
#Sta/Elev= 30
  4189.8 1809.58  4239.2  1809.5  4326.4 1808.91  4391.3 1808.59  4910.8 1806.84
  4948.2 1806.03  4951.7 1800.44  4952.2 1799.94  4976.2 1800.44  4977.9 1806.18
    5001 1806.33    5926 1806.43  5957.2  1802.7    5978 1805.84  6010.5 1806.31
  6029.9 1803.88  6133.8 1807.47  6237.6 1804.58  6338.1  1808.8  6343.3 1807.04
  6403.8 1808.76  6434.9 1806.44  6529.4  1808.5  6538.8 1806.84  6725.7  1811.7
  6767.3 1807.49  6783.7 1810.61  6817.8 1809.14    6840 1811.24  7321.6 1819.13
#Mann= 6 ,-1 , 0
  4189.8    .035       0  4239.2     .07       0  4326.4     .16       0
  4391.3     .07       0  4951.7     .07       0  4976.2     .07       0
Bank Sta=4951.7,4976.2
XS Rating Curve= 0 ,0
Exp/Cntr=0.3,0.1

Type RM Length L Ch R = 1 ,20733   ,697,697,697
BEGIN DESCRIPTION:
Mapping XS ef084307
END DESCRIPTION:
XS GIS Cut Line= 4
      1455885.17      6917569.95      1456523.29      6916955.76
      1456797.31      6915841.18      1457306.93      6914552.11
#Sta/Elev= 30
  2964.5 1807.01  3072.9 1806.97  3149.2 1806.98  3205.1 1807.05  3425.4 1806.72
  3496.1 1805.47  3524.4  1806.2  3722.5 1802.96  3881.1 1802.18  4527.5 1805.21
  4949.7 1805.36  4971.4 1804.12  5030.4 1803.87  5035.7 1800.69  5044.4 1801.36
  5053.1 1799.28  5053.6 1798.78  5078.7 1799.28  5084.4 1802.11  5119.6 1804.78
  5246.7 1805.05  5291.7 1804.19  5300.8 1803.82  5306.1  1802.2  5330.5 1801.71
  5354.8 1804.77  5408.9 1804.32    5583 1807.67  5918.1 1815.52  6384.1 1823.75
#Mann= 8 ,-1 , 0
  2964.5    .035       0  3072.9     .07       0  3149.2    .035       0
  3205.1     .07       0  5053.1     .07       0  5078.7     .07       0
    5583    .035       0  5918.1     .07       0
Bank Sta=5053.1,5078.7
XS Rating Curve= 0 ,0
Exp/Cntr=0.3,0.1

Type RM Length L Ch R = 1 ,20036   ,434,434,434
BEGIN DESCRIPTION:
Mapping XS b302d926
END DESCRIPTION:
XS GIS Cut Line= 4
      1455827.69       6917652.6      1456275.89      6917296.47
      1457138.45      6916252.64      1458218.75      6915519.94
#Sta/Elev= 30
  3087.2 1806.54  3329.6 1806.94  3332.6 1806.93  3457.8 1806.59  3484.7 1806.56
  3688.6 1806.14  4048.1 1802.29  4638.3 1802.94  4652.6 1801.53  4716.4 1803.43
    4929 1804.39  4930.3    1799  4930.8  1798.5  4955.9    1799  4957.4 1801.57
  4965.3 1803.59  5021.7 1803.47  5035.4 1802.62  5044.3 1800.38  5080.2 1803.63
  5166.7 1804.25  5373.8 1803.03  5396.3 1800.92  5418.6 1804.58  5600.8 1805.84
  5757.6 1805.64  5828.9 1807.04  6122.5 1807.62  6230.3  1809.9  6319.1 1810.09
#Mann= 10 ,-1 , 0
  3087.2    .035       0  3329.6     .07       0  3332.6    .035       0
  3457.8     .07       0  3484.7    .035       0  3688.6     .07       0
  4930.3     .07       0  4955.9     .07       0  5600.8    .035       0
  5757.6     .07       0
Bank Sta=4930.3,4955.9
XS Rating Curve= 0 ,0
Exp/Cntr=0.3,0.1

Type RM Length L Ch R = 1 ,19602   ,419,419,419
BEGIN DESCRIPTION:
Mapping XS 54acd842
END DESCRIPTION:
XS GIS Cut Line= 3
      1455951.25      6917600.39      1457346.79      6916585.97
      1458078.57      6916398.47
#Sta/Elev= 30
  3271.6  1806.6  3375.4 1806.84  3439.4 1806.96  3475.5 1806.73  3599.8 1806.52
  3783.3  1805.9  3954.8 1803.45  4049.2 1801.99  4206.1 1802.01  4228.2 1800.85
  4306.6 1802.47  4442.6 1801.89    4472 1801.01  4492.8 1801.56  4513.7 1799.19
  4528.4 1800.76  4563.9 1801.82  4965.8 1803.25    4972 1801.28  4979.7  1796.9
  4980.2  1796.4  5005.6  1796.9  5009.7 1799.45  5036.3  1802.3  5118.9 1802.39
  5126.9 1801.09  5160.2 1802.97  5208.5 1802.69  5529.6  1808.2  5752.3  1810.9
#Mann= 8 ,-1 , 0
  3271.6    .035       0  3375.4     .07       0  3439.4    .035       0
  3475.5     .07       0  3599.8    .035       0  3954.8     .07       0
  4979.7     .07       0  5005.6     .07       0
Bank Sta=4979.7,5005.6
XS Rating Curve= 0 ,0
Exp/Cntr=0.3,0.1

Type RM Length L Ch R = 1 ,19183   ,455,455,455
BEGIN DESCRIPTION:
Mapping XS 4df61249
END DESCRIPTION:
XS GIS Cut Line= 3
      1456000.63      6917638.01      1457401.48      6916960.97
      1458447.92       6916624.1
#Sta/Elev= 30
  3440.7 1807.68    3514 1806.41  3677.2 1806.19  3976.9 1805.53  4086.9 1804.44
  4269.7 1801.41  4308.9 1800.98  4535.9 1800.59  4545.1 1797.66  4575.6 1800.28
  4620.8 1801.16  4722.8 1800.95  4767.5 1802.17  4956.1 1802.33  4965.3 1795.71
  4965.8 1795.21  4991.2 1795.71  4993.4 1800.57  4995.8 1801.55  5019.3 1802.55
  5178.9 1802.24  5190.2 1800.39  5199.9 1800.34    5217 1802.26  5241.9 1802.67
  5350.6 1802.91  5819.7 1808.03  5938.4 1808.32  6050.8 1806.31  6095.9 1807.16
#Mann= 8 ,-1 , 0
  3440.7    .035       0    3514     .07       0  3677.2    .035       0
  4086.9     .07       0  4269.7    .035       0  4308.9     .07       0
  4965.3     .07       0  4991.2     .07       0
Bank Sta=4965.3,4991.2
XS Rating Curve= 0 ,0
Exp/Cntr=0.3,0.1

Type RM Length L Ch R = 1 ,18728   ,452,452,452
BEGIN DESCRIPTION:
Mapping XS 4119210a
END DESCRIPTION:
XS GIS Cut Line= 3
      1456130.17      6917624.11      1457336.37      6917367.22
      1458515.67      6917301.18
#Sta/Elev= 30
  3748.5 1806.02  3831.7 1806.03  4172.6 1805.14  4223.8 1803.75  4274.9 1803.65
  4316.5 1802.19  4343.5 1801.82  4514.9 1799.29  4530.5 1799.05  4550.9 1797.51
  4568.1 1799.13  4602.1 1799.88  4724.7 1799.88  4745.2 1799.29  4761.3 1797.33
  4762.9 1796.46  4763.4 1795.96  4788.9 1796.46  4796.3 1799.34  4954.4 1801.28
  5000.4 1800.81  5010.4 1798.44  5020.4 1798.38  5030.5 1801.07  5100.6 1801.67
  5230.8 1800.47  5441.1 1801.84  5541.3 1801.58  5761.6 1803.18  6162.9 1808.94
#Mann= 7 ,-1 , 0
  3748.5     .07       0  3831.7    .035       0  4316.5     .07       0
  4343.5    .035       0  4514.9     .07       0  4762.9     .07       0
  4788.9     .07       0
Bank Sta=4762.9,4788.9
XS Rating Curve= 0 ,0
Exp/Cntr=0.3,0.1

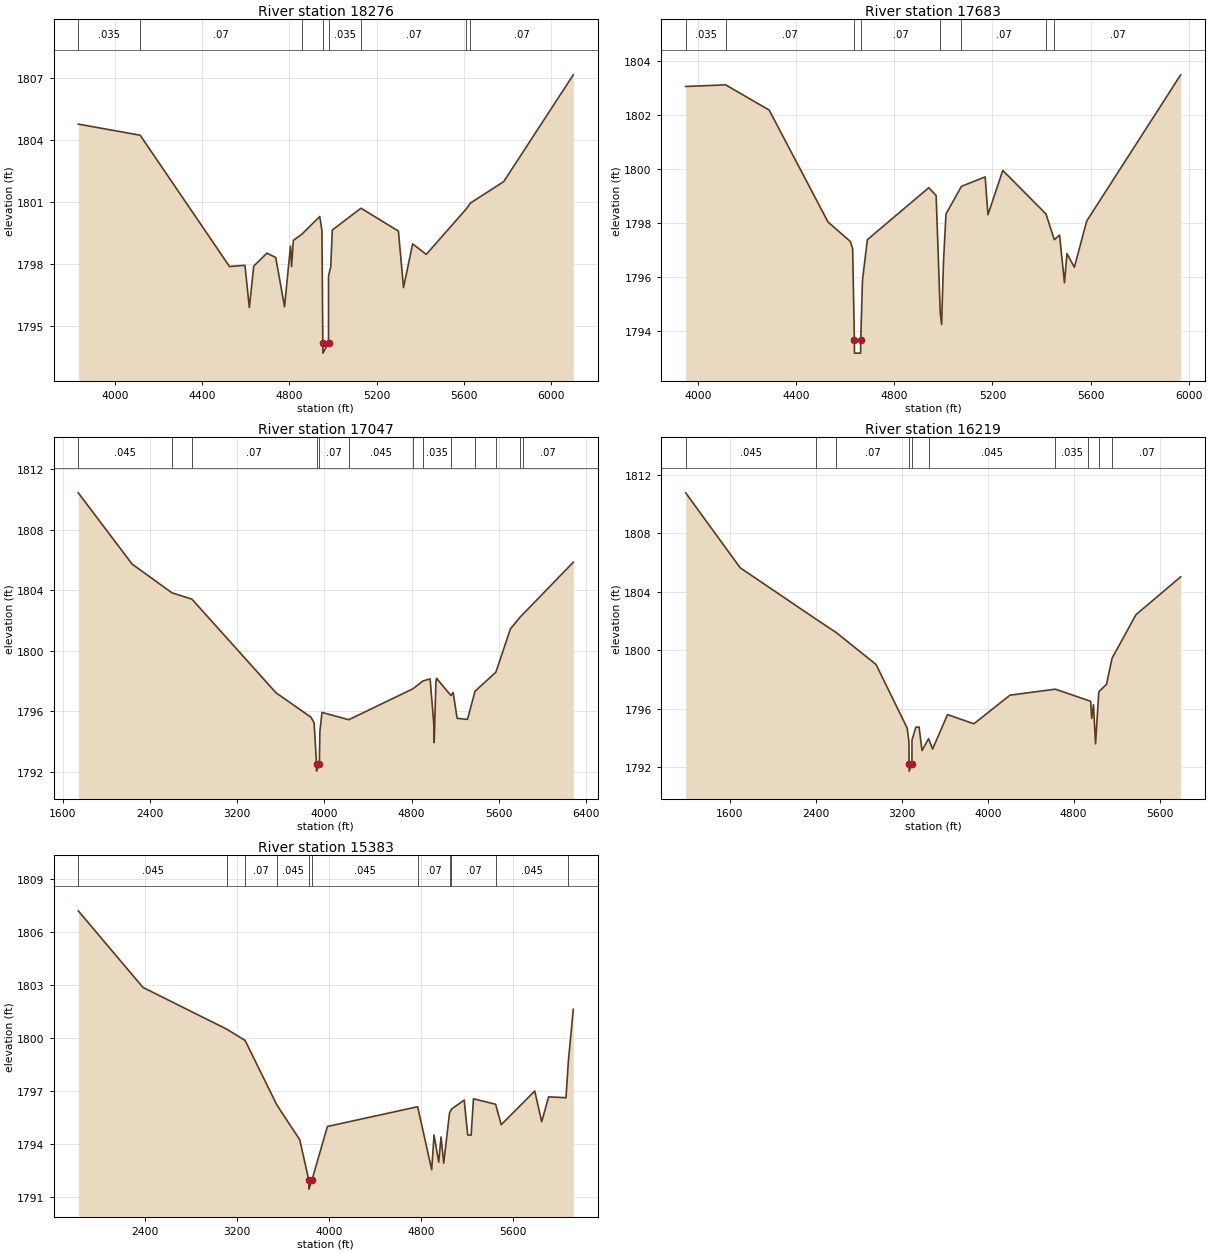
Type RM Length L Ch R = 1 ,18276   ,593,593,593
BEGIN DESCRIPTION:
Mapping XS 01dfb3d5
END DESCRIPTION:
XS GIS Cut Line= 3
      1456187.52       6917874.1      1457344.18       6917729.2
       1458400.5      6917415.93
#Sta/Elev= 30
  3833.1 1804.78  4116.6 1804.24    4526 1797.87  4596.5 1797.93  4616.7 1795.88
  4636.8 1797.89  4697.3 1798.52  4737.6 1798.31  4777.9 1795.92  4805.2 1798.87
  4810.3 1797.87  4818.2 1799.14  4857.5 1799.44  4939.2  1800.3  4949.2 1799.62
  4953.3 1794.17  4953.8 1793.67  4979.3 1794.17  4979.5 1797.42  4989.6 1797.86
  4996.7 1799.64  5128.2  1800.7  5299.5 1799.59    5323 1796.85  5364.7 1798.97
  5427.3 1798.46  5610.7 1800.67  5629.4 1800.95  5781.9 1801.99  6100.6 1807.17
#Mann= 8 ,-1 , 0
  3833.1    .035       0  4116.6     .07       0  4857.5    .035       0
  4953.3    .035       0  4979.3    .035       0  5128.2     .07       0
  5610.7    .035       0  5629.4     .07       0
Bank Sta=4953.3,4979.3
XS Rating Curve= 0 ,0
Exp/Cntr=0.3,0.1

Type RM Length L Ch R = 1 ,17683   ,636,636,636
BEGIN DESCRIPTION:
Mapping XS 5305b6fc
END DESCRIPTION:
XS GIS Cut Line= 3
      1456255.17      6918025.14      1457297.31      6918062.53
      1458265.61      6917957.43
#Sta/Elev= 30
  3950.1 1803.05  4112.9 1803.11  4290.1 1802.18  4530.3 1798.04  4620.4 1797.33
  4630.4 1797.06  4637.4  1793.7  4637.9  1793.2  4662.9  1793.2  4663.4  1793.7
  4670.4 1795.89  4690.4 1797.39  4940.6 1799.31  4970.6 1799.02  4987.4 1794.69
  4992.9 1794.26  5000.6 1796.58  5010.7 1798.34  5073.6 1799.36  5170.3 1799.71
  5181.7 1798.31  5242.1 1799.95  5418.2 1798.34    5452 1797.39  5473.4 1797.56
  5493.5  1795.8  5503.6 1796.88  5533.8 1796.37  5584.1 1798.08  5966.9 1803.48
#Mann= 8 ,-1 , 0
  3950.1    .035       0  4112.9     .07       0  4637.4    .035       0
  4663.4     .07       0  4987.4    .035       0  5073.6     .07       0
  5418.2    .035       0    5452     .07       0
Bank Sta=4637.4,4663.4
XS Rating Curve= 0 ,0
Exp/Cntr=0.3,0.1

Type RM Length L Ch R = 1 ,17047   ,828,828,828
BEGIN DESCRIPTION:
Mapping XS 3f86ba41
END DESCRIPTION:
XS GIS Cut Line= 4
      1454708.36      6920077.22      1456610.54      6918940.42
       1457544.7      6918473.99      1458633.92      6917802.11
#Sta/Elev= 30
  1742.7 1810.44  2236.1 1805.73  2601.7 1803.83    2785 1803.41  3556.1 1797.22
  3876.1 1795.61  3905.6 1795.23  3927.6 1792.54  3928.1 1792.04  3953.6 1792.54
  3958.4 1794.65  3977.9 1795.92  4223.8 1795.44  4810.5 1797.48  4903.7    1798
  4969.6 1798.14  5002.8  1795.2  5006.9 1793.92  5022.3 1797.89  5028.2 1798.18
  5160.1 1797.04  5180.7 1797.24  5217.4 1795.53    5312 1795.46  5381.4 1797.32
  5572.5 1798.58  5705.9 1801.44  5798.1 1802.25  5817.6 1802.39  6282.6 1805.85
#Mann= 13 ,-1 , 0
  1742.7    .045       0  2601.7    .035       0    2785     .07       0
  3927.6    .035       0  3953.6     .07       0  4223.8    .045       0
  4810.5     .07       0  4903.7    .035       0  5160.1     .07       0
  5381.4    .035       0  5572.5     .07       0  5798.1    .035       0
  5817.6     .07       0
Bank Sta=3927.6,3953.6
XS Rating Curve= 0 ,0
Exp/Cntr=0.3,0.1

Type RM Length L Ch R = 1 ,16219   ,836,836,836
BEGIN DESCRIPTION:
Mapping XS d2a38db8
END DESCRIPTION:
XS GIS Cut Line= 4
      1454838.59      6920368.87      1456727.84      6919211.58
      1458138.45      6918497.43      1458830.53      6918073.34
#Sta/Elev= 30
  1188.2 1810.77  1695.7 1805.64  2404.6 1802.11  2590.9  1801.2  2960.7 1799.02
  3250.8 1794.66  3266.3 1793.74  3268.7 1792.22  3269.2 1791.72  3294.8 1792.22
  3294.9 1793.83  3330.2 1794.72    3361 1794.74  3388.7 1793.13  3449.6 1793.94
  3486.9 1793.23  3626.2 1795.59  3871.3 1794.96  4207.6 1796.92  4629.7 1797.33
  4931.3 1796.57  4958.5  1796.5  4968.3 1795.33  4984.8 1796.27  5004.2 1793.59
  5034.4 1797.15    5106 1797.66    5158 1799.45  5380.7 1802.43  5796.5 1805.02
#Mann= 10 ,-1 , 0
  1188.2    .045       0  2404.6    .035       0  2590.9     .07       0
  3268.7     .07       0  3294.8     .07       0  3449.6    .045       0
  4629.7    .035       0  4931.3     .07       0  5034.4    .035       0
    5158     .07       0
Bank Sta=3268.7,3294.8
XS Rating Curve= 0 ,0
Exp/Cntr=0.3,0.1

Type RM Length L Ch R = 1 ,15383   ,745,745,745
BEGIN DESCRIPTION:
Mapping XS 4ec24c97
END DESCRIPTION:
XS GIS Cut Line= 4
      1455375.04      6920669.21      1457281.26      6919054.65
      1457945.75      6918937.53       1459068.1      6918828.16
#Sta/Elev= 30
  1821.7  1807.2  2383.5 1802.86  3112.9 1800.49  3270.5 1799.86  3546.1 1796.21
  3745.7 1794.23  3824.9 1791.93  3825.4 1791.43    3851 1791.93  3986.2 1794.98
    4770  1796.1  4892.2 1792.53  4912.5  1794.5  4953.2 1792.96  4973.5 1794.39
  4996.7  1792.9  5046.9 1795.74  5063.5 1795.96  5174.6 1796.48  5204.8  1794.5
  5234.9 1794.49    5255 1796.55  5447.5 1796.24  5496.1 1795.08  5787.5 1796.99
  5847.8 1795.25  5908.1 1796.66  6058.8 1796.61  6079.5 1798.68  6122.2 1801.62
#Mann= 11 ,-1 , 0
  1821.7    .045       0  3112.9    .035       0  3270.5     .07       0
  3546.1    .045       0  3824.9     .07       0    3851    .045       0
    4770     .07       0  5046.9    .045       0  5063.5     .07       0
  5447.5    .045       0  6079.5    .035       0
Bank Sta=3824.9,3851
XS Rating Curve= 0 ,0
Exp/Cntr=0.3,0.1