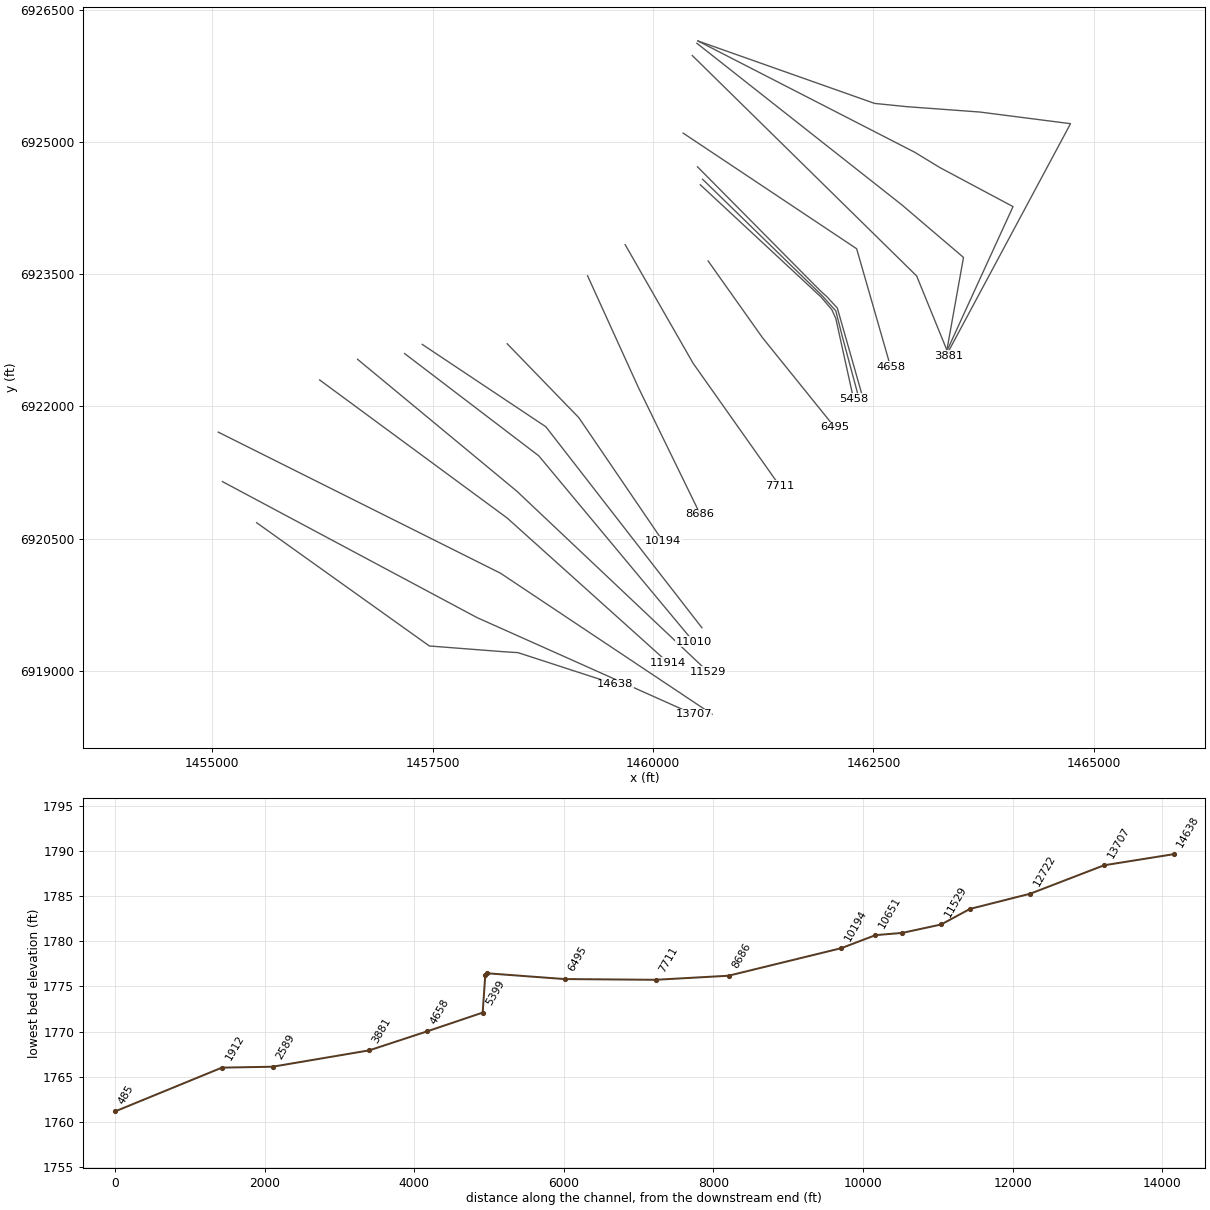
HEC-RAS study Raven Creek.prj: Raven Creek Base Level Engineering

--- Raven Creek.g01 (geometry) --- (continued)

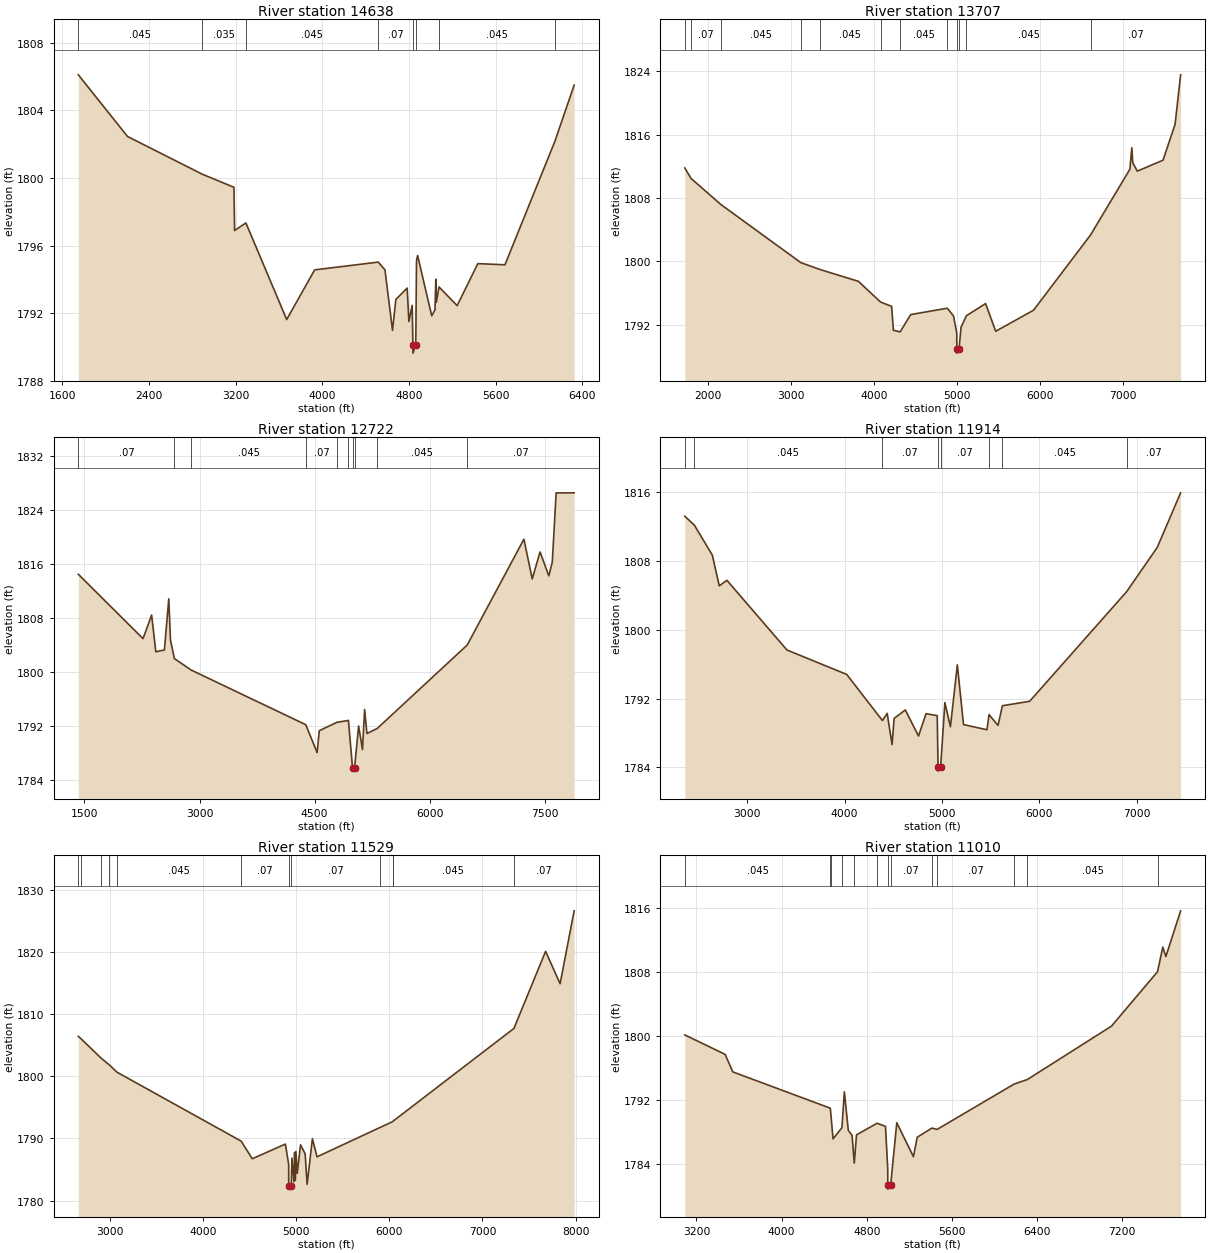
Type RM Length L Ch R = 1 ,14638   ,931,931,931
BEGIN DESCRIPTION:
Mapping XS acd2b7a3
END DESCRIPTION:
XS GIS Cut Line= 5
      1455505.19      6920679.68      1457463.98      6919281.28
      1458305.12      6919216.18      1458469.18      6919205.76
      1459571.67      6918846.93
#Sta/Elev= 30
  1749.5 1806.11  2203.1 1802.46  2891.4 1800.23  3185.1 1799.45  3191.2 1796.89
  3295.4 1797.34  3671.8 1791.62  3929.9 1794.56  4516.7 1795.02  4578.5 1794.56
    4648 1790.98  4678.8 1792.81    4783 1793.48  4799.2  1791.5  4829.3 1792.46
  4836.3 1790.13  4836.8 1789.63  4862.4 1790.13  4869.4 1795.11  4879.4 1795.41
  5009.8 1791.84  5039.9  1792.2  5047.5    1794  5052.5 1792.64  5076.8 1793.55
    5244 1792.44  5435.1 1794.93  5685.3 1794.86  6146.4 1802.18  6323.7  1805.5
#Mann= 8 ,-1 , 0
  1749.5    .045       0  2891.4    .035       0  3295.4    .045       0
  4516.7     .07       0  4836.3     .07       0  4862.4     .07       0
  5076.8    .045       0  6146.4     .07       0
Bank Sta=4836.3,4862.4
XS Rating Curve= 0 ,0
Exp/Cntr=0.3,0.1

Type RM Length L Ch R = 1 ,13707   ,985,985,985
BEGIN DESCRIPTION:
Raven Creek 10.0
END DESCRIPTION:
XS GIS Cut Line= 3
      1455117.58      6921145.89      1458004.93      6919603.07
      1460460.64      6918505.57
#Sta/Elev= 30
  1726.3 1811.78  1802.3 1810.45  2161.1 1807.16  3121.3 1799.83  3354.6 1798.95
  3813.6 1797.47    4082 1794.84  4213.6 1794.31  4235.5 1791.29    4316 1791.08
  4443.6 1793.27  4883.8 1794.07    4959 1793.08  4997.2 1790.94    4998  1788.9
  4998.5  1788.4  5024.1  1788.9  5049.3 1791.68  5113.3 1793.12  5344.2 1794.66
  5465.7 1791.16  5920.1 1793.81  6607.9 1803.34  7079.5 1811.62  7102.8 1814.33
  7114.1 1812.44  7168.8 1811.38  7478.2 1812.76    7623 1817.28  7689.8 1823.54
#Mann= 12 ,-1 , 0
  1726.3    .035       0  1802.3     .07       0  2161.1    .045       0
  3121.3    .035       0  3354.6    .045       0    4082    .035       0
    4316    .045       0  4883.8     .07       0    4998     .07       0
  5024.1     .07       0  5113.3    .045       0  6607.9     .07       0
Bank Sta=4998,5024.1
XS Rating Curve= 0 ,0
Exp/Cntr=0.3,0.1

Type RM Length L Ch R = 1 ,12722   ,808,808,808
BEGIN DESCRIPTION:
Raven Creek 9.0
END DESCRIPTION:
XS GIS Cut Line= 3
      1455070.66      6921706.73      1458270.63      6920106.75
      1460670.28      6918506.98
#Sta/Elev= 30
  1419.8 1814.43  2263.2 1804.89    2375 1808.39  2429.8 1802.95  2541.6 1803.21
  2598.6  1810.8  2620.9 1804.66  2671.3 1801.94  2889.9 1800.24  4384.1 1792.14
  4531.7 1788.01  4559.7 1791.25  4789.7 1792.49  4939.8 1792.77  4993.2 1785.76
  4993.7 1785.26  5019.7 1785.76  5072.6 1791.95  5122.9 1788.46  5150.7  1794.4
  5180.8 1790.83  5314.9 1791.58  6487.4 1803.94  7226.9 1819.63  7335.1 1813.74
  7437.2 1817.74  7551.4  1814.2  7596.5 1816.24  7646.8 1826.49  7881.5  1826.5
#Mann= 10 ,-1 , 0
  1419.8     .07       0  2671.3    .035       0  2889.9    .045       0
  4384.1     .07       0  4789.7    .035       0  4939.8     .07       0
  4993.2     .07       0  5019.7     .07       0  5314.9    .045       0
  6487.4     .07       0
Bank Sta=4993.2,5019.7
XS Rating Curve= 0 ,0
Exp/Cntr=0.3,0.1

Type RM Length L Ch R = 1 ,11914   ,385,385,385
BEGIN DESCRIPTION:
Raven Creek 8.0
END DESCRIPTION:
XS GIS Cut Line= 3
      1456220.07      6922298.63      1458347.14      6920732.06
      1460169.74      6919093.75
#Sta/Elev= 30
  2358.3  1813.2  2455.6 1812.18  2640.7 1808.69  2712.2 1805.11  2791.1 1805.75
  3407.4 1797.65  4021.4 1794.81  4387.9 1789.45  4437.1 1790.28  4487.2 1786.66
  4508.1  1789.7    4623 1790.68  4758.8 1787.65  4835.9 1790.25  4950.9 1790.02
  4959.2 1784.07  4959.7 1783.57  4985.8 1784.07  5029.6 1791.54  5086.4 1788.73
  5157.4 1795.92    5221 1788.98  5461.7 1788.38  5482.9 1790.14  5575.3 1788.88
  5620.2 1791.17  5900.4 1791.69    6897 1804.44  7210.8 1809.58  7450.7 1815.92
#Mann= 8 ,-1 , 0
  2358.3     .07       0  2455.6    .045       0  4387.9     .07       0
  4959.2     .07       0  4985.8     .07       0  5482.9    .035       0
  5620.2    .045       0    6897     .07       0
Bank Sta=4959.2,4985.8
XS Rating Curve= 0 ,0
Exp/Cntr=0.3,0.1

Type RM Length L Ch R = 1 ,11529   ,519,519,519
BEGIN DESCRIPTION:
Raven Creek 7.0
END DESCRIPTION:
XS GIS Cut Line= 3
      1456649.77      6922532.99        1458455.        6921038.
      1460621.44      6918990.93
#Sta/Elev= 30
  2660.2 1806.44  2689.1 1806.06  2903.1 1802.96  2992.9 1801.85  3075.9 1800.67
  4408.6 1789.58    4528 1786.74  4883.6  1789.1  4918.8 1785.86  4919.8 1782.35
  4920.3 1781.85  4946.4 1782.35  4953.9 1786.85  4976.1 1783.03  4982.6 1787.75
  4990.4 1783.28  4996.9 1787.92  5011.2 1784.39  5046.4 1788.98  5096.1 1787.52
  5117.2 1782.63  5173.8 1789.97  5223.6 1787.05  5898.9 1791.77  6034.1  1792.7
  6037.4 1792.76    7338 1807.72    7678 1820.13  7833.7 1814.91  7984.7 1826.65
#Mann= 12 ,-1 , 0
  2660.2    .045       0  2689.1     .07       0  2903.1    .045       0
  2992.9     .07       0  3075.9    .045       0  4408.6     .07       0
  4919.8     .07       0  4946.4     .07       0  5898.9    .035       0
  6034.1     .07       0  6037.4    .045       0    7338     .07       0
Bank Sta=4919.8,4946.4
XS Rating Curve= 0 ,0
Exp/Cntr=0.3,0.1

Type RM Length L Ch R = 1 ,11010   ,359,359,359
BEGIN DESCRIPTION:
Raven Creek 6.0
END DESCRIPTION:
XS GIS Cut Line= 3
      1457183.58      6922598.13        1458705.        6921438.
      1460460.66      6919329.01
#Sta/Elev= 30
  3090.6 1800.14  3469.7 1797.71  3541.6 1795.53  4456.6 1791.01  4459.8 1790.68
  4483.2 1787.18  4566.4 1788.57  4589.3 1793.04  4626.6 1788.24  4661.9 1787.62
  4682.5 1784.17  4703.6 1787.68  4896.4 1789.13  4975.8 1788.74  4996.6 1783.53
  4997.7 1781.42  4998.2 1780.92  5024.3 1781.42  5081.9  1789.2  5238.1 1784.96
    5274 1787.39  5412.1 1788.53  5460.6 1788.36  6183.9 1794.01  6308.4 1794.58
  7098.7 1801.23    7531 1808.01  7580.8 1811.08  7609.5  1809.9    7748  1815.6
#Mann= 13 ,-1 , 0
  3090.6    .045       0  4456.6     .07       0  4459.8    .045       0
  4566.4     .07       0  4682.5    .035       0  4896.4     .07       0
  4997.7     .07       0  5024.3     .07       0  5412.1    .035       0
  5460.6     .07       0  6183.9    .035       0  6308.4    .045       0
    7531     .07       0
Bank Sta=4997.7,5024.3
XS Rating Curve= 0 ,0
Exp/Cntr=0.3,0.1

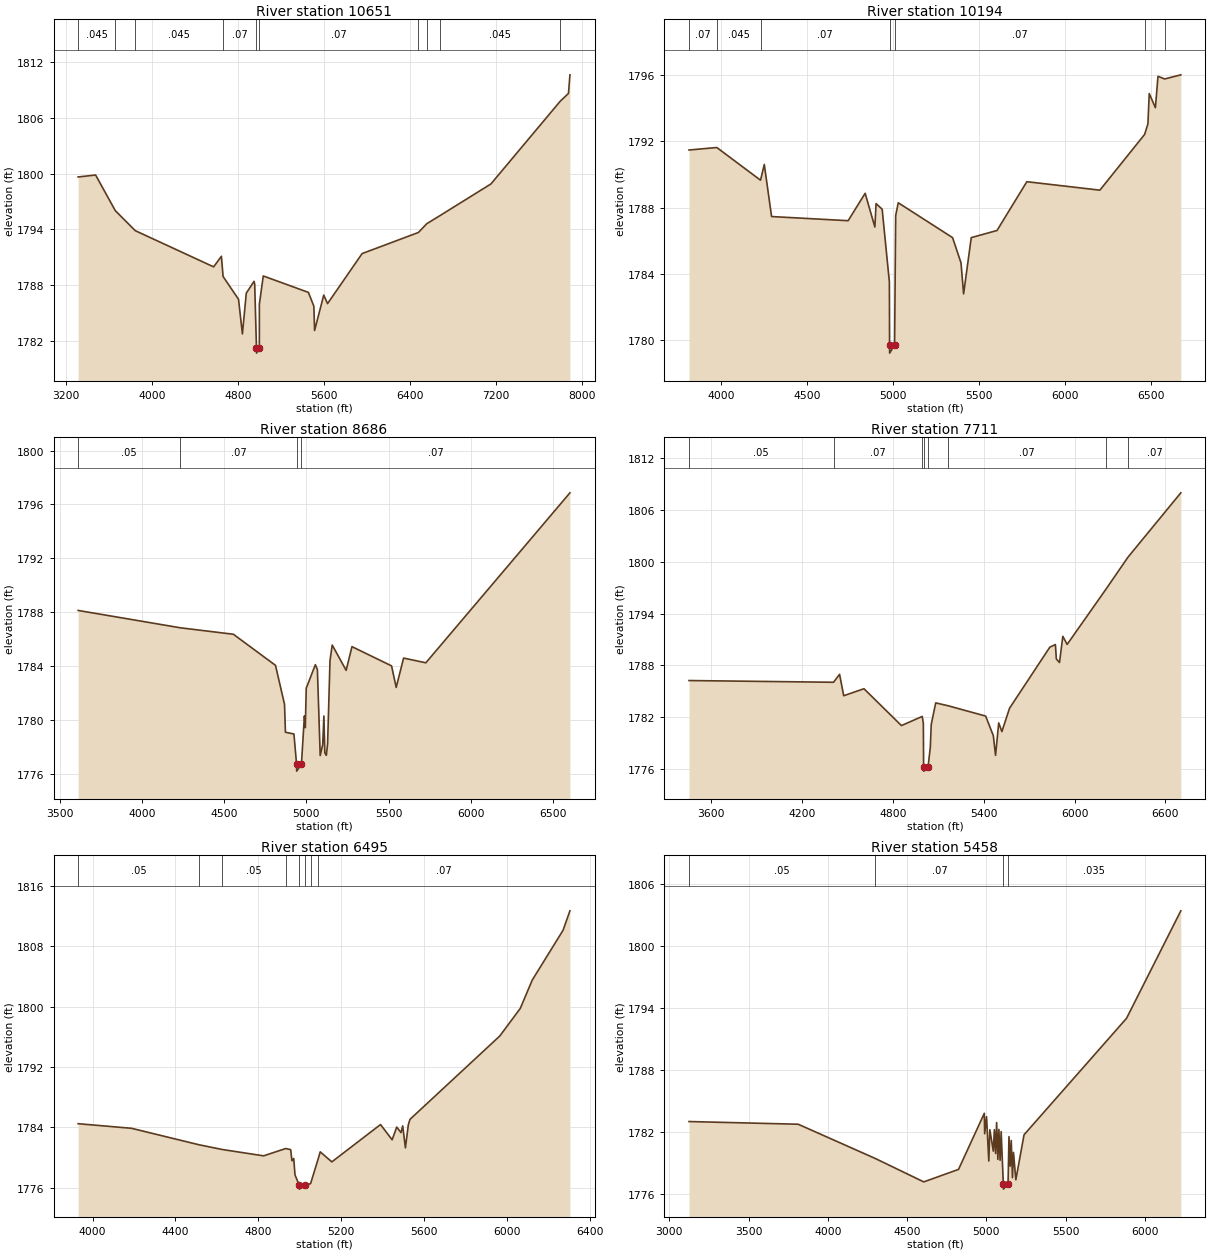
Type RM Length L Ch R = 1 ,10651   ,457,457,457
BEGIN DESCRIPTION:
Raven Creek 5.0
END DESCRIPTION:
XS GIS Cut Line= 3
      1457383.27      6922702.27      1458784.95      6921768.02
      1460554.97      6919488.03
#Sta/Elev= 30
  3315.5 1799.64  3478.1 1799.85  3660.6 1796.02  3846.1 1793.86  4574.9 1789.96
    4647  1791.1  4662.8 1788.92  4806.2 1786.47  4842.3 1782.74  4878.4 1787.13
  4950.5  1788.4  4956.5 1788.11  4973.2 1781.17  4973.7 1780.67  4999.8 1781.17
    5000 1785.94  5036.3 1788.98  5455.8 1787.21  5506.4 1785.72  5513.2 1783.11
  5598.3 1786.92  5633.6    1786  5954.9 1791.39  6477.6 1793.66  6556.2 1794.61
  6677.5 1795.47  7152.2 1798.89  7796.4  1807.8  7872.9 1808.64  7886.4 1810.64
#Mann= 10 ,-1 , 0
  3315.5    .045       0  3660.6     .07       0  3846.1    .045       0
  4662.8     .07       0  4973.2     .07       0  4999.8     .07       0
  6477.6    .035       0  6556.2     .07       0  6677.5    .045       0
  7796.4     .07       0
Bank Sta=4973.2,4999.8
XS Rating Curve= 0 ,0
Exp/Cntr=0.3,0.1

Type RM Length L Ch R = 1 ,10194   ,1508,1508,1508
BEGIN DESCRIPTION:
Mapping XS 65768020
END DESCRIPTION:
XS GIS Cut Line= 3
       1458346.8      6922709.22      1459159.29      6921870.69
      1460112.41      6920469.65
#Sta/Elev= 30
  3811.1 1791.47  3972.9 1791.62  4227.3 1789.65  4249.1  1790.6  4291.6 1787.46
  4737.1 1787.21  4836.1 1788.86  4892.7 1786.83  4899.7 1788.24  4935.2  1787.9
  4977.1 1783.52  4978.3 1779.73  4978.8 1779.23  5007.5 1779.73  5013.8 1787.52
  5028.8 1788.29  5344.8 1786.19    5394 1784.67    5409  1782.8  5453.6 1786.19
  5603.5 1786.62  5777.1 1789.56  6202.1 1789.05  6462.7 1792.41  6481.7 1793.05
  6489.4 1794.87  6525.3 1794.02  6540.3 1795.91    6579 1795.75  6673.2    1796
#Mann= 7 ,-1 , 0
  3811.1     .07       0  3972.9    .045       0  4227.3     .07       0
  4978.3     .07       0  5007.5     .07       0  6462.7    .035       0
    6579    .045       0
Bank Sta=4978.3,5007.5
XS Rating Curve= 0 ,0
Exp/Cntr=0.3,0.1

Type RM Length L Ch R = 1 ,8686    ,975,975,975
BEGIN DESCRIPTION:
Mapping XS 3f723556
END DESCRIPTION:
XS GIS Cut Line= 3
      1459258.25      6923480.05      1459836.37      6922209.23
      1460534.28      6920776.96
#Sta/Elev= 30
  3612.7 1788.12  4234.5 1786.83  4556.5 1786.35  4812.4 1784.04  4867.3 1781.14
  4872.8 1779.07  4924.4 1778.94  4940.6 1776.68  4941.1 1776.18  4969.9 1776.68
  4988.1 1780.28  4993.6 1779.41  4999.2 1782.34  5054.7 1784.09  5067.1 1783.73
  5084.1 1777.34  5099.2 1778.15  5106.6 1780.28  5112.2 1777.54  5121.4 1777.35
  5129.1 1778.22  5143.7  1784.4  5157.2 1785.55  5241.8 1783.67  5277.2 1785.43
  5517.9    1784    5546  1782.4    5591 1784.58  5726.3 1784.23  6602.1 1796.86
#Mann= 4 ,-1 , 0
  3612.7     .05       0  4234.5     .07       0  4940.6     .07       0
  4969.9     .07       0
Bank Sta=4940.6,4969.9
XS Rating Curve= 0 ,0
Exp/Cntr=0.3,0.1

Type RM Length L Ch R = 1 ,7711    ,1216,1216,1216
BEGIN DESCRIPTION:
Raven Creek 3.0
END DESCRIPTION:
XS GIS Cut Line= 3
      1459684.46      6923833.36        1460455.        6922488.
      1461434.23      6921101.41
#Sta/Elev= 30
  3453.6 1786.23  4408.1 1786.03  4447.9 1786.95  4475.2 1784.47    4609 1785.28
  4856.5 1781.01  4993.6 1782.07  5001.1 1781.29  5002.9 1776.23  5003.4 1775.73
  5032.2 1776.23  5047.1 1778.48  5053.2 1781.14  5082.8 1783.64  5166.2  1783.3
  5412.7 1782.11  5463.2 1779.84    5478 1777.56  5498.9 1781.32  5519.8 1780.31
  5570.3 1783.02  5836.5  1790.1  5873.2  1790.4  5879.4 1788.73  5900.3 1788.32
  5922.2 1791.36  5950.8 1790.42  6206.4  1796.8  6352.9 1800.54  6701.5 1807.99
#Mann= 8 ,-1 , 0
  3453.6     .05       0  4408.1     .07       0  4993.6     .12       0
  5002.9     .07       0  5032.2     .12       0  5166.2     .07       0
  6206.4    .035       0  6352.9     .07       0
Bank Sta=5002.9,5032.2
XS Rating Curve= 0 ,0
Exp/Cntr=0.3,0.1

Type RM Length L Ch R = 1 ,6495    ,1037,1037,1037
BEGIN DESCRIPTION:
Mapping XS c7dbc0ee
END DESCRIPTION:
XS GIS Cut Line= 3
      1460625.45      6923648.45      1461240.02      6922780.41
      1462062.94      6921759.57
#Sta/Elev= 30
  3930.2 1784.48  4188.1 1783.87  4513.6 1781.69  4626.4 1781.06    4826 1780.22
  4932.5 1781.19  4956.5 1781.04  4962.6 1779.57  4971.3 1779.87  4977.4  1777.7
  4998.1 1776.31  4998.6 1775.81  5027.8 1776.31  5052.7 1776.54  5088.9 1779.78
  5099.2 1780.75  5155.3 1779.42  5390.4 1784.37  5446.4 1782.35  5468.7 1784.03
  5489.5  1783.3  5497.5 1784.19  5510.6 1781.28  5524.7 1784.35  5532.7 1785.06
  5966.2  1796.1  6065.3 1799.76  6122.9 1803.51  6271.7 1810.11    6305 1812.69
#Mann= 8 ,-1 , 0
  3930.2     .05       0  4513.6     .07       0  4626.4     .05       0
  4932.5     .07       0  4998.1     .07       0  5027.8     .07       0
  5052.7     .16       0  5088.9     .07       0
Bank Sta=4998.1,5027.8
XS Rating Curve= 0 ,0
Exp/Cntr=0.3,0.1

Type RM Length L Ch R = 1 ,5458    ,24,24,24
BEGIN DESCRIPTION:
Mapping XS f3be3fd9
END DESCRIPTION:
XS GIS Cut Line= 5
      1460536.47      6924512.98      1461903.21      6923242.22
      1462028.21      6923096.39      1462073.35      6922995.69
      1462274.68      6922082.78
#Sta/Elev= 30
  3124.2 1782.99  3813.1 1782.73  4300.5 1779.41  4605.6 1777.15    4825 1778.36
  4987.7 1783.79  4989.9 1781.81  5001.7 1783.46    5016 1779.17  5022.6  1782.2
  5044.5 1780.13  5051.1  1782.2  5058.8  1779.9  5065.4 1782.89  5073.1 1779.33
  5079.6 1782.23  5087.3 1779.24  5093.9 1782.01  5107.6 1776.95  5108.1 1776.45
  5137.4 1776.95  5143.3 1781.53    5151 1778.67  5157.6 1781.16  5165.3 1777.56
  5171.8    1780  5186.5 1777.35  5238.4 1781.71  5885.2 1792.98  6227.7 1803.38
#Mann= 4 ,-1 , 0
  3124.2     .05       0  4300.5     .07       0  5107.6     .07       0
  5137.4    .035       0
Bank Sta=5107.6,5137.4
XS Rating Curve= 0 ,0
Exp/Cntr=0.3,0.1

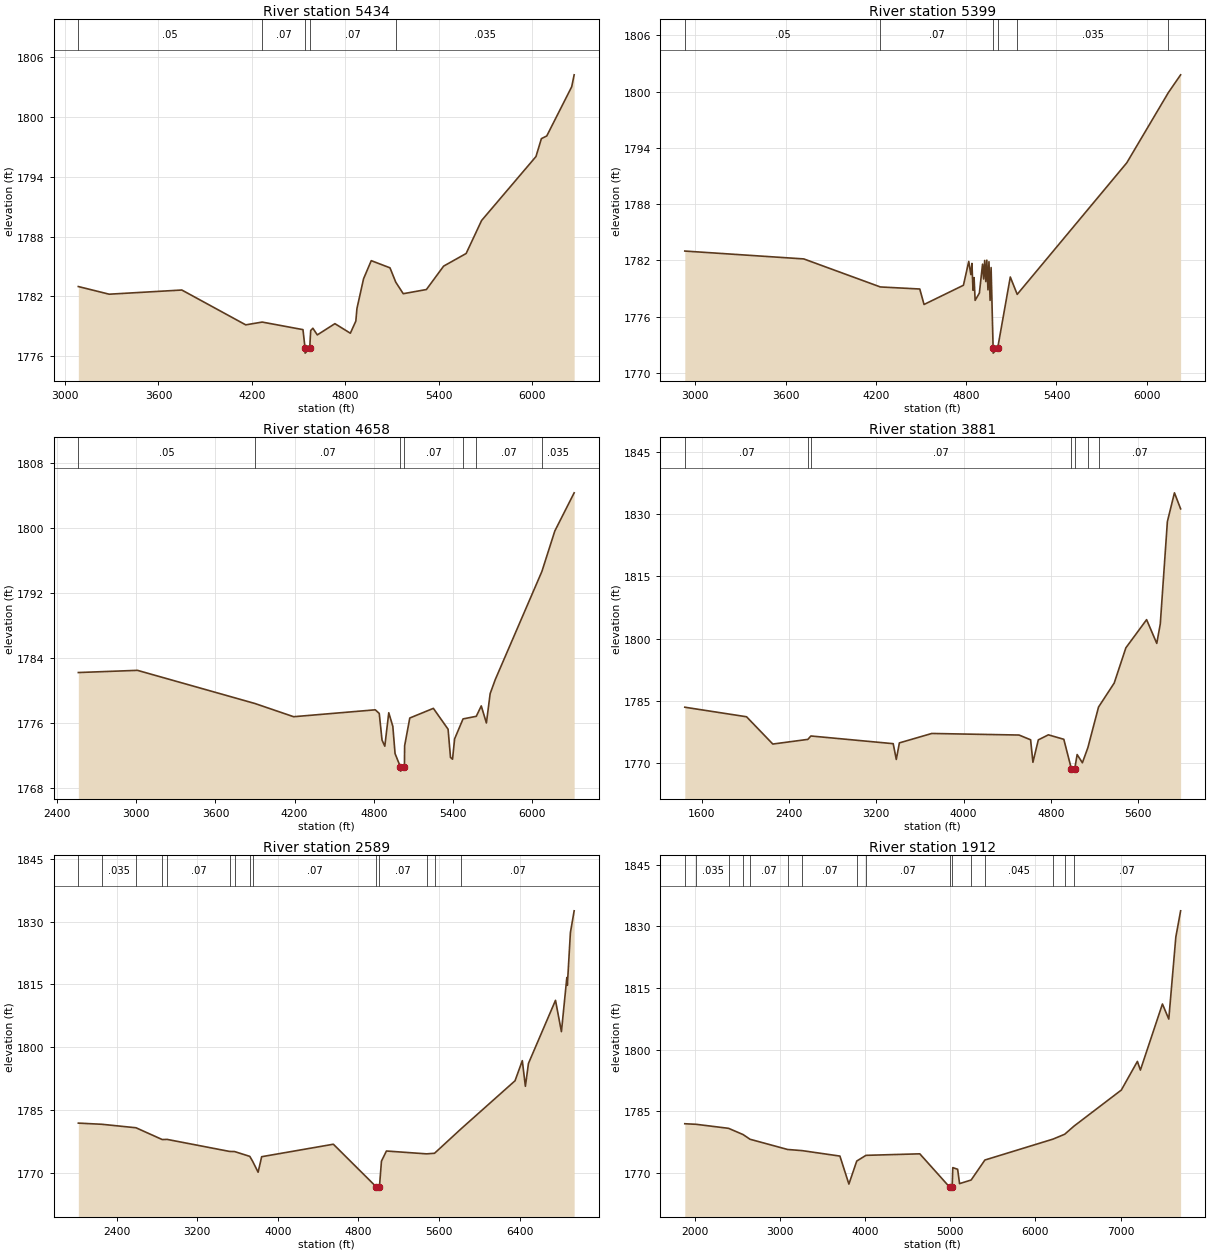
Type RM Length L Ch R = 1 ,5434    ,35,35,35
BEGIN DESCRIPTION:
Mapping XS 200dfe91
END DESCRIPTION:
XS GIS Cut Line= 5
      1460562.49      6924575.51      1461913.63      6923259.58
      1462073.35       6923082.5      1462146.27       6922794.3
      1462344.19      6922058.16
#Sta/Elev= 30
  3085.3 1782.98  3283.4 1782.21    3750 1782.63  4160.3 1779.13  4266.1 1779.41
  4527.9 1778.65  4541.3 1776.79  4541.8 1776.29  4571.1 1776.79  4577.5 1778.56
  4591.6 1778.79  4619.9 1778.12  4733.1 1779.25  4832.1 1778.29  4867.4 1779.51
  4874.5 1780.77    4917 1783.76  4966.4 1785.58  5086.7 1784.86  5123.8 1783.42
  5171.9 1782.26  5320.6 1782.68  5431.1 1785.03  5575.8  1786.3  5674.8 1789.61
  6024.2 1796.04    6059 1797.84  6093.5 1798.11  6253.6 1803.05  6269.4 1804.25
#Mann= 5 ,-1 , 0
  3085.3     .05       0  4266.1     .07       0  4541.3     .07       0
  4571.1     .07       0  5123.8    .035       0
Bank Sta=4541.3,4571.1
XS Rating Curve= 0 ,0
Exp/Cntr=0.3,0.1

Type RM Length L Ch R = 1 ,5399    ,741,741,741
BEGIN DESCRIPTION:
Mapping XS ae5cc0c3
END DESCRIPTION:
XS GIS Cut Line= 5
      1460505.22      6924716.11      1461889.32      6923318.61
      1461972.66      6923242.22      1462090.71      6923113.75
      1462375.44      6922113.73
#Sta/Elev= 30
  2930.6 1782.99  3721.1 1782.15  4229.7 1779.16  4491.8 1778.94  4520.1 1777.29
  4781.8 1779.34  4817.1 1781.88  4831.2 1780.48  4838.3 1781.67  4845.4 1778.81
  4852.5 1780.16  4859.5 1777.73  4887.8 1778.51  4908.9 1781.59  4916.3 1780.01
  4923.1 1781.99  4930.5 1779.73  4937.3 1782.02  4944.7 1778.85  4951.5 1781.85
  4958.9 1777.73  4965.6 1781.23  4979.1  1772.6  4979.6  1772.1  5008.9  1772.6
  5093.2 1780.22  5139.1 1778.37  5866.9  1792.4  6143.2 1799.89  6224.8 1801.79
#Mann= 6 ,-1 , 0
  2930.6     .05       0  4229.7     .07       0  4979.1     .07       0
  5008.9     .07       0  5139.1    .035       0  6143.2     .07       0
Bank Sta=4979.1,5008.9
XS Rating Curve= 0 ,0
Exp/Cntr=0.3,0.1

Type RM Length L Ch R = 1 ,4658    ,777,777,777
BEGIN DESCRIPTION:
Mapping XS b6fdb71f
END DESCRIPTION:
XS GIS Cut Line= 3
      1460342.29      6925098.55      1462309.46      6923787.36
      1462694.88      6922447.08
#Sta/Elev= 30
  2560.4 1782.17  3008.7 1782.44  3898.6 1778.36  4192.6 1776.73  4811.6 1777.58
  4841.6 1777.13  4862.7 1773.85  4883.7  1773.1  4913.7 1777.22  4944.6 1775.54
  4961.4 1772.19  5002.6 1770.53  5003.1 1770.03  5032.4 1770.53    5034 1773.15
    5073 1776.57  5251.9 1777.76  5363.4 1775.19  5381.7 1771.72  5397.1  1771.5
  5412.9    1774  5476.8 1776.46  5577.1 1776.78  5614.9 1778.06  5653.8 1775.96
  5682.3 1779.57  5721.2 1781.31  6074.6 1794.62  6172.5  1799.6  6319.1  1804.3
#Mann= 7 ,-1 , 0
  2560.4     .05       0  3898.6     .07       0  5002.6     .07       0
  5032.4     .07       0  5476.8     .16       0  5577.1     .07       0
  6074.6    .035       0
Bank Sta=5002.6,5032.4
XS Rating Curve= 0 ,0
Exp/Cntr=0.3,0.1

Type RM Length L Ch R = 1 ,3881    ,1292,1292,1292
BEGIN DESCRIPTION:
Mapping XS 42a33306
END DESCRIPTION:
XS GIS Cut Line= 3
      1460445.72      6925978.75      1462990.02      6923478.33
      1463358.07      6922575.56
#Sta/Elev= 30
  1446.1 1783.38  2011.8 1781.07  2252.3 1774.47  2573.6  1775.6  2601.2 1776.42
  3355.3 1774.56  3383.6 1770.75  3411.9 1774.75  3708.9 1777.03    4508 1776.65
    4614  1775.5  4635.3 1770.06  4684.7 1775.48  4776.7  1776.7  4918.2 1775.62
  4988.1 1768.42  4988.6 1767.92    5018 1768.42  5040.3 1771.93  5088.4 1769.94
  5138.8 1773.62  5236.3 1783.42  5379.8 1789.22  5486.8 1797.75  5676.7 1804.56
  5769.7 1798.82  5802.1 1803.54  5866.9 1828.27  5931.7 1835.24  5988.3 1831.37
#Mann= 7 ,-1 , 0
  1446.1     .07       0  2573.6     .16       0  2601.2     .07       0
  4988.1     .07       0    5018     .07       0  5138.8    .035       0
  5236.3     .07       0
Bank Sta=4988.1,5018
XS Rating Curve= 0 ,0
Exp/Cntr=0.3,0.1

Type RM Length L Ch R = 1 ,2589    ,677,677,677
BEGIN DESCRIPTION:
Mapping XS d9c6eb14
END DESCRIPTION:
XS GIS Cut Line= 4
      1460497.79      6926117.66      1462823.35      6924283.89
      1463521.24      6923688.67      1463337.22      6922661.34
#Sta/Elev= 30
  2019.4 1781.87  2253.7 1781.59  2591.7 1780.76  2852.1 1777.95  2901.2 1777.98
  3520.8 1775.11  3570.1 1775.08  3721.7 1773.93  3750.3 1772.74  3804.3 1770.15
  3839.5 1773.85  4551.4 1776.83  4978.8 1766.61  4979.3 1766.11  5008.7 1766.61
  5028.9  1772.8  5078.3 1775.21    5477 1774.53  5555.7 1774.67  5818.1 1780.48
    6355 1791.98  6427.2 1796.78  6457.7 1790.66  6488.1 1796.11  6756.7 1811.18
  6815.5  1803.7  6869.3 1816.64  6874.3 1814.77  6904.7 1827.36  6941.9 1832.55
#Mann= 14 ,-1 , 0
  2019.4     .07       0  2253.7    .035       0  2591.7     .07       0
  2852.1    .035       0  2901.2     .07       0  3520.8     .16       0
  3570.1     .07       0  3721.7     .16       0  3750.3     .07       0
  4978.8     .07       0  5008.7     .07       0    5477    .035       0
  5555.7    .045       0  5818.1     .07       0
Bank Sta=4978.8,5008.7
XS Rating Curve= 0 ,0
Exp/Cntr=0.3,0.1

Type RM Length L Ch R = 1 ,1912    ,1427,1427,1427
BEGIN DESCRIPTION:
Mapping XS 2da9430e
END DESCRIPTION:
XS GIS Cut Line= 5
      1460510.11      6926143.97      1462969.18      6924881.11
      1463253.91       6924707.5      1464082.91      6924265.23
      1463342.14      6922646.89
#Sta/Elev= 30
    1886 1781.94  2020.8  1781.8  2399.8 1780.82    2571 1779.29  2651.4 1778.16
  3092.1 1775.67  3262.6 1775.39    3706 1774.06  3811.3 1767.24  3903.4 1772.85
  4011.5 1774.24  4643.2 1774.61  4992.8 1766.51  4993.3 1766.01  5022.8 1766.51
  5030.4 1771.25  5087.1 1770.85  5109.8 1767.35  5245.6 1768.23  5406.8  1773.1
  6205.6 1778.19  6343.2 1779.38  6452.3 1781.36  7007.7 1790.15  7196.2 1797.13
  7231.3 1795.01  7489.9 1811.11  7564.4 1807.44  7647.1 1827.42  7703.3 1833.81
#Mann= 16 ,-1 , 0
    1886     .07       0  2020.8    .035       0  2399.8     .07       0
    2571    .035       0  2651.4     .07       0  3092.1     .16       0
  3262.6     .07       0  3903.4     .16       0  4011.5     .07       0
  4992.8     .07       0  5022.8     .07       0  5245.6    .035       0
  5406.8    .045       0  6205.6    .035       0  6343.2    .045       0
  6452.3     .07       0
Bank Sta=4992.8,5022.8
XS Rating Curve= 0 ,0
Exp/Cntr=0.3,0.1

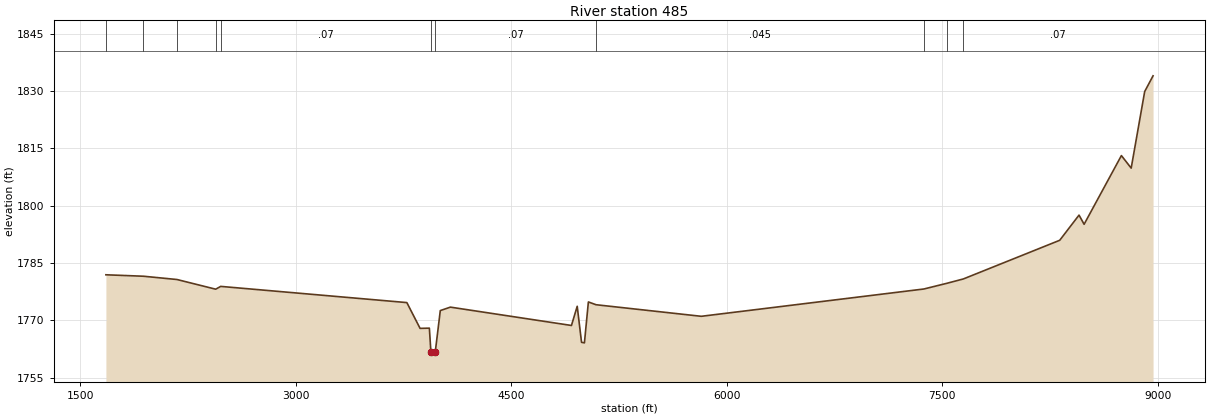
Type RM Length L Ch R = 1 ,485     ,0,0,0
BEGIN DESCRIPTION:
Raven Creek 1.0
END DESCRIPTION:
XS GIS Cut Line= 6
      1460510.12      6926143.98      1462513.29      6925435.66
       1462878.1      6925398.79      1463705.78      6925337.99
      1464734.94      6925205.87      1463351.34      6922623.81
#Sta/Elev= 30
  1678.7 1781.94  1940.2 1781.56  2173.6  1780.7  2442.8 1778.17    2478  1778.9
  3773.4 1774.66  3865.4 1767.91    3930 1767.97  3940.9 1761.67  3941.4 1761.17
  3970.9 1761.67  4006.2 1772.57  4076.5 1773.47    4919 1768.67  4959.1 1773.69
  4989.2 1764.26  5009.3 1764.12  5036.8 1774.83  5090.1  1774.1  5822.7 1771.07
  7372.3 1778.22    7534 1779.73  7646.8 1780.85  8317.4 1790.97  8451.7 1797.56
  8487.1 1795.16  8746.7 1813.14  8814.8 1809.86  8908.8 1829.91    8967 1834.02
#Mann= 11 ,-1 , 0
  1678.7     .07       0  1940.2    .035       0  2173.6     .07       0
  2442.8    .035       0    2478     .07       0  3940.9     .07       0
  3970.9     .07       0  5090.1    .045       0  7372.3    .035       0
    7534    .045       0  7646.8     .07       0
Bank Sta=3940.9,3970.9
XS Rating Curve= 0 ,0
Exp/Cntr=0.3,0.1

Chan Stop Cuts=-1
Use User Specified Reach Order=0
Composite Channel Slope=5