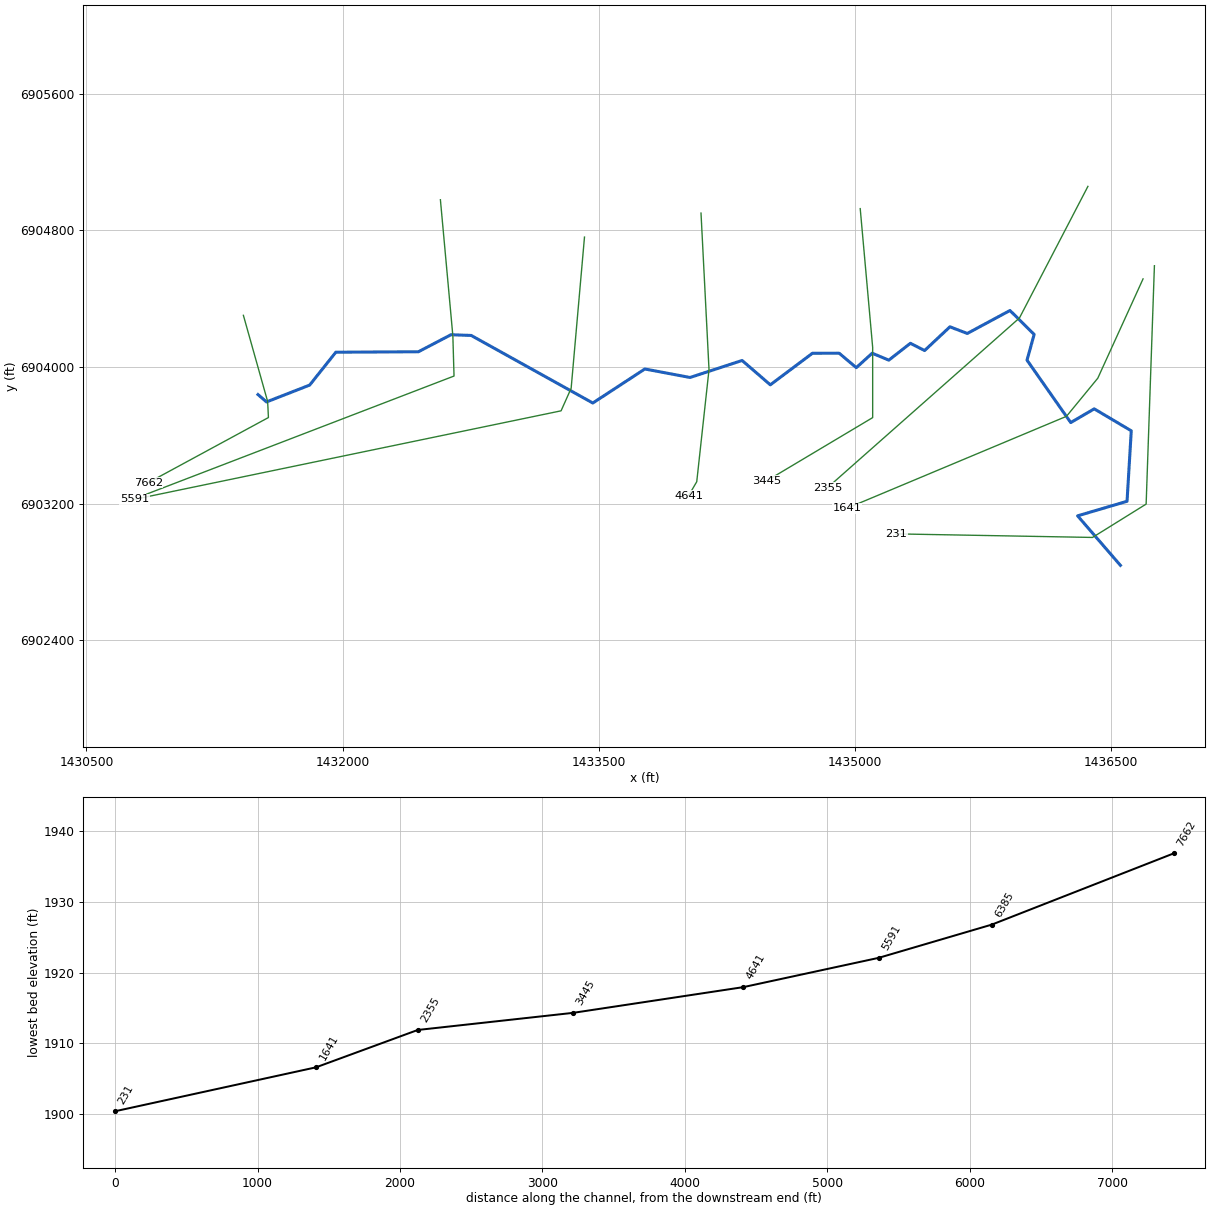
--- Raven Creek Trib1.prj (project) ---

Proj Title=Raven Creek Trib1 Base Level Engineering
Current Plan=p01
Default Exp/Contr=0.3,0.1
English Units
Geom File=g01
Flow File=f01
Plan File=p01
BEGIN DESCRIPTION:
Raven Creek Trib1
END DESCRIPTION:

--- Raven Creek Trib1.p01 (plan) ---

Plan Title=Multiple Run
Short Identifier=Multiple
Geom File=g01
Flow File=f01
Subcritical Flow
K Sum by GR= 0
Std Step Tol= 0.01
Critical Tol= 0.01
Num of Std Step Trials= 20
Max Error Tol= 0.3
Flow Tol Ratio= 0.001
Split Flow NTrial= 30
Split Flow Tol= 0.02
Split Flow Ratio= 0.02
Log Output Level= 0
Friction Slope Method= 1
Unsteady Friction Slope Method= 2
Unsteady Bridges Friction Slope Method= 1
Parabolic Critical Depth
Global Vel Dist=  1 , 1 , 1
Global Log Level= 0
CheckData=True
Encroach Param= -1, 0, 0, 0
BEGIN DESCRIPTION:
Multiple Run
END DESCRIPTION:

--- Raven Creek Trib1.f01 (steady flow) ---

Flow Title=Multiple
Number of Profiles=7
Profile Names=10-year,25-year,50-year,1pct_min,100-year,1pct_plu,500-year
River Rch & RM= Raven Creek Trib,Reach-1,7662
     289     412     516     322     642    1282    1007
River Rch & RM= Raven Creek Trib,Reach-1,6385
     391     565     714     449     895    1786    1425
Boundary for River Rch & Prof#=Raven Creek Trib,Reach-1,1
Up Type=0
Dn Type=3
Dn Slope=0.005
Boundary for River Rch & Prof#=Raven Creek Trib,Reach-1,2
Up Type=0
Dn Type=3
Dn Slope=0.005
Boundary for River Rch & Prof#=Raven Creek Trib,Reach-1,3
Up Type=0
Dn Type=3
Dn Slope=0.005
Boundary for River Rch & Prof#=Raven Creek Trib,Reach-1,4
Up Type=0
Dn Type=3
Dn Slope=0.005
Boundary for River Rch & Prof#=Raven Creek Trib,Reach-1,5
Up Type=0
Dn Type=3
Dn Slope=0.005
Boundary for River Rch & Prof#=Raven Creek Trib,Reach-1,6
Up Type=0
Dn Type=3
Dn Slope=0.005
Boundary for River Rch & Prof#=Raven Creek Trib,Reach-1,7
Up Type=0
Dn Type=3
Dn Slope=0.005

--- Raven Creek Trib1.g01 (geometry) ---

Geom Title=Existing Conditions

River Reach=Raven Creek Trib,Reach-1
Reach XY= 30
      1431505.00      6903838.00      1431554.88      6903794.87
      1431807.44      6903893.52      1431960.67      6904086.02
      1432444.30      6904088.80      1432634.86      6904188.40
      1432753.44      6904184.26      1433465.64      6903788.55
      1433770.39      6903987.92      1434034.97      6903938.07
      1434339.78      6904037.76      1434505.00      6903895.07
      1434751.69      6904079.93      1434908.41      6904080.15
      1435008.33      6903995.64      1435101.59      6904080.15
      1435198.95      6904039.67      1435325.16      6904138.32
      1435408.41      6904095.82      1435556.65      6904234.84
      1435658.41      6904195.85      1435908.33      6904330.39
      1436049.91      6904190.30      1436008.13      6904039.63
      1436264.13      6903674.09      1436401.76      6903754.42
      1436618.60      6903625.77      1436593.86      6903213.01
      1436304.45      6903127.81      1436555.00      6902838.00

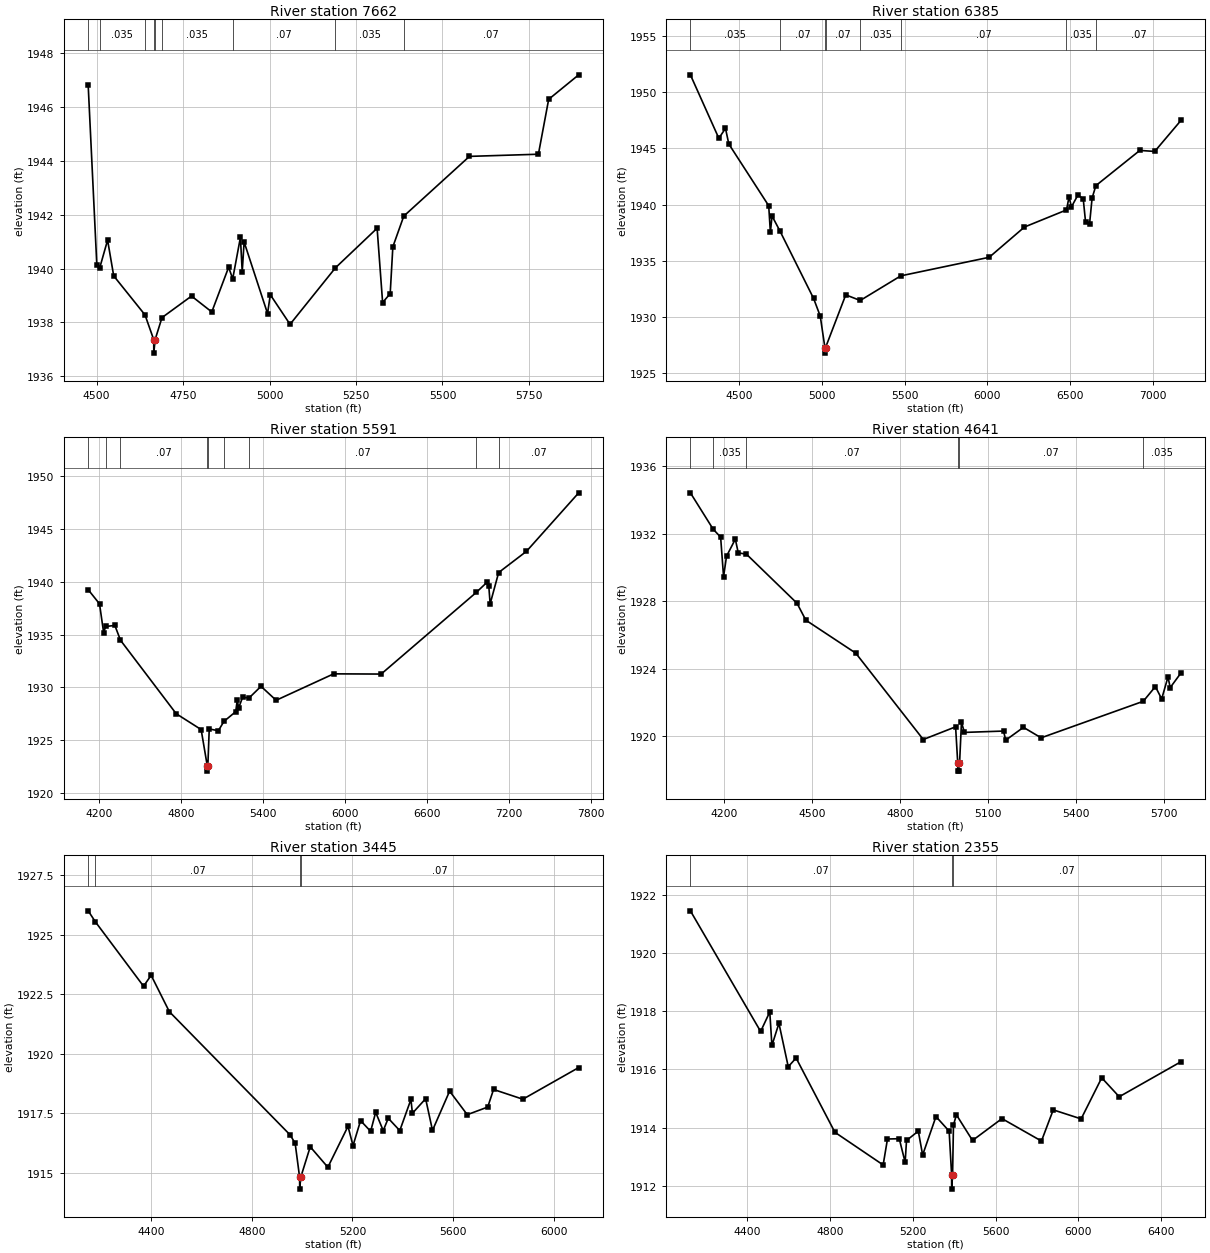
Type RM Length L Ch R = 1,7662,1277,1277,1277
BEGIN DESCRIPTION:
Mapping XS a41189c9
END DESCRIPTION:
XS GIS Cut Line= 4
      1431419.46      6904302.04      1431561.51      6903797.14
      1431566.06      6903703.52      1430862.53      6903322.30
#Sta/Elev= 30
  4475.5 1946.81  4500.5 1940.13  4509.1 1940.04  4531.6 1941.06  4549.3 1939.73
  4639.8 1938.28  4665.0 1937.36  4665.2 1936.86  4669.0 1937.36  4688.9 1938.18
  4774.3 1938.98  4832.9 1938.39  4881.6 1940.05  4893.4 1939.62  4915.7 1941.16
  4920.9 1939.88  4926.4 1940.99  4994.2 1938.33  5002.1 1939.03  5059.2 1937.93
  5190.5 1940.03  5311.0 1941.50  5326.9 1938.74  5348.8 1939.07  5356.5 1940.81
  5388.1 1941.95  5578.0 1944.17  5777.4 1944.25  5807.1 1946.29  5893.9 1947.20
#Mann=9,-1,0
  4475.5    0.07       0  4509.1   0.035       0  4639.8    0.07       0
  4665.0    0.07       0  4669.0    0.07       0  4688.9   0.035       0
  4893.4    0.07       0  5190.5   0.035       0  5388.1    0.07       0
Bank Sta=4665,4669
Exp/Cntr=0.3,0.1

Type RM Length L Ch R = 1,6385,794,794,794
BEGIN DESCRIPTION:
Mapping XS 5a37ee72
END DESCRIPTION:
XS GIS Cut Line= 4
      1432573.10      6904979.10      1432646.01      6904182.27
      1432652.87      6903946.58      1430854.27      6903255.61
#Sta/Elev= 30
  4206.1 1951.53  4377.9 1945.89  4418.1 1946.77  4438.2 1945.38  4679.2 1939.89
  4689.2 1937.53  4699.3 1938.98  4747.6 1937.63  4950.3 1931.65  4990.5 1930.08
  5018.5 1927.29  5018.7 1926.79  5022.6 1927.29  5144.5 1931.97  5231.9 1931.47
  5477.0 1933.66  6011.1 1935.31  6224.0 1938.00  6477.8 1939.52  6493.1 1940.66
  6508.0 1939.80  6546.7 1940.84  6578.8 1940.52  6592.7 1938.49  6617.4 1938.30
  6632.4 1940.57  6655.3 1941.68  6920.7 1944.81  7010.7 1944.72  7168.8 1947.47
#Mann=8,-1,0
  4206.1   0.035       0  4747.6    0.07       0  5018.5    0.07       0
  5022.6    0.07       0  5231.9   0.035       0  5477.0    0.07       0
  6477.8   0.035       0  6655.3    0.07       0
Bank Sta=5018.5,5022.6
Exp/Cntr=0.3,0.1

Type RM Length L Ch R = 1,5591,950,950,950
BEGIN DESCRIPTION:
Mapping XS 5e114c7c
END DESCRIPTION:
XS GIS Cut Line= 4
      1433416.84      6904760.38      1433338.72      6903874.98
      1433279.77      6903742.85      1430781.32      6903224.35
#Sta/Elev= 30
  4123.7 1939.25  4206.5 1937.91  4236.5 1935.20  4251.6 1935.77  4318.6 1935.87
  4359.7 1934.47  4767.0 1927.52  4949.3 1926.02  4994.1 1922.59  4994.4 1922.09
  4998.3 1922.59  5008.5 1926.08  5074.9 1925.91  5116.4 1926.80  5201.8 1927.71
  5213.2 1928.80  5223.4 1928.07  5251.9 1929.06  5300.4 1929.02  5386.8 1930.11
  5497.5 1928.79  5917.9 1931.29  6265.1 1931.27  6960.2 1938.99  7041.3 1939.98
  7051.5 1939.64  7061.7 1937.91  7123.8 1940.87  7327.3 1942.88  7708.9 1948.41
#Mann=9,-1,0
  4123.7    0.07       0  4251.6   0.035       0  4359.7    0.07       0
  4994.1    0.07       0  4998.3    0.07       0  5116.4   0.035       0
  5300.4    0.07       0  6960.2   0.035       0  7123.8    0.07       0
Bank Sta=4994.1,4998.3
Exp/Cntr=0.3,0.1

Type RM Length L Ch R = 1,4641,1196,1196,1196
BEGIN DESCRIPTION:
Mapping XS 58610851
END DESCRIPTION:
XS GIS Cut Line= 4
      1434099.14      6904901.00      1434146.01      6903984.36
      1434074.20      6903327.82      1434026.89      6903246.58
#Sta/Elev= 30
  4085.9 1934.41  4163.5 1932.26  4189.0 1931.79  4199.0 1929.45  4209.1 1930.66
  4239.1 1931.67  4249.1 1930.86  4277.1 1930.78  4449.4 1927.88  4479.4 1926.88
  4649.6 1924.93  4879.9 1919.82  4990.1 1920.57  4997.3 1918.45  4997.6 1917.95
  5001.3 1917.95  5001.6 1918.45  5003.7 1918.45  5010.1 1920.84  5020.2 1920.24
  5153.5 1920.32  5161.0 1919.78  5221.4 1920.54  5281.7 1919.92  5629.9 1922.08
  5671.2 1922.95  5692.7 1922.22  5714.2 1923.52  5721.8 1922.89  5758.2 1923.75
#Mann=6,-1,0
  4085.9    0.07       0  4163.5   0.035       0  4277.1    0.07       0
  4997.3    0.07       0  5001.6    0.07       0  5629.9   0.035       0
Bank Sta=4997.3,5001.6
Exp/Cntr=0.3,0.1

Type RM Length L Ch R = 1,3445,1090,1090,1090
BEGIN DESCRIPTION:
Mapping XS 51b9b1e1
END DESCRIPTION:
XS GIS Cut Line= 4
      1435031.43      6904927.08      1435104.34      6904114.56
      1435104.34      6903703.11      1434484.52      6903333.30
#Sta/Elev= 30
  4150.2 1926.01  4178.6 1925.55  4370.2 1922.84  4400.3 1923.30  4472.7 1921.77
  4952.5 1916.59  4972.5 1916.24  4990.3 1914.81  4990.6 1914.31  4994.8 1914.81
  5032.5 1916.09  5102.5 1915.23  5182.5 1916.95  5202.5 1916.14  5232.5 1917.19
  5272.5 1916.74  5292.5 1917.54  5322.5 1916.77  5342.5 1917.29  5388.3 1916.77
  5432.6 1918.08  5438.5 1917.50  5491.0 1918.11  5518.3 1916.78  5586.3 1918.43
  5656.4 1917.44  5737.7 1917.76  5760.9 1918.50  5877.4 1918.09  6099.2 1919.42
#Mann=4,-1,0
  4150.2   0.035       0  4178.6    0.07       0  4990.3    0.07       0
  4994.8    0.07       0
Bank Sta=4990.3,4994.8
Exp/Cntr=0.3,0.1

Type RM Length L Ch R = 1,2355,714,714,714
BEGIN DESCRIPTION:
Mapping XS 93d4fd6b
END DESCRIPTION:
XS GIS Cut Line= 3
      1436364.76      6905057.28      1435963.72      6904286.44
      1434840.12      6903292.88
#Sta/Elev= 30
  4126.3 1921.44  4465.5 1917.30  4509.7 1917.97  4520.0 1916.82  4553.9 1917.58
  4598.9 1916.09  4636.7 1916.39  4824.3 1913.84  5057.2 1912.72  5078.1 1913.61
  5135.0 1913.62  5163.4 1912.81  5170.1 1913.56  5227.0 1913.88  5247.9 1913.06
  5312.3 1914.38  5375.9 1913.88  5387.8 1912.39  5388.1 1911.89  5392.5 1912.39
  5396.8 1914.09  5411.0 1914.44  5488.8 1913.56  5631.0 1914.31  5821.7 1913.54
  5878.6 1914.61  6013.3 1914.30  6112.8 1915.71  6197.3 1915.06  6495.1 1916.26
#Mann=3,-1,0
  4126.3    0.07       0  5387.8    0.07       0  5392.5    0.07       0
Bank Sta=5387.8,5392.5
Exp/Cntr=0.3,0.1

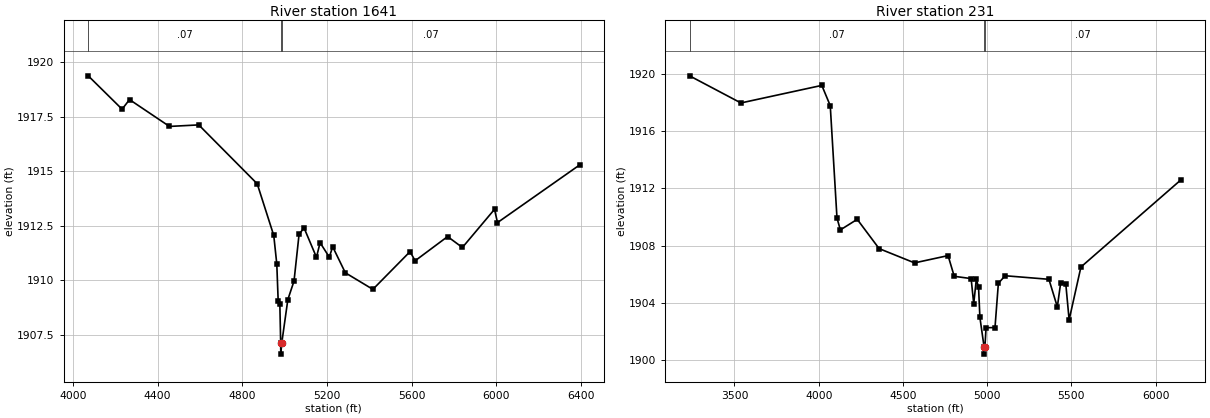
Type RM Length L Ch R = 1,1641,1410,1410,1410
BEGIN DESCRIPTION:
Mapping XS a07906b4
END DESCRIPTION:
XS GIS Cut Line= 4
      1436687.67      6904515.58      1436422.60      6903933.90
      1436239.26      6903710.67      1434954.66      6903172.42
#Sta/Elev= 30
  4071.9 1919.37  4231.8 1917.84  4267.0 1918.28  4455.7 1917.05  4594.0 1917.12
  4870.2 1914.42  4948.4 1912.05  4962.7 1910.74  4969.2 1909.06  4977.1 1908.91
  4981.1 1907.11  4981.5 1906.61  4986.0 1907.11  5014.9 1909.11  5044.1 1909.96
  5067.9 1912.10  5091.4 1912.40  5150.1 1911.05  5167.2 1911.72  5210.6 1911.06
  5226.9 1911.53  5286.5 1910.34  5416.6 1909.58  5592.3 1911.31  5616.1 1910.89
  5769.6 1912.00  5839.5 1911.50  5991.3 1913.25  6005.3 1912.64  6392.8 1915.28
#Mann=3,-1,0
  4071.9    0.07       0  4981.1    0.07       0  4986.0    0.07       0
Bank Sta=4981.1,4986
Exp/Cntr=0.3,0.1

Type RM Length L Ch R = 1,231,0,0,0
BEGIN DESCRIPTION:
Raven Creek Trib1 1.0
END DESCRIPTION:
XS GIS Cut Line= 4
      1436754.18      6904592.66      1436705.71      6903196.67
      1436391.64      6903001.32      1435241.83      6903022.17
#Sta/Elev= 30
  3233.3 1919.89  3538.1 1917.99  4018.4 1919.22  4068.5 1917.80  4108.5 1909.93
  4128.5 1909.10  4228.6 1909.84  4358.6 1907.79  4568.8 1906.79  4768.0 1907.30
  4804.6 1905.85  4904.9 1905.69  4920.3 1903.93  4935.6 1905.63  4948.9 1905.10
  4956.9 1902.98  4981.8 1900.90  4982.1 1900.40  4986.8 1900.90  4993.5 1902.25
  5046.6 1902.26  5066.6 1905.36  5106.7 1905.89  5366.7 1905.64  5416.7 1903.71
  5436.7 1905.41  5466.7 1905.34  5486.7 1902.80  5556.7 1906.50  6150.0 1912.60
#Mann=3,-1,0
  3233.3    0.07       0  4981.8    0.07       0  4986.8    0.07       0
Bank Sta=4981.8,4986.8
Exp/Cntr=0.3,0.1

Chan Stop Cuts=-1