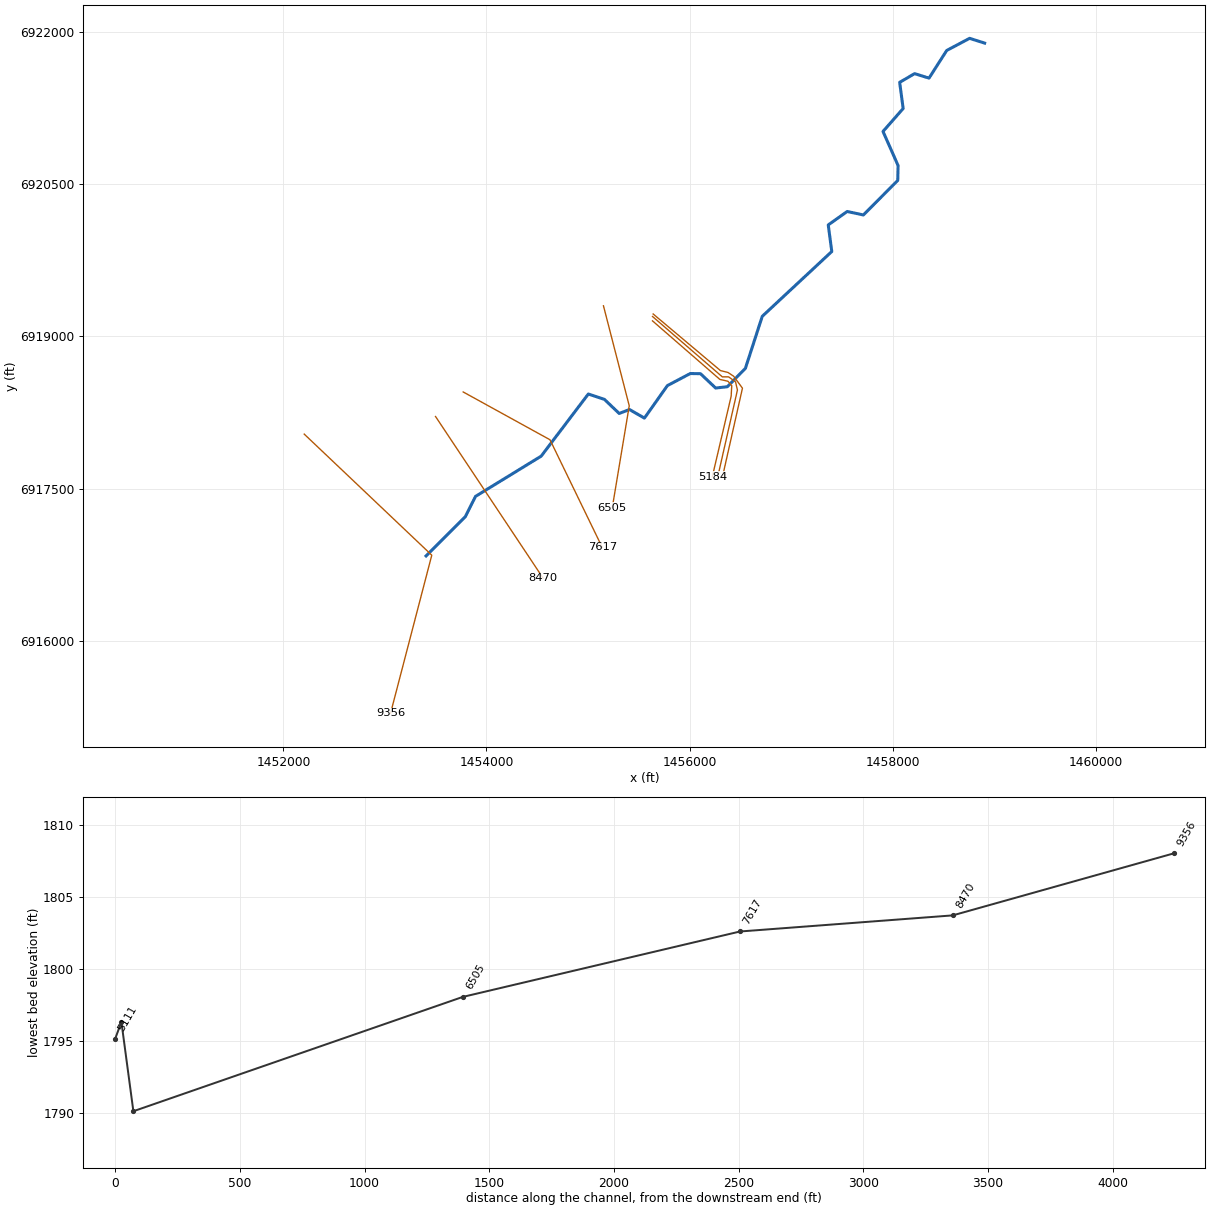
--- Raven Creek Trib3.prj (project) ---

Proj Title=Raven Creek Trib3 Base Level Engineering
Current Plan=p01
Default Exp/Contr=0.3,0.1
English Units
Geom File=g01
Flow File=f01
Plan File=p01
BEGIN DESCRIPTION:
Raven Creek Trib3
END DESCRIPTION:

--- Raven Creek Trib3.p01 (plan) ---

Plan Title=Multiple Run
Short Identifier=Multiple
Geom File=g01
Flow File=f01
Subcritical Flow
K Sum by GR= 0
Std Step Tol= 0.01
Critical Tol= 0.01
Num of Std Step Trials= 20
Max Error Tol= 0.3
Flow Tol Ratio= 0.001
Split Flow NTrial= 30
Split Flow Tol= 0.02
Split Flow Ratio= 0.02
Log Output Level= 0
Friction Slope Method= 1
Unsteady Friction Slope Method= 2
Unsteady Bridges Friction Slope Method= 1
Parabolic Critical Depth
Global Vel Dist=  1 , 1 , 1
Global Log Level= 0
CheckData=True
Encroach Param= -1, 0, 0, 0
BEGIN DESCRIPTION:
Multiple Run
END DESCRIPTION:

--- Raven Creek Trib3.f01 (steady flow) ---

Flow Title=Multiple
Number of Profiles=7
Profile Names=10-year,25-year,50-year,1pct_min,100-year,1pct_plu,500-year
River Rch & RM= Raven Creek Trib,Reach-1,9356
     206     281     340     205     409     816     598
River Rch & RM= Raven Creek Trib,Reach-1,8470
     316     439     539     329     657    1311     986
Boundary for River Rch & Prof#=Raven Creek Trib,Reach-1,1
Up Type=0
Dn Type=3
Dn Slope=0.005
Boundary for River Rch & Prof#=Raven Creek Trib,Reach-1,2
Up Type=0
Dn Type=3
Dn Slope=0.005
Boundary for River Rch & Prof#=Raven Creek Trib,Reach-1,3
Up Type=0
Dn Type=3
Dn Slope=0.005
Boundary for River Rch & Prof#=Raven Creek Trib,Reach-1,4
Up Type=0
Dn Type=3
Dn Slope=0.005
Boundary for River Rch & Prof#=Raven Creek Trib,Reach-1,5
Up Type=0
Dn Type=3
Dn Slope=0.005
Boundary for River Rch & Prof#=Raven Creek Trib,Reach-1,6
Up Type=0
Dn Type=3
Dn Slope=0.005
Boundary for River Rch & Prof#=Raven Creek Trib,Reach-1,7
Up Type=0
Dn Type=3
Dn Slope=0.005

--- Raven Creek Trib3.g01 (geometry) ---

Geom Title=Existing Conditions

River Reach=Raven Creek Trib,Reach-1
Reach XY= 30
      1453405.00      6916838.00      1453791.60      6917224.70
      1453891.76      6917424.39      1454538.58      6917820.92
      1455002.70      6918432.91      1455161.06      6918379.86
      1455306.65      6918241.16      1455408.31      6918279.93
      1455555.09      6918195.29      1455781.16      6918515.15
      1456006.59      6918634.33      1456107.43      6918632.60
      1456256.50      6918491.46      1456371.75      6918504.40
      1456549.48      6918685.57      1456715.47      6919197.82
      1457399.89      6919835.70      1457365.19      6920097.70
      1457551.68      6920229.96      1457711.17      6920195.76
      1458049.55      6920535.55      1458052.75      6920682.06
      1457904.55      6921017.97      1458102.76      6921243.93
      1458068.38      6921501.74      1458215.68      6921587.25
      1458357.31      6921543.09      1458531.42      6921815.15
      1458756.63      6921934.88      1458905.00      6921888.00

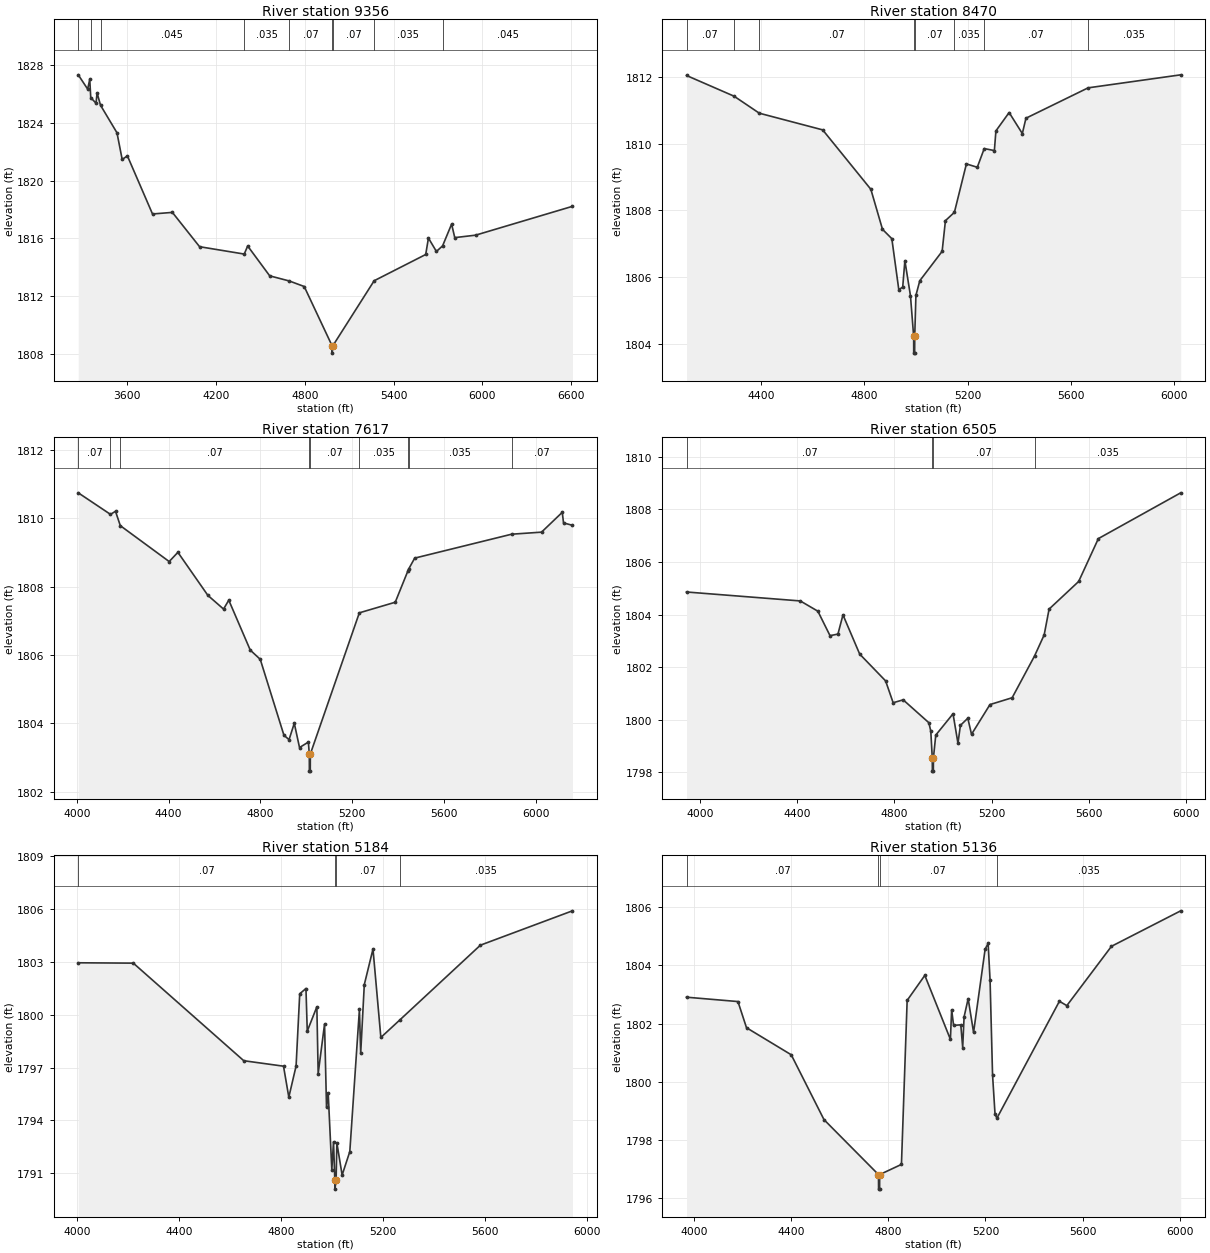
Type RM Length L Ch R = 1,9356,886,886,886
BEGIN DESCRIPTION:
Raven Creek Trib3 3.0
END DESCRIPTION:
XS GIS Cut Line= 3
      1452205.02      6918037.98      1453461.24      6916845.75
      1453054.99      6915287.95
#Sta/Elev= 30
  3268.1 1827.33  3331.8 1826.34  3345.9 1827.02  3352.6 1825.75  3388.4 1825.36
  3395.3 1826.08  3418.7 1825.22  3530.0 1823.31  3565.2 1821.46  3600.4 1821.71
  3770.3 1817.68  3904.6 1817.79  4088.6 1815.41  4390.6 1814.90  4413.8 1815.46
  4562.7 1813.39  4696.3 1813.03  4796.1 1812.65  4985.0 1808.53  4985.2 1808.03
  4989.0 1808.53  5269.1 1813.05  5617.7 1814.87  5636.1 1816.01  5690.1 1815.08
  5731.9 1815.47  5792.9 1816.98  5814.1 1816.04  5954.8 1816.21  6609.9 1818.21
#Mann=9,-1,0
  3268.1   0.045       0  3352.6   0.035       0  3418.7   0.045       0
  4390.6   0.035       0  4696.3    0.07       0  4985.0    0.07       0
  4989.0    0.07       0  5269.1   0.035       0  5731.9   0.045       0
Bank Sta=4985,4989
Exp/Cntr=0.3,0.1

Type RM Length L Ch R = 1,8470,853,853,853
BEGIN DESCRIPTION:
Mapping XS 638df365
END DESCRIPTION:
XS GIS Cut Line= 2
      1453498.04      6918211.32      1454557.14      6916619.57
#Sta/Elev= 30
  4112.2 1812.04  4296.1 1811.42  4393.8 1810.91  4639.0 1810.41  4825.3 1808.63
  4870.4 1807.43  4906.5 1807.15  4933.5 1805.62  4948.6 1805.70  4957.0 1806.49
  4978.6 1805.44  4991.0 1804.22  4991.2 1803.72  4994.8 1803.72  4995.1 1804.22
  4999.7 1805.45  5014.7 1805.89  5101.1 1806.77  5113.9 1807.69  5148.6 1807.94
  5195.0 1809.39  5237.1 1809.29  5264.0 1809.85  5303.2 1809.79  5309.2 1810.38
  5360.3 1810.93  5411.4 1810.30  5425.4 1810.76  5665.9 1811.67  6024.1 1812.06
#Mann=8,-1,0
  4112.2    0.07       0  4296.1   0.035       0  4393.8    0.07       0
  4991.0    0.07       0  4995.1    0.07       0  5148.6   0.035       0
  5264.0    0.07       0  5665.9   0.035       0
Bank Sta=4991,4995.1
Exp/Cntr=0.3,0.1

Type RM Length L Ch R = 1,7617,1112,1112,1112
BEGIN DESCRIPTION:
Mapping XS b715ed11
END DESCRIPTION:
XS GIS Cut Line= 3
      1453770.56      6918452.84      1454625.24      6917982.14
      1455139.31      6916923.04
#Sta/Elev= 30
  4006.5 1810.74  4146.9 1810.11  4168.8 1810.20  4189.7 1809.78  4402.7 1808.73
  4440.6 1809.00  4571.3 1807.74  4639.5 1807.34  4662.3 1807.60  4755.9 1806.14
  4799.4 1805.87  4902.6 1803.65  4924.9 1803.52  4947.7 1804.00  4970.5 1803.29
  5009.1 1803.45  5013.1 1803.10  5013.4 1802.60  5017.3 1802.60  5017.6 1803.10
  5231.1 1807.23  5387.5 1807.54  5442.9 1808.46  5445.9 1808.51  5472.2 1808.83
  5894.7 1809.53  6024.9 1809.59  6115.2 1810.17  6120.7 1809.86  6159.5 1809.79
#Mann=9,-1,0
  4006.5    0.07       0  4146.9   0.035       0  4189.7    0.07       0
  5013.1    0.07       0  5017.6    0.07       0  5231.1   0.035       0
  5442.9    0.07       0  5445.9   0.035       0  5894.7    0.07       0
Bank Sta=5013.1,5017.6
Exp/Cntr=0.3,0.1

Type RM Length L Ch R = 1,6505,1321,1321,1321
BEGIN DESCRIPTION:
Mapping XS 220990ab
END DESCRIPTION:
XS GIS Cut Line= 3
      1455151.66      6919301.37      1455405.60      6918316.58
      1455238.56      6917313.81
#Sta/Elev= 30
  3944.8 1804.86  4413.0 1804.52  4485.3 1804.13  4535.3 1803.20  4567.9 1803.26
  4588.6 1803.99  4657.4 1802.50  4764.1 1801.48  4795.1 1800.65  4836.4 1800.76
  4942.1 1799.89  4950.0 1799.57  4956.1 1798.55  4956.5 1798.05  4960.5 1798.05
  4960.8 1798.55  4970.5 1799.42  5041.5 1800.23  5061.8 1799.11  5071.9 1799.79
  5102.3 1800.06  5117.6 1799.45  5193.5 1800.58  5284.8 1800.84  5377.1 1802.43
  5416.6 1803.23  5436.8 1804.21  5558.5 1805.26  5639.6 1806.89  5978.4 1808.63
#Mann=4,-1,0
  3944.8    0.07       0  4956.1    0.07       0  4960.8    0.07       0
  5377.1   0.035       0
Bank Sta=4956.1,4960.8
Exp/Cntr=0.3,0.1

Type RM Length L Ch R = 1,5184,48,48,48
BEGIN DESCRIPTION:
Mapping XS 27959807
END DESCRIPTION:
XS GIS Cut Line= 6
      1455634.77      6919152.67      1456297.45      6918576.70
      1456377.96      6918558.12      1456415.12      6918514.77
      1456408.93      6918409.48      1456223.13      6917616.76
#Sta/Elev= 30
  4005.6 1802.95  4221.5 1802.93  4654.5 1797.39  4810.3 1797.08  4831.1 1795.32
  4859.6 1797.09  4873.9 1801.19  4898.3 1801.49  4903.4 1799.07  4941.0 1800.45
  4946.2 1796.66  4971.2 1799.47  4978.9 1794.75  4985.4 1795.57  4999.7 1791.20
  5006.3 1792.79  5011.5 1790.60  5011.9 1790.10  5016.4 1790.60  5019.4 1792.73
  5040.1 1790.90  5070.2 1792.23  5107.9 1800.30  5112.9 1797.82  5127.0 1801.71
  5161.1 1803.73  5191.9 1798.71  5267.4 1799.72  5582.2 1803.95  5943.0 1805.90
#Mann=4,-1,0
  4005.6    0.07       0  5011.5    0.07       0  5016.4    0.07       0
  5267.4   0.035       0
Bank Sta=5011.5,5016.4
Exp/Cntr=0.3,0.1

Type RM Length L Ch R = 1,5136,25,25,25
BEGIN DESCRIPTION:
Mapping XS da40b1ef
END DESCRIPTION:
XS GIS Cut Line= 6
      1455634.75      6919196.05      1456322.22      6918601.48
      1456384.15      6918601.48      1456452.28      6918551.93
      1456470.86      6918471.42      1456272.68      6917598.18
#Sta/Elev= 30
  3968.7 1802.91  4180.6 1802.76  4215.8 1801.86  4400.1 1800.93  4535.0 1798.70
  4759.5 1796.81  4759.9 1796.31  4764.1 1796.31  4764.4 1796.81  4854.1 1797.16
  4877.6 1802.80  4950.4 1803.66  5055.8 1801.46  5060.9 1802.48  5068.9 1801.94
  5098.6 1801.96  5106.4 1801.18  5112.1 1802.23  5128.9 1802.86  5151.2 1801.70
  5198.8 1804.56  5211.2 1804.76  5219.2 1803.49  5229.4 1800.24  5239.6 1798.89
  5247.4 1798.75  5504.8 1802.77  5535.4 1802.62  5719.3 1804.66  6004.5 1805.88
#Mann=4,-1,0
  3968.7    0.07       0  4759.5    0.07       0  4764.4    0.07       0
  5247.4   0.035       0
Bank Sta=4759.5,4764.4
Exp/Cntr=0.3,0.1

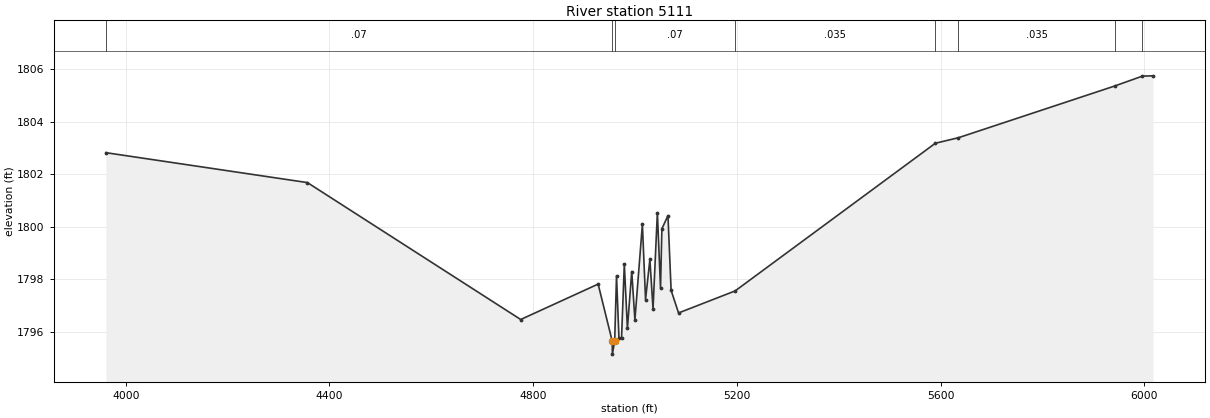
Type RM Length L Ch R = 1,5111,0,0,0
BEGIN DESCRIPTION:
Mapping XS d3427a41
END DESCRIPTION:
XS GIS Cut Line= 6
      1455640.97      6919220.80      1456303.64      6918663.41
      1456377.96      6918644.83      1456433.70      6918607.67
      1456520.41      6918490.00      1456322.51      6917611.81
#Sta/Elev= 30
  3961.1 1802.82  4356.7 1801.68  4775.5 1796.46  4927.5 1797.81  4955.1 1795.64
  4955.5 1795.14  4960.0 1795.64  4963.6 1798.12  4968.4 1795.76  4973.5 1795.76
  4978.9 1798.57  4985.0 1796.12  4993.5 1798.29  4999.7 1796.44  5014.4 1800.09
  5020.6 1797.22  5029.1 1798.75  5035.3 1796.87  5043.8 1800.53  5050.0 1797.66
  5052.7 1799.92  5064.6 1800.42  5070.8 1797.57  5085.4 1796.71  5196.5 1797.55
  5589.6 1803.18  5634.8 1803.39  5941.4 1805.36  5996.2 1805.74  6017.0 1805.75
#Mann=8,-1,0
  3961.1    0.07       0  4955.1    0.07       0  4960.0    0.07       0
  5196.5   0.035       0  5589.6    0.07       0  5634.8   0.035       0
  5941.4    0.07       0  5996.2   0.035       0
Bank Sta=4955.1,4960
Exp/Cntr=0.3,0.1

Chan Stop Cuts=-1