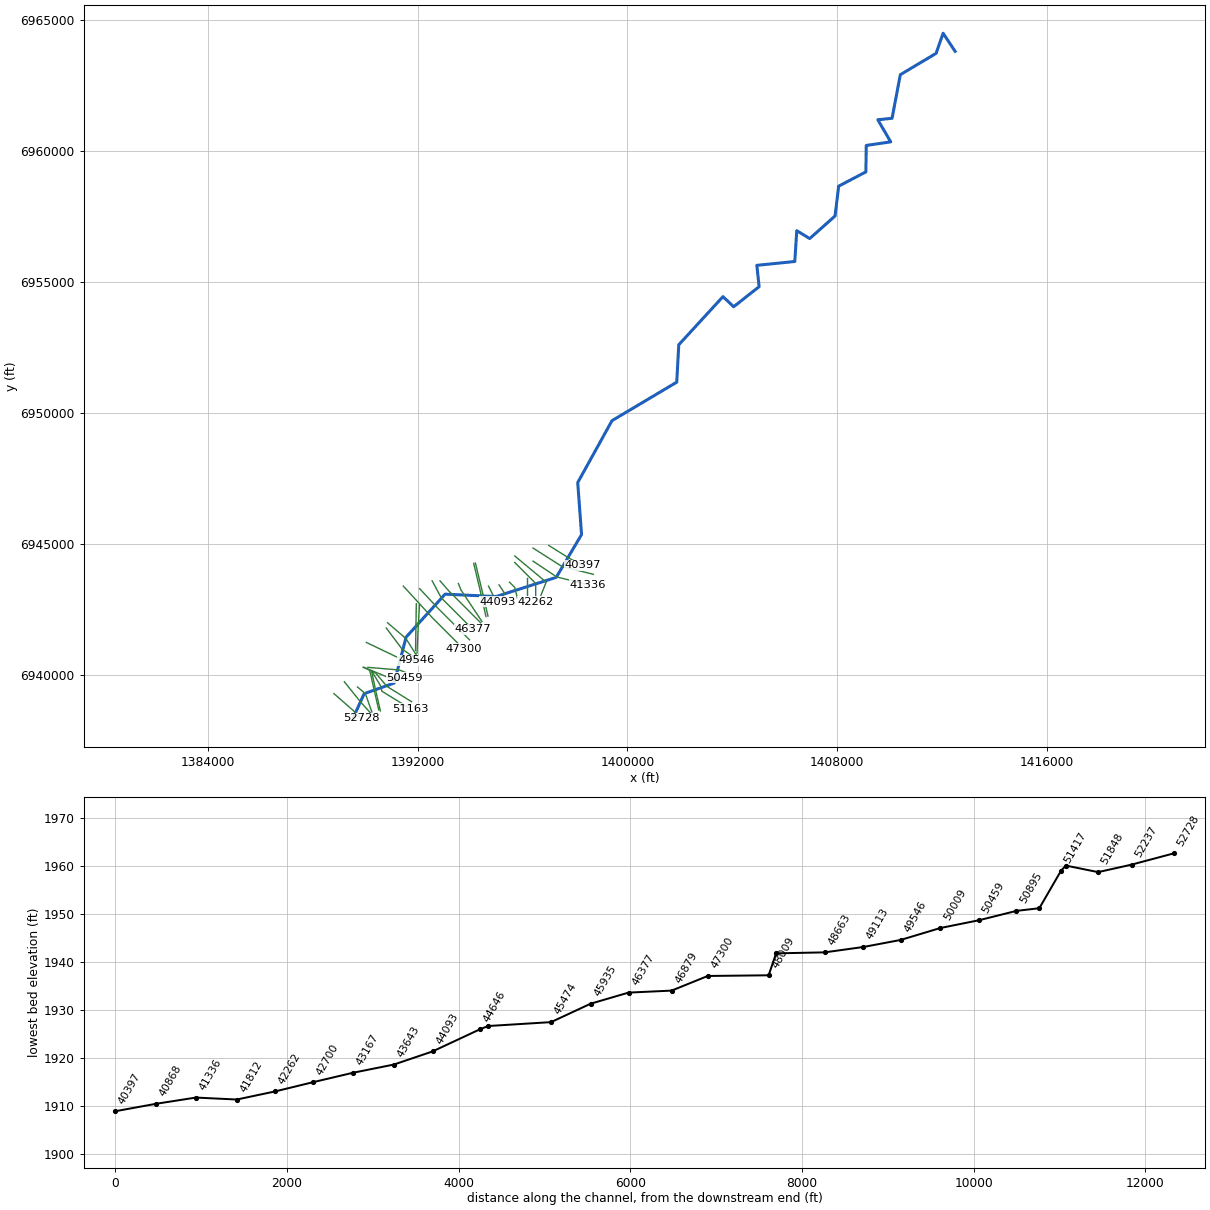
--- Sandy Creek.prj (project) ---

Proj Title=Sandy Creek Base Level Engineering
Current Plan=p01
Default Exp/Contr=0.3,0.1
English Units
Geom File=g01
Flow File=f01
Plan File=p01
BEGIN DESCRIPTION:
Sandy Creek
END DESCRIPTION:

--- Sandy Creek.p01 (plan) ---

Plan Title=Multiple Run
Short Identifier=Multiple
Geom File=g01
Flow File=f01
Subcritical Flow
K Sum by GR= 0
Std Step Tol= 0.01
Critical Tol= 0.01
Num of Std Step Trials= 20
Max Error Tol= 0.3
Flow Tol Ratio= 0.001
Split Flow NTrial= 30
Split Flow Tol= 0.02
Split Flow Ratio= 0.02
Log Output Level= 0
Friction Slope Method= 1
Unsteady Friction Slope Method= 2
Unsteady Bridges Friction Slope Method= 1
Parabolic Critical Depth
Global Vel Dist=  1 , 1 , 1
Global Log Level= 0
CheckData=True
Encroach Param= -1, 0, 0, 0
BEGIN DESCRIPTION:
Multiple Run
END DESCRIPTION:

--- Sandy Creek.f01 (steady flow) ---

Flow Title=Multiple
Number of Profiles=7
Profile Names=10-year,25-year,50-year,1pct_min,100-year,1pct_plu,500-year
River Rch & RM= Sandy Creek,Reach-1,52728
     352     508     642     404     805    1607    1283
River Rch & RM= Sandy Creek,Reach-1,50459
     531     785    1007     642    1281    2555    2099
River Rch & RM= Sandy Creek,Reach-1,50009
     623     926    1191     761    1518    3030    2501
River Rch & RM= Sandy Creek,Reach-1,46879
     748    1120    1449     930    1855    3702    3084
River Rch & RM= Sandy Creek,Reach-1,44742
     784    1174    1519     974    1943    3877    3228
River Rch & RM= Sandy Creek,Reach-1,41812
    1041    1573    2048    1320    2634    5255    4421
River Rch & RM= Sandy Creek,Reach-1,37440
    1053    1589    2067    1331    2656    5300    4450
River Rch & RM= Sandy Creek,Reach-1,35839
    1048    1579    2052    1320    2633    5254    4400
River Rch & RM= Sandy Creek,Reach-1,33952
    1059    1595    2071    1332    2657    5301    4434
River Rch & RM= Sandy Creek,Reach-1,30714
    1085    1635    2124    1365    2725    5436    4549
River Rch & RM= Sandy Creek,Reach-1,30260
    1196    1806    2349    1512    3016    6018    5045
River Rch & RM= Sandy Creek,Reach-1,27507
    1302    1965    2555    1643    3278    6540    5473
River Rch & RM= Sandy Creek,Reach-1,21535
    1305    1966    2552    1639    3270    6525    5445
River Rch & RM= Sandy Creek,Reach-1,17408
    1354    2039    2648    1700    3392    6767    5646
River Rch & RM= Sandy Creek,Reach-1,13914
    1391    2094    2718    1744    3480    6943    5787
River Rch & RM= Sandy Creek,Reach-1,9899
    1378    2069    2679    1715    3422    6827    5662
Boundary for River Rch & Prof#=Sandy Creek,Reach-1,1
Up Type=0
Dn Type=3
Dn Slope=0.005
Boundary for River Rch & Prof#=Sandy Creek,Reach-1,2
Up Type=0
Dn Type=3
Dn Slope=0.005
Boundary for River Rch & Prof#=Sandy Creek,Reach-1,3
Up Type=0
Dn Type=3
Dn Slope=0.005
Boundary for River Rch & Prof#=Sandy Creek,Reach-1,4
Up Type=0
Dn Type=3
Dn Slope=0.005
Boundary for River Rch & Prof#=Sandy Creek,Reach-1,5
Up Type=0
Dn Type=3
Dn Slope=0.005
Boundary for River Rch & Prof#=Sandy Creek,Reach-1,6
Up Type=0
Dn Type=3
Dn Slope=0.005
Boundary for River Rch & Prof#=Sandy Creek,Reach-1,7
Up Type=0
Dn Type=3
Dn Slope=0.005

--- Sandy Creek.g01 (geometry) ---

Geom Title=Existing Conditions

River Reach=Sandy Creek,Reach-1
Reach XY= 30
      1389555.00      6938388.00      1389960.41      6939282.82
      1391105.00      6939688.00      1391560.83      6941440.30
      1393048.55      6943080.25      1394994.50      6942989.22
      1397288.36      6943721.32      1398254.48      6945353.55
      1398108.46      6947336.50      1399415.43      6949698.52
      1401885.78      6951167.41      1401962.81      6952594.23
      1403648.93      6954430.51      1404058.21      6954045.87
      1405028.83      6954811.13      1404941.68      6955624.63
      1406388.59      6955771.20      1406464.99      6956947.95
      1406958.22      6956645.83      1407925.58      6957507.22
      1408062.64      6958644.45      1409101.48      6959189.48
      1409115.04      6960198.07      1410049.61      6960335.56
      1409555.55      6961177.36      1410100.03      6961235.41
      1410415.47      6962897.82      1411778.96      6963710.81
      1412048.25      6964478.90      1412505.00      6963788.00

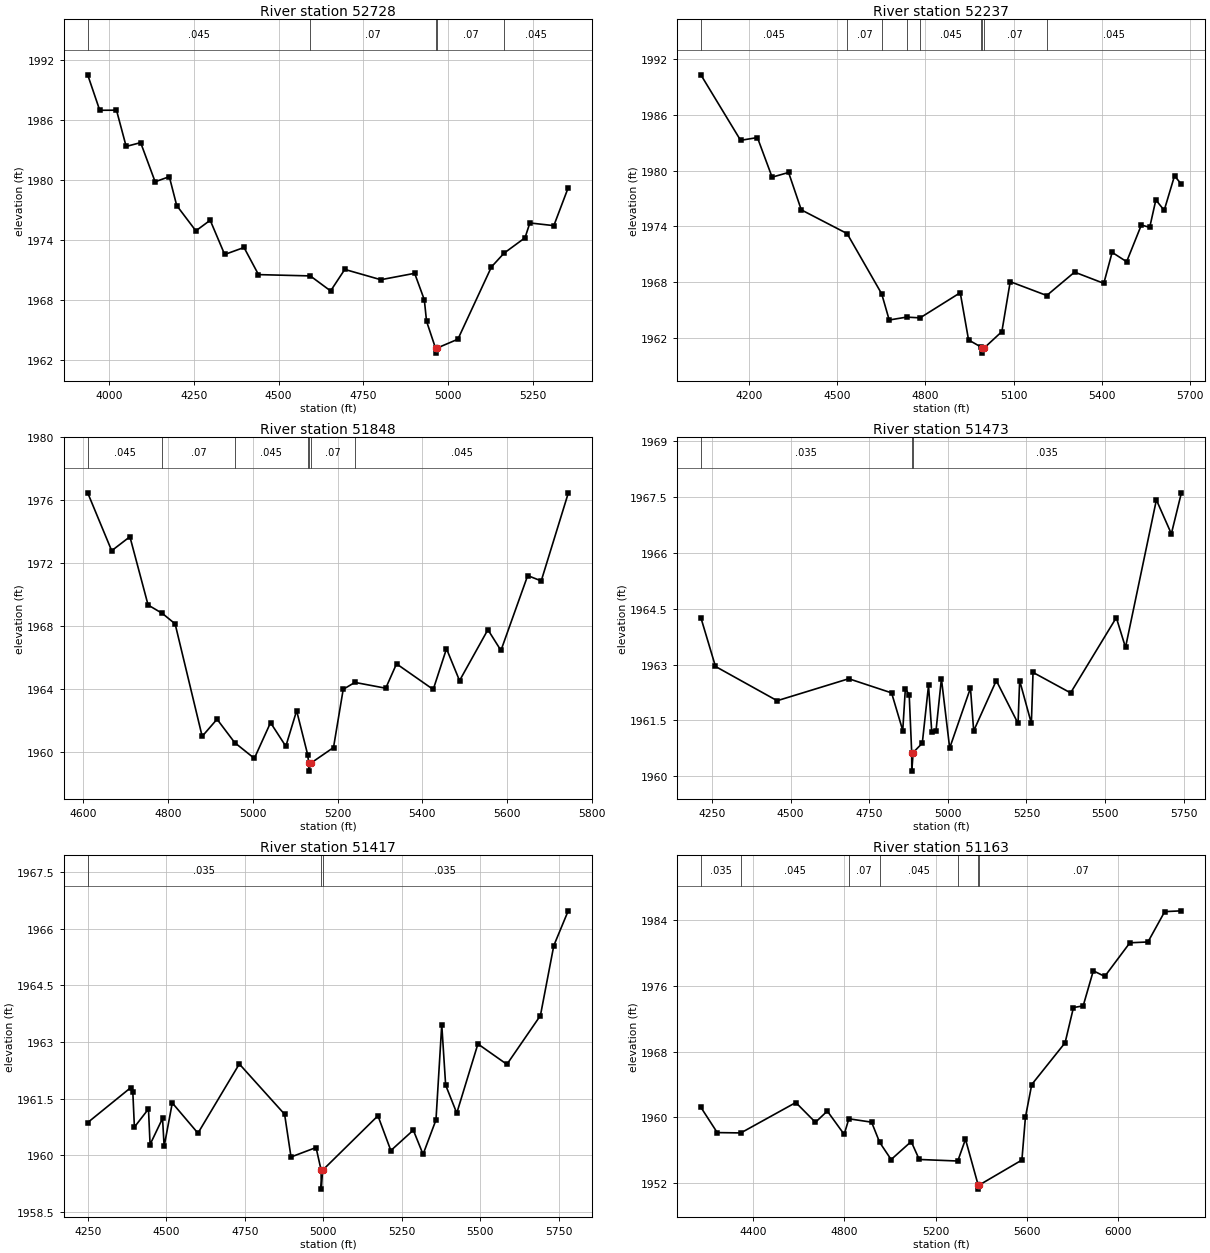
Type RM Length L Ch R = 1,52728,491,491,491
BEGIN DESCRIPTION:
Sandy Creek 71.0
END DESCRIPTION:
XS GIS Cut Line= 3
      1388805.04      6939287.97      1389605.00      6938588.00
      1389854.98      6938338.02
#Sta/Elev= 30
  3937.3 1990.47  3972.8 1986.93  4022.2 1986.94  4050.7 1983.32  4093.4 1983.70
  4136.1 1979.79  4177.9 1980.30  4199.7 1977.42  4256.2 1974.89  4298.4 1975.95
  4341.1 1972.53  4398.1 1973.23  4440.8 1970.52  4593.5 1970.39  4653.4 1968.89
  4695.1 1971.04  4801.4 1970.01  4901.1 1970.65  4929.6 1968.01  4936.2 1965.86
  4962.6 1963.18  4962.9 1962.68  4966.7 1963.18  5028.6 1964.07  5127.5 1971.29
  5164.6 1972.66  5226.5 1974.20  5240.7 1975.68  5311.4 1975.41  5353.8 1979.20
#Mann=5,-1,0
  3937.3   0.045       0  4593.5    0.07       0  4962.6    0.07       0
  4966.7    0.07       0  5164.6   0.045       0
Bank Sta=4962.6,4966.7
Exp/Cntr=0.3,0.1

Type RM Length L Ch R = 1,52237,389,389,389
BEGIN DESCRIPTION:
Sandy Creek 70.0
END DESCRIPTION:
XS GIS Cut Line= 3
      1389204.98      6939738.03      1389808.85      6938986.35
      1390257.61      6938487.90
#Sta/Elev= 30
  4035.8 1990.33  4171.0 1983.27  4228.2 1983.57  4278.2 1979.30  4334.2 1979.81
  4377.4 1975.78  4533.4 1973.22  4651.0 1966.73  4676.6 1963.91  4735.6 1964.22
  4781.7 1964.14  4918.3 1966.85  4946.6 1961.76  4988.8 1961.00  4993.7 1960.84
  4993.9 1960.34  4997.8 1960.84  5059.9 1962.66  5088.3 1968.04  5212.6 1966.55
  5307.3 1969.07  5406.7 1967.86  5435.1 1971.20  5484.4 1970.19  5534.5 1974.15
  5562.9 1973.89  5583.8 1976.85  5612.2 1975.73  5647.4 1979.45  5670.7 1978.53
#Mann=9,-1,0
  4035.8   0.045       0  4533.4    0.07       0  4651.0   0.045       0
  4735.6    0.07       0  4781.7   0.045       0  4988.8    0.07       0
  4993.7    0.07       0  4997.8    0.07       0  5212.6   0.045       0
Bank Sta=4993.7,4997.8
Exp/Cntr=0.3,0.1

Type RM Length L Ch R = 1,51848,375,375,375
BEGIN DESCRIPTION:
Sandy Creek 69.0
END DESCRIPTION:
XS GIS Cut Line= 3
      1389705.01      6939538.00      1390005.00      6939288.00
      1390255.00      6938588.01
#Sta/Elev= 30
  4610.3 1976.47  4666.9 1972.79  4709.9 1973.68  4752.8 1969.34  4786.7 1968.80
  4816.6 1968.14  4880.4 1960.99  4915.5 1962.08  4957.2 1960.59  5003.5 1959.59
  5041.7 1961.86  5077.8 1960.36  5103.3 1962.62  5129.5 1959.81  5131.7 1959.28
  5132.1 1958.78  5136.4 1959.28  5190.3 1960.28  5213.2 1963.98  5240.7 1964.42
  5313.5 1964.05  5339.0 1965.60  5425.6 1963.97  5456.9 1966.56  5487.7 1964.53
  5554.6 1967.77  5585.4 1966.45  5648.5 1971.21  5680.4 1970.87  5744.1 1976.44
#Mann=7,-1,0
  4610.3   0.045       0  4786.7    0.07       0  4957.2   0.045       0
  5129.5    0.07       0  5131.7   0.045       0  5136.4    0.07       0
  5240.7   0.045       0
Bank Sta=5131.7,5136.4
Exp/Cntr=0.3,0.1

Type RM Length L Ch R = 1,51473,56,56,56
BEGIN DESCRIPTION:
Mapping XS a2070c7e
END DESCRIPTION:
XS GIS Cut Line= 3
      1390179.27      6940154.92      1390347.86      6939390.70
      1390518.01      6938664.97
#Sta/Elev= 30
  4214.7 1964.26  4261.1 1962.95  4457.3 1962.03  4685.0 1962.62  4821.2 1962.24
  4856.7 1961.23  4864.9 1962.35  4877.2 1962.19  4885.1 1960.64  4885.4 1960.14
  4889.8 1960.64  4918.8 1960.89  4938.6 1962.44  4948.9 1961.20  4962.5 1961.23
  4979.6 1962.62  5005.9 1960.76  5072.0 1962.37  5082.2 1961.22  5154.1 1962.57
  5223.3 1961.42  5228.4 1962.57  5265.7 1961.42  5270.9 1962.79  5390.4 1962.24
  5535.8 1964.26  5565.0 1963.46  5663.2 1967.42  5710.8 1966.51  5742.7 1967.61
#Mann=3,-1,0
  4214.7   0.035       0  4885.1   0.035       0  4889.8   0.035       0
Bank Sta=4885.1,4889.8
Exp/Cntr=0.3,0.1

Type RM Length L Ch R = 1,51417,254,254,254
BEGIN DESCRIPTION:
Mapping XS 523fd01b
END DESCRIPTION:
XS GIS Cut Line= 3
      1390250.11      6940121.55      1390403.42      6939390.70
      1390580.25      6938627.89
#Sta/Elev= 30
  4250.1 1960.87  4386.6 1961.79  4393.7 1961.69  4398.8 1960.75  4443.6 1961.23
  4448.7 1960.29  4488.4 1960.98  4493.5 1960.24  4519.4 1961.39  4601.1 1960.59
  4732.8 1962.42  4877.0 1961.09  4897.4 1959.96  4977.1 1960.21  4993.3 1959.61
  4993.6 1959.11  4998.0 1959.61  5174.1 1961.05  5215.2 1960.13  5286.8 1960.67
  5317.8 1960.03  5358.9 1960.94  5377.3 1963.46  5389.7 1961.86  5425.1 1961.12
  5492.4 1962.95  5584.7 1962.41  5691.4 1963.70  5734.0 1965.55  5779.9 1966.47
#Mann=3,-1,0
  4250.1   0.035       0  4993.3   0.035       0  4998.0   0.035       0
Bank Sta=4993.3,4998
Exp/Cntr=0.3,0.1

Type RM Length L Ch R = 1,51163,268,268,268
BEGIN DESCRIPTION:
Mapping XS 94690f19
END DESCRIPTION:
XS GIS Cut Line= 4
      1390265.88      6940119.16      1390617.44      6939530.62
      1390630.46      6939382.18      1391713.81      6938715.50
#Sta/Elev= 30
  4170.8 1961.22  4242.6 1958.14  4346.0 1958.10  4587.0 1961.80  4673.0 1959.39
  4725.1 1960.76  4799.1 1957.92  4819.5 1959.82  4919.2 1959.41  4954.5 1956.96
  5004.9 1954.86  5092.9 1957.05  5128.1 1954.87  5297.1 1954.68  5330.9 1957.33
  5386.4 1951.76  5386.8 1951.26  5391.2 1951.76  5578.2 1954.80  5593.6 1960.00
  5621.3 1963.99  5767.5 1969.07  5804.2 1973.36  5846.8 1973.56  5891.3 1977.83
  5941.4 1977.15  6051.5 1981.24  6130.8 1981.34  6204.2 1985.03  6277.4 1985.13
#Mann=7,-1,0
  4170.8   0.035       0  4346.0   0.045       0  4819.5    0.07       0
  4954.5   0.045       0  5297.1    0.07       0  5386.4   0.045       0
  5391.2    0.07       0
Bank Sta=5386.4,5391.2
Exp/Cntr=0.3,0.1

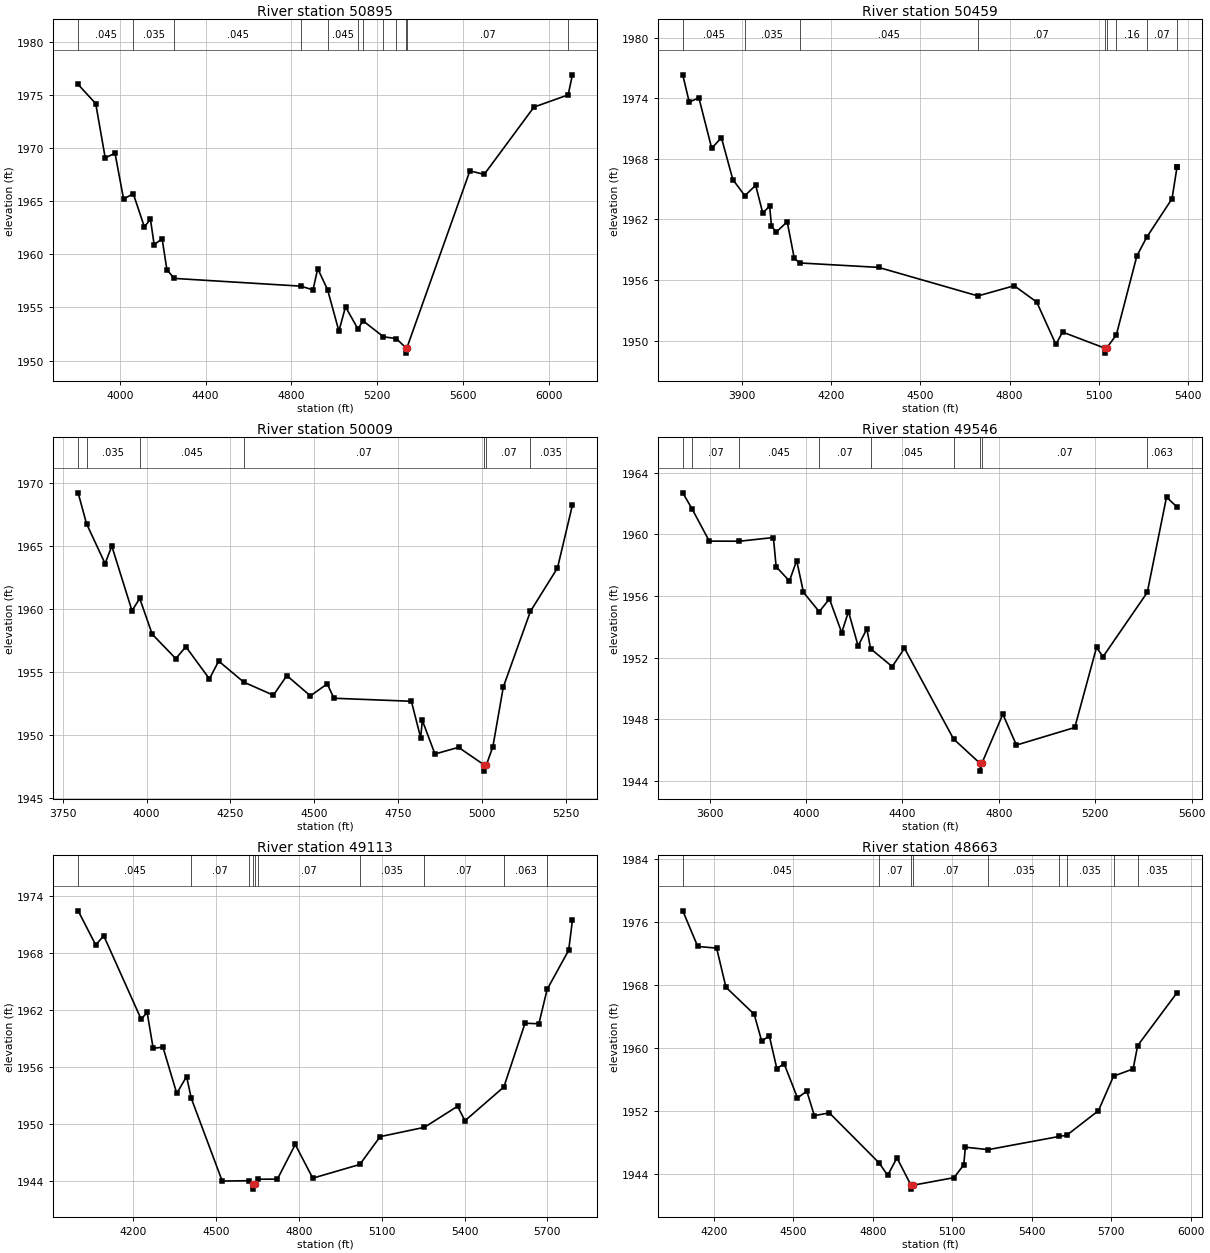
Type RM Length L Ch R = 1,50895,436,436,436
BEGIN DESCRIPTION:
Sandy Creek 67.0
END DESCRIPTION:
XS GIS Cut Line= 5
      1389920.87      6940294.46      1390404.80      6940066.60
      1390828.18      6939561.71      1391102.37      6939391.90
      1391771.01      6938977.80
#Sta/Elev= 30
  3806.2 1976.01  3888.1 1974.21  3932.4 1969.10  3978.0 1969.53  4018.1 1965.21
  4063.0 1965.73  4114.8 1962.59  4143.1 1963.32  4160.3 1960.93  4197.6 1961.46
  4219.7 1958.57  4253.5 1957.74  4843.7 1957.01  4900.4 1956.66  4922.5 1958.66
  4968.6 1956.66  5021.1 1952.78  5051.9 1955.06  5110.0 1952.97  5133.2 1953.75
  5228.6 1952.24  5288.6 1952.07  5333.1 1951.20  5333.4 1950.70  5337.9 1951.20
  5631.4 1967.87  5698.2 1967.54  5929.8 1973.88  6089.2 1975.03  6109.0 1976.92
#Mann=12,-1,0
  3806.2   0.045       0  4063.0   0.035       0  4253.5   0.045       0
  4843.7    0.07       0  4968.6   0.045       0  5110.0    0.07       0
  5133.2   0.045       0  5228.6    0.16       0  5288.6    0.07       0
  5333.1   0.045       0  5337.9    0.07       0  6089.2   0.035       0
Bank Sta=5333.1,5337.9
Exp/Cntr=0.3,0.1

Type RM Length L Ch R = 1,50459,450,450,450
BEGIN DESCRIPTION:
Sandy Creek 66.0
END DESCRIPTION:
XS GIS Cut Line= 3
      1389954.96      6940288.02      1391155.00      6939788.00
      1391504.96      6939887.99
#Sta/Elev= 30
  3699.8 1976.34  3721.5 1973.64  3754.0 1974.06  3797.3 1969.05  3829.8 1970.12
  3868.3 1965.96  3908.9 1964.35  3945.2 1965.39  3969.0 1962.64  3992.3 1963.33
  3998.3 1961.39  4014.0 1960.73  4051.4 1961.78  4075.2 1958.15  4093.4 1957.69
  4359.0 1957.25  4693.6 1954.42  4815.7 1955.43  4891.5 1953.81  4956.0 1949.61
  4978.2 1950.84  5119.9 1949.25  5120.4 1948.75  5126.8 1949.25  5159.4 1950.56
  5228.6 1958.39  5261.5 1960.23  5346.9 1964.06  5363.7 1967.19  5363.8 1967.19
#Mann=9,-1,0
  3699.8   0.045       0  3908.9   0.035       0  4093.4   0.045       0
  4693.6    0.07       0  5119.9    0.07       0  5126.8    0.07       0
  5159.4    0.16       0  5261.5    0.07       0  5363.7   0.035       0
Bank Sta=5119.9,5126.8
Exp/Cntr=0.3,0.1

Type RM Length L Ch R = 1,50009,463,463,463
BEGIN DESCRIPTION:
Sandy Creek 65.0
END DESCRIPTION:
XS GIS Cut Line= 3
      1390104.96      6940288.00      1391305.00      6940188.00
      1391555.04      6940087.99
#Sta/Elev= 30
  3795.8 1969.24  3820.8 1966.79  3876.1 1963.62  3896.2 1965.01  3956.4 1959.87
  3979.4 1960.85  4016.6 1958.01  4086.8 1956.07  4117.0 1957.01  4187.2 1954.46
  4214.8 1955.87  4289.6 1954.20  4377.9 1953.16  4418.0 1954.72  4488.2 1953.11
  4538.4 1954.06  4558.5 1952.92  4789.3 1952.68  4816.9 1949.78  4821.9 1951.16
  4859.5 1948.49  4929.8 1949.02  5005.9 1947.63  5006.4 1947.13  5012.9 1947.63
  5032.3 1949.08  5063.3 1953.81  5144.1 1959.82  5224.8 1963.27  5269.3 1968.26
#Mann=7,-1,0
  3795.8   0.045       0  3820.8   0.035       0  3979.4   0.045       0
  4289.6    0.07       0  5005.9    0.07       0  5012.9    0.07       0
  5144.1   0.035       0
Bank Sta=5005.9,5012.9
Exp/Cntr=0.3,0.1

Type RM Length L Ch R = 1,49546,433,433,433
BEGIN DESCRIPTION:
Sandy Creek 64.0
END DESCRIPTION:
XS GIS Cut Line= 3
      1390045.74      6941237.94      1391405.00      6940588.00
      1391948.57      6940553.89
#Sta/Elev= 30
  3488.1 1962.69  3526.2 1961.66  3598.1 1959.56  3722.9 1959.55  3864.2 1959.79
  3875.6 1957.90  3930.7 1956.97  3960.8 1958.30  3989.0 1956.24  4054.4 1954.98
  4096.8 1955.81  4147.7 1953.62  4175.9 1954.99  4215.7 1952.76  4252.1 1953.86
  4267.6 1952.58  4357.3 1951.42  4408.2 1952.61  4612.1 1946.72  4722.2 1945.14
  4722.7 1944.64  4729.2 1945.14  4816.4 1948.33  4872.8 1946.33  5115.0 1947.47
  5205.2 1952.66  5232.3 1952.06  5415.8 1956.23  5495.7 1962.41  5539.4 1961.77
#Mann=9,-1,0
  3488.1   0.035       0  3526.2    0.07       0  3722.9   0.045       0
  4054.4    0.07       0  4267.6   0.045       0  4612.1    0.07       0
  4722.2    0.07       0  4729.2    0.07       0  5415.8   0.063       0
Bank Sta=4722.2,4729.2
Exp/Cntr=0.3,0.1

Type RM Length L Ch R = 1,49113,450,450,450
BEGIN DESCRIPTION:
Sandy Creek 63.0
END DESCRIPTION:
XS GIS Cut Line= 3
      1390804.97      6941788.04      1391405.00      6940988.00
      1392054.99      6940538.01
#Sta/Elev= 30
  4000.1 1972.40  4063.7 1968.82  4092.9 1969.78  4228.3 1961.03  4250.1 1961.73
  4272.0 1957.96  4307.4 1958.09  4357.4 1953.23  4392.9 1955.00  4410.1 1952.71
  4522.0 1944.03  4619.5 1944.06  4633.0 1943.68  4633.5 1943.18  4640.2 1943.68
  4650.2 1944.22  4722.0 1944.23  4786.6 1947.87  4850.1 1944.33  5020.6 1945.77
  5094.1 1948.69  5254.5 1949.67  5374.5 1951.88  5401.5 1950.36  5542.5 1953.91
  5619.1 1960.60  5669.1 1960.54  5699.3 1964.16  5777.2 1968.26  5790.7 1971.40
#Mann=10,-1,0
  4000.1   0.045       0  4410.1    0.07       0  4619.5   0.045       0
  4633.0    0.07       0  4640.2   0.045       0  4650.2    0.07       0
  5020.6   0.035       0  5254.5    0.07       0  5542.5   0.063       0
  5699.3   0.035       0
Bank Sta=4633,4640.2
Exp/Cntr=0.3,0.1

Type RM Length L Ch R = 1,48663,567,567,567
BEGIN DESCRIPTION:
Sandy Creek 62.0
END DESCRIPTION:
XS GIS Cut Line= 3
      1390855.03      6941987.97      1391555.00      6941388.00
      1392054.99      6940588.01
#Sta/Elev= 30
  4083.0 1977.43  4139.5 1972.90  4210.8 1972.69  4245.9 1967.72  4352.4 1964.29
  4380.9 1960.87  4409.5 1961.55  4438.0 1957.38  4465.5 1958.00  4515.9 1953.65
  4551.1 1954.51  4579.6 1951.40  4636.1 1951.75  4824.3 1945.38  4856.2 1943.81
  4891.3 1946.03  4944.3 1942.56  4944.8 1942.06  4952.5 1942.56  5106.9 1943.52
  5143.5 1945.16  5149.4 1947.39  5235.7 1947.08  5504.4 1948.76  5532.2 1948.91
  5651.7 1952.03  5708.5 1956.41  5782.6 1957.34  5799.7 1960.30  5948.3 1967.03
#Mann=9,-1,0
  4083.0   0.045       0  4824.3    0.07       0  4944.3    0.07       0
  4952.5    0.07       0  5235.7   0.035       0  5504.4    0.07       0
  5532.2   0.035       0  5708.5   0.063       0  5799.7   0.035       0
Bank Sta=4944.3,4952.5
Exp/Cntr=0.3,0.1

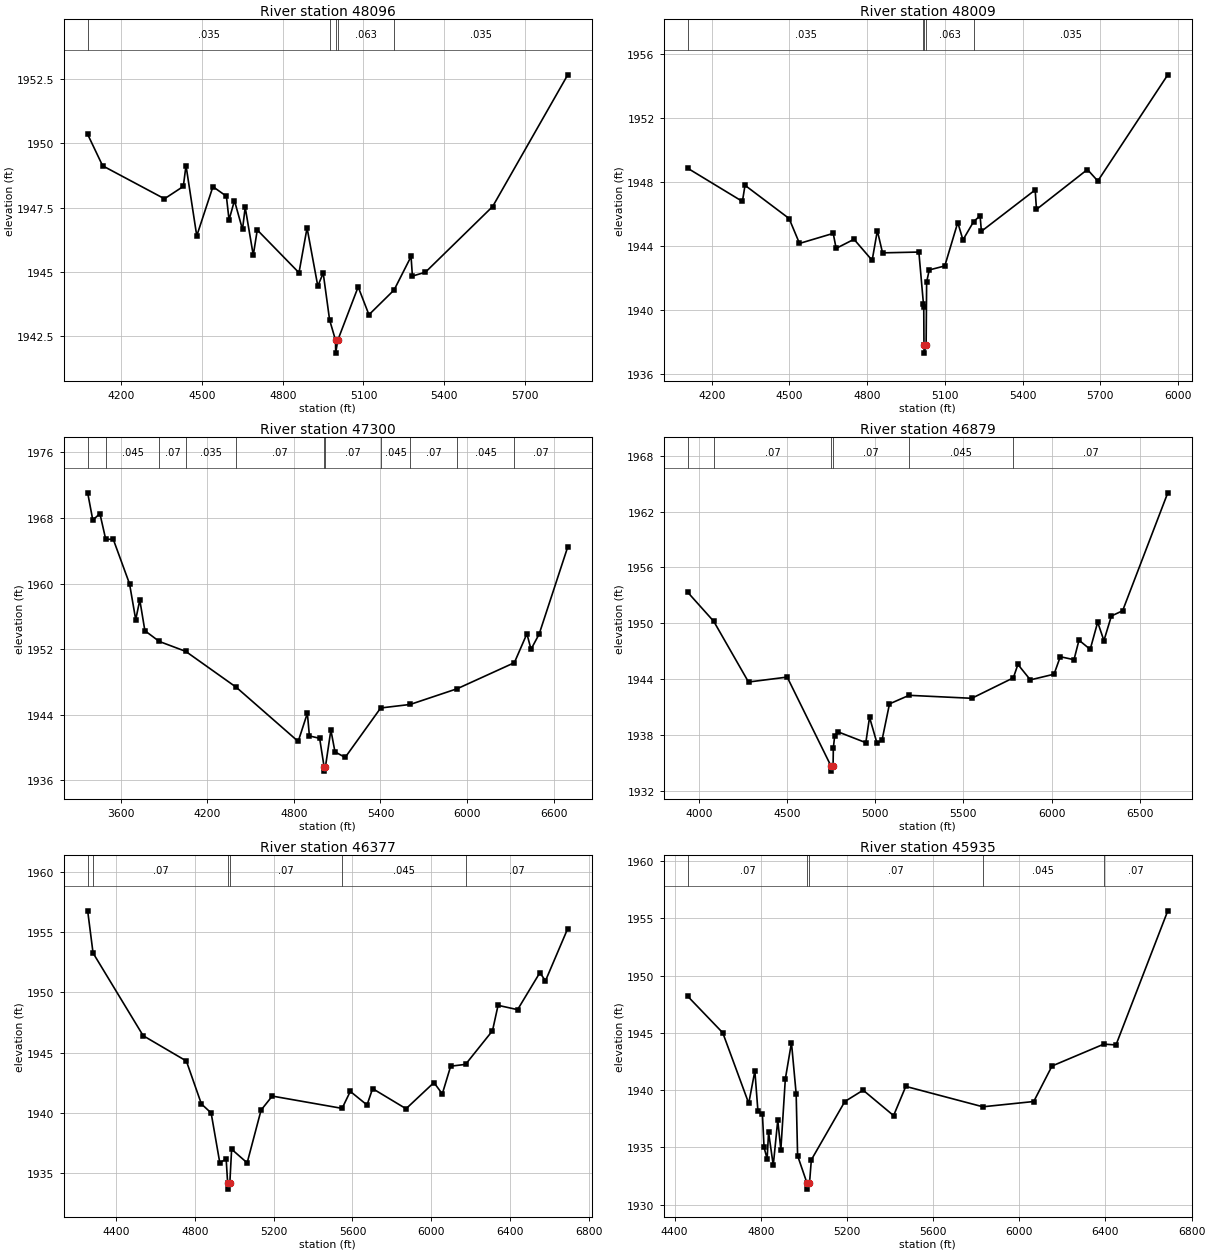
Type RM Length L Ch R = 1,48096,87,87,87
BEGIN DESCRIPTION:
Mapping XS 89d94516
END DESCRIPTION:
XS GIS Cut Line= 3
      1391952.03      6942713.57      1391934.67      6941803.89
      1391920.78      6940928.85
#Sta/Elev= 30
  4074.6 1950.34  4130.2 1949.12  4360.2 1947.84  4430.2 1948.32  4440.2 1949.13
  4480.2 1946.40  4540.3 1948.31  4590.3 1947.94  4600.3 1947.02  4620.3 1947.77
  4650.3 1946.65  4660.3 1947.51  4690.3 1945.65  4705.2 1946.63  4860.3 1944.97
  4890.3 1946.71  4930.3 1944.45  4950.3 1944.96  4974.1 1943.14  4996.2 1942.35
  4996.7 1941.85  5004.5 1942.35  5080.3 1944.42  5120.4 1943.34  5213.9 1944.30
  5277.0 1945.60  5282.0 1944.84  5330.4 1944.99  5580.4 1947.54  5859.6 1952.65
#Mann=5,-1,0
  4074.6   0.035       0  4974.1   0.063       0  4996.2   0.063       0
  5004.5   0.063       0  5213.9   0.035       0
Bank Sta=4996.2,5004.5
Exp/Cntr=0.3,0.1

Type RM Length L Ch R = 1,48009,709,709,709
BEGIN DESCRIPTION:
Mapping XS 152f4296
END DESCRIPTION:
XS GIS Cut Line= 3
      1392073.56      6942678.87      1392021.47      6941796.95
      1391976.33      6940828.16
#Sta/Elev= 30
  4107.0 1948.86  4318.2 1946.78  4328.3 1947.79  4498.5 1945.71  4538.6 1944.15
  4668.8 1944.78  4680.0 1943.84  4749.0 1944.41  4819.1 1943.09  4839.1 1944.95
  4859.2 1943.56  4999.4 1943.61  5017.0 1940.38  5018.3 1940.16  5019.1 1937.78
  5019.6 1937.28  5027.4 1937.78  5029.4 1941.73  5039.5 1942.49  5099.5 1942.74
  5149.6 1945.46  5169.6 1944.37  5210.9 1945.52  5235.8 1945.88  5240.8 1944.91
  5448.4 1947.50  5453.4 1946.28  5650.1 1948.78  5690.2 1948.06  5960.3 1954.71
#Mann=5,-1,0
  4107.0   0.035       0  5017.0   0.063       0  5019.1   0.035       0
  5027.4   0.063       0  5210.9   0.035       0
Bank Sta=5019.1,5027.4
Exp/Cntr=0.3,0.1

Type RM Length L Ch R = 1,47300,421,421,421
BEGIN DESCRIPTION:
Sandy Creek 59.0
END DESCRIPTION:
XS GIS Cut Line= 3
      1391455.00      6943388.00      1392555.00      6942188.00
      1393754.98      6940988.02
#Sta/Elev= 30
  3372.1 1971.07  3407.6 1967.75  3456.9 1968.53  3497.4 1965.38  3548.8 1965.43
  3662.2 1959.97  3704.8 1955.61  3733.1 1958.01  3768.3 1954.26  3868.0 1952.95
  4051.1 1951.74  4401.5 1947.36  4830.1 1940.76  4893.6 1944.20  4907.8 1941.43
  4978.7 1941.14  5009.7 1937.64  5010.2 1937.14  5018.6 1937.64  5056.5 1942.15
  5084.8 1939.49  5155.5 1938.81  5401.4 1944.84  5605.9 1945.27  5931.8 1947.19
  6327.2 1950.36  6414.2 1953.89  6442.5 1951.99  6499.0 1953.85  6697.0 1964.48
#Mann=11,-1,0
  3372.1   0.035       0  3497.4   0.045       0  3868.0    0.07       0
  4051.1   0.035       0  4401.5    0.07       0  5009.7    0.07       0
  5018.6    0.07       0  5401.4   0.045       0  5605.9    0.07       0
  5931.8   0.045       0  6327.2    0.07       0
Bank Sta=5009.7,5018.6
Exp/Cntr=0.3,0.1

Type RM Length L Ch R = 1,46879,502,502,502
BEGIN DESCRIPTION:
Sandy Creek 58.0
END DESCRIPTION:
XS GIS Cut Line= 3
      1392078.61      6943289.39      1392778.61      6942539.39
      1393978.63      6941339.37
#Sta/Elev= 30
  3936.1 1953.32  4084.0 1950.19  4281.0 1943.67  4500.4 1944.20  4750.1 1934.59
  4750.6 1934.09  4760.7 1934.59  4762.2 1936.58  4769.5 1937.83  4790.6 1938.30
  4946.4 1937.15  4967.5 1939.88  5009.9 1937.09  5038.2 1937.41  5080.7 1941.32
  5191.8 1942.24  5547.3 1941.92  5783.2 1944.12  5809.0 1945.56  5879.7 1943.90
  6014.0 1944.51  6049.4 1946.39  6127.2 1946.07  6155.5 1948.17  6219.1 1947.18
  6261.5 1950.10  6296.9 1948.12  6339.3 1950.77  6402.9 1951.33  6659.1 1964.01
#Mann=6,-1,0
  3936.1   0.035       0  4084.0    0.07       0  4750.1    0.07       0
  4760.7    0.07       0  5191.8   0.045       0  5783.2    0.07       0
Bank Sta=4750.1,4760.7
Exp/Cntr=0.3,0.1

Type RM Length L Ch R = 1,46377,442,442,442
BEGIN DESCRIPTION:
Sandy Creek 57.0
END DESCRIPTION:
XS GIS Cut Line= 3
      1392554.99      6943588.02      1392905.00      6942938.00
      1394104.98      6941738.02
#Sta/Elev= 30
  4256.9 1956.76  4284.2 1953.26  4538.4 1946.40  4757.5 1944.30  4833.7 1940.74
  4883.2 1939.99  4927.0 1935.87  4959.5 1936.16  4966.9 1934.17  4967.4 1933.67
  4978.0 1934.17  4987.1 1936.98  5065.9 1935.85  5136.6 1940.23  5193.2 1941.39
  5547.5 1940.37  5589.1 1941.78  5674.0 1940.65  5702.3 1942.01  5872.0 1940.34
  6013.4 1942.51  6055.8 1941.57  6098.3 1943.87  6173.8 1944.02  6310.4 1946.81
  6338.7 1948.92  6437.7 1948.56  6550.8 1951.63  6579.1 1950.95  6692.2 1955.29
#Mann=6,-1,0
  4256.9   0.035       0  4284.2    0.07       0  4966.9    0.07       0
  4978.0    0.07       0  5547.5   0.045       0  6173.8    0.07       0
Bank Sta=4966.9,4978
Exp/Cntr=0.3,0.1

Type RM Length L Ch R = 1,45935,461,461,461
BEGIN DESCRIPTION:
Sandy Creek 56.0
END DESCRIPTION:
XS GIS Cut Line= 3
      1392854.97      6943588.03      1393205.00      6943188.00
      1394405.00      6941988.00
#Sta/Elev= 30
  4460.5 1948.20  4623.3 1945.01  4743.9 1938.85  4772.3 1941.68  4786.6 1938.16
  4807.4 1937.90  4815.0 1935.00  4829.3 1934.00  4835.9 1936.33  4857.7 1933.44
  4878.6 1937.38  4892.9 1934.79  4913.7 1940.97  4942.2 1944.15  4964.0 1939.69
  4970.7 1934.28  5014.8 1931.86  5015.3 1931.36  5025.9 1931.86  5034.5 1933.92
  5190.0 1939.01  5274.9 1940.00  5416.3 1937.78  5472.9 1940.33  5830.7 1938.55
  6066.9 1939.01  6151.7 1942.11  6392.1 1944.02  6448.7 1943.95  6689.1 1955.66
#Mann=5,-1,0
  4460.5    0.07       0  5014.8    0.07       0  5025.9    0.07       0
  5830.7   0.045       0  6392.1    0.07       0
Bank Sta=5014.8,5025.9
Exp/Cntr=0.3,0.1

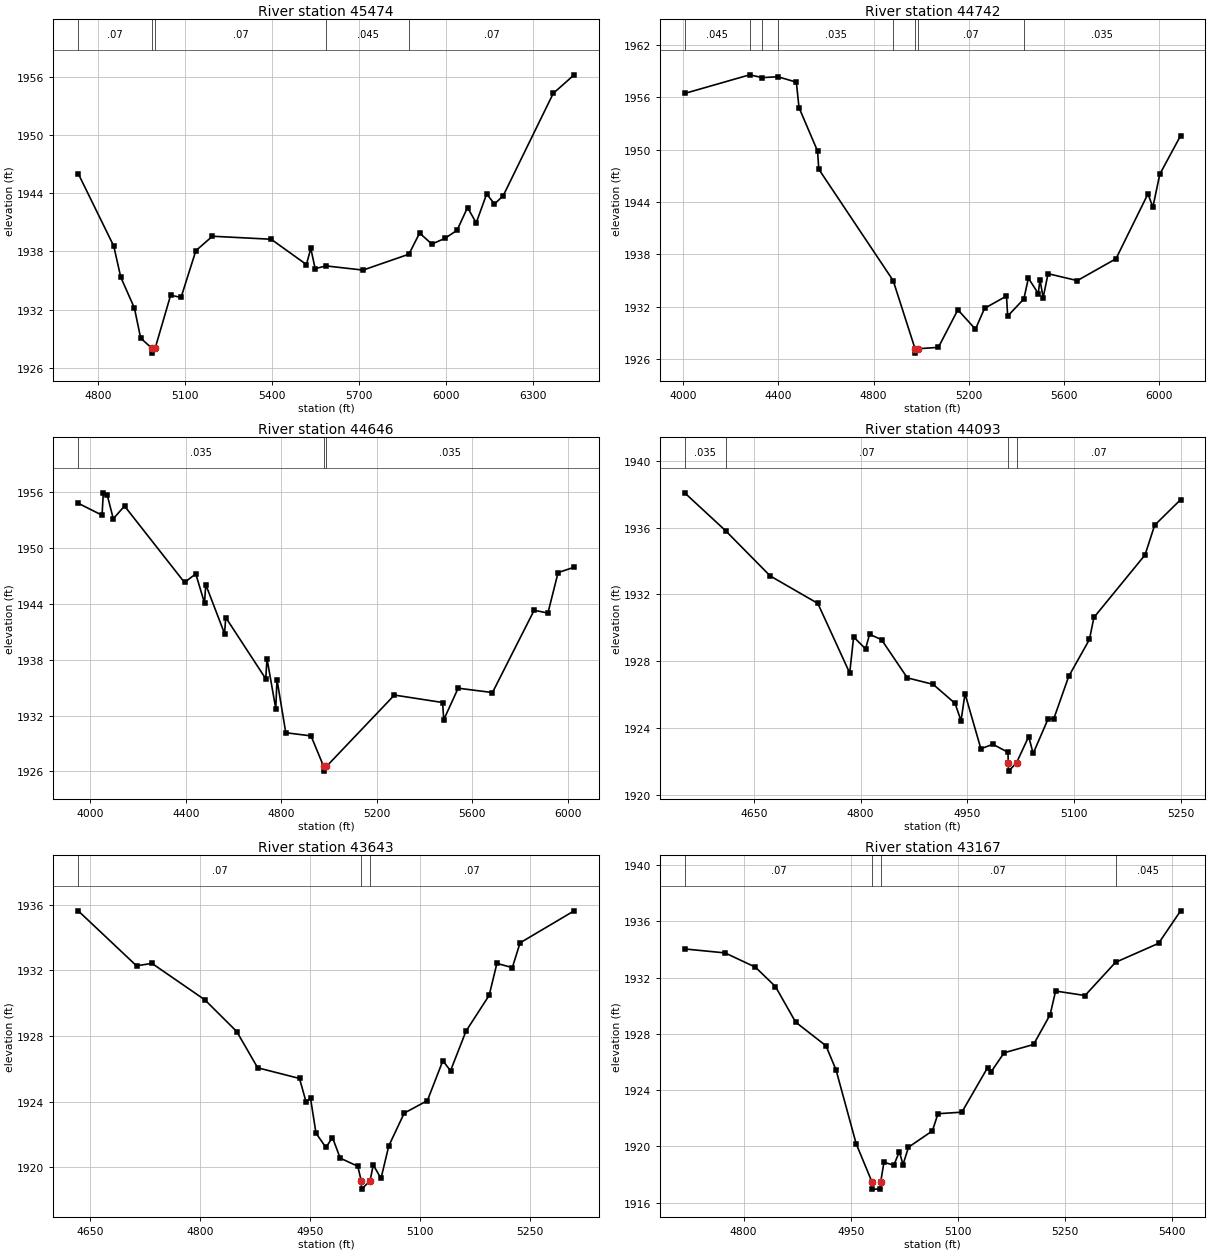
Type RM Length L Ch R = 1,45474,732,732,732
BEGIN DESCRIPTION:
Sandy Creek 55.0
END DESCRIPTION:
XS GIS Cut Line= 3
      1393554.98      6943488.04      1393655.00      6943238.00
      1394454.98      6942038.02
#Sta/Elev= 30
  4730.7 1946.03  4853.3 1938.56  4877.5 1935.35  4924.6 1932.17  4946.2 1929.07
  4984.9 1928.02  4985.4 1927.52  4996.2 1928.02  5049.6 1933.49  5085.6 1933.26
  5136.7 1938.08  5193.8 1939.57  5396.6 1939.26  5518.3 1936.65  5533.3 1938.32
  5548.4 1936.23  5586.1 1936.51  5713.6 1936.08  5872.0 1937.72  5908.9 1939.90
  5951.0 1938.76  5996.0 1939.35  6038.1 1940.18  6074.2 1942.53  6104.2 1940.95
  6140.3 1943.93  6167.3 1942.89  6197.4 1943.75  6370.1 1954.30  6442.2 1956.21
#Mann=5,-1,0
  4730.7    0.07       0  4984.9    0.07       0  4996.2    0.07       0
  5586.1   0.045       0  5872.0    0.07       0
Bank Sta=4984.9,4996.2
Exp/Cntr=0.3,0.1

Type RM Length L Ch R = 1,44742,96,96,96
BEGIN DESCRIPTION:
Mapping XS 36f3d155
END DESCRIPTION:
XS GIS Cut Line= 3
      1394139.52      6944255.32      1394365.22      6943314.31
      1394608.27      6942224.07
#Sta/Elev= 30
  4005.8 1956.43  4278.9 1958.56  4331.6 1958.24  4397.9 1958.34  4475.2 1957.72
  4486.4 1954.81  4564.4 1949.83  4569.5 1947.76  4882.2 1935.01  4974.2 1927.21
  4974.7 1926.71  4985.7 1927.21  5072.2 1927.37  5154.1 1931.67  5228.1 1929.45
  5266.5 1931.84  5358.5 1933.24  5363.6 1930.95  5431.5 1932.91  5450.6 1935.29
  5492.2 1933.53  5499.2 1935.11  5512.7 1933.06  5533.2 1935.80  5656.2 1935.01
  5818.8 1937.51  5953.3 1944.94  5973.8 1943.41  6003.0 1947.19  6090.5 1951.60
#Mann=8,-1,0
  4005.8   0.045       0  4278.9   0.035       0  4331.6   0.045       0
  4397.9   0.035       0  4882.2    0.07       0  4974.2    0.07       0
  4985.7    0.07       0  5431.5   0.035       0
Bank Sta=4974.2,4985.7
Exp/Cntr=0.3,0.1

Type RM Length L Ch R = 1,44646,553,553,553
BEGIN DESCRIPTION:
Mapping XS df9024d1
END DESCRIPTION:
XS GIS Cut Line= 3
      1394205.50      6944265.69      1394448.56      6943258.76
      1394684.68      6942244.84
#Sta/Elev= 30
  3949.8 1954.84  4049.7 1953.55  4054.8 1955.96  4070.9 1955.76  4096.7 1953.17
  4143.7 1954.54  4395.0 1946.32  4442.1 1947.25  4478.8 1944.10  4483.9 1946.10
  4562.6 1940.82  4567.7 1942.55  4735.2 1935.96  4740.4 1938.13  4777.1 1932.75
  4782.3 1935.87  4819.0 1930.16  4924.7 1929.82  4977.7 1926.53  4978.2 1926.03
  4989.2 1926.53  5273.9 1934.21  5475.6 1933.41  5480.7 1931.56  5540.9 1934.95
  5684.6 1934.48  5859.2 1943.33  5916.8 1943.03  5959.4 1947.38  6026.7 1947.96
#Mann=3,-1,0
  3949.8   0.035       0  4977.7   0.035       0  4989.2   0.035       0
Bank Sta=4977.7,4989.2
Exp/Cntr=0.3,0.1

Type RM Length L Ch R = 1,44093,450,450,450
BEGIN DESCRIPTION:
Sandy Creek 52.0
END DESCRIPTION:
XS GIS Cut Line= 3
      1394705.02      6943387.97      1394905.00      6942988.00
      1395055.02      6942787.98
#Sta/Elev= 30
  4552.7 1938.09  4610.2 1935.82  4672.9 1933.11  4739.9 1931.46  4784.7 1927.29
  4790.2 1929.45  4807.0 1928.74  4812.6 1929.61  4829.4 1929.29  4865.7 1927.00
  4902.0 1926.61  4932.8 1925.47  4941.2 1924.43  4946.8 1926.05  4969.1 1922.75
  4985.9 1923.02  5007.2 1922.54  5007.6 1921.91  5008.1 1921.41  5019.2 1921.91
  5036.3 1923.48  5042.6 1922.47  5063.4 1924.52  5071.7 1924.56  5092.6 1927.09
  5121.7 1929.30  5128.0 1930.62  5199.9 1934.37  5213.4 1936.15  5249.9 1937.68
#Mann=4,-1,0
  4552.7   0.035       0  4610.2    0.07       0  5007.6    0.07       0
  5019.2    0.07       0
Bank Sta=5007.6,5019.2
Exp/Cntr=0.3,0.1

Type RM Length L Ch R = 1,43643,476,476,476
BEGIN DESCRIPTION:
Sandy Creek 51.0
END DESCRIPTION:
XS GIS Cut Line= 3
      1395105.01      6943437.99      1395305.00      6943138.00
      1395204.99      6942837.97
#Sta/Elev= 30
  4633.5 1935.63  4713.1 1932.28  4734.1 1932.43  4806.3 1930.21  4849.8 1928.28
  4878.4 1926.07  4935.5 1925.42  4944.5 1923.98  4950.5 1924.22  4958.0 1922.09
  4971.5 1921.22  4980.5 1921.82  4991.0 1920.57  5015.1 1920.07  5019.7 1919.18
  5020.2 1918.68  5031.7 1919.18  5036.2 1920.15  5046.7 1919.33  5057.3 1921.31
  5078.4 1923.31  5110.0 1924.07  5131.1 1926.50  5141.6 1925.89  5162.7 1928.30
  5194.3 1930.48  5204.9 1932.43  5225.9 1932.17  5236.5 1933.68  5310.3 1935.63
#Mann=3,-1,0
  4633.5    0.07       0  5019.7    0.07       0  5031.7    0.07       0
Bank Sta=5019.7,5031.7
Exp/Cntr=0.3,0.1

Type RM Length L Ch R = 1,43167,467,467,467
BEGIN DESCRIPTION:
Sandy Creek 50.0
END DESCRIPTION:
XS GIS Cut Line= 3
      1395505.02      6943537.98      1395705.00      6943338.00
      1395804.99      6942938.02
#Sta/Elev= 30
  4717.3 1934.04  4773.8 1933.76  4816.3 1932.75  4844.5 1931.37  4872.8 1928.84
  4915.3 1927.16  4929.4 1925.45  4957.7 1920.19  4979.9 1917.47  4980.4 1916.97
  4991.5 1916.97  4992.0 1917.47  4996.6 1918.88  5010.4 1918.67  5018.2 1919.63
  5023.3 1918.71  5031.0 1919.95  5064.5 1921.11  5072.3 1922.33  5105.8 1922.44
  5141.8 1925.60  5147.0 1925.32  5165.0 1926.66  5206.3 1927.25  5229.5 1929.37
  5237.2 1931.05  5278.4 1930.73  5321.2 1933.09  5381.5 1934.44  5412.4 1936.75
#Mann=4,-1,0
  4717.3    0.07       0  4979.9    0.07       0  4992.0    0.07       0
  5321.2   0.045       0
Bank Sta=4979.9,4992
Exp/Cntr=0.3,0.1

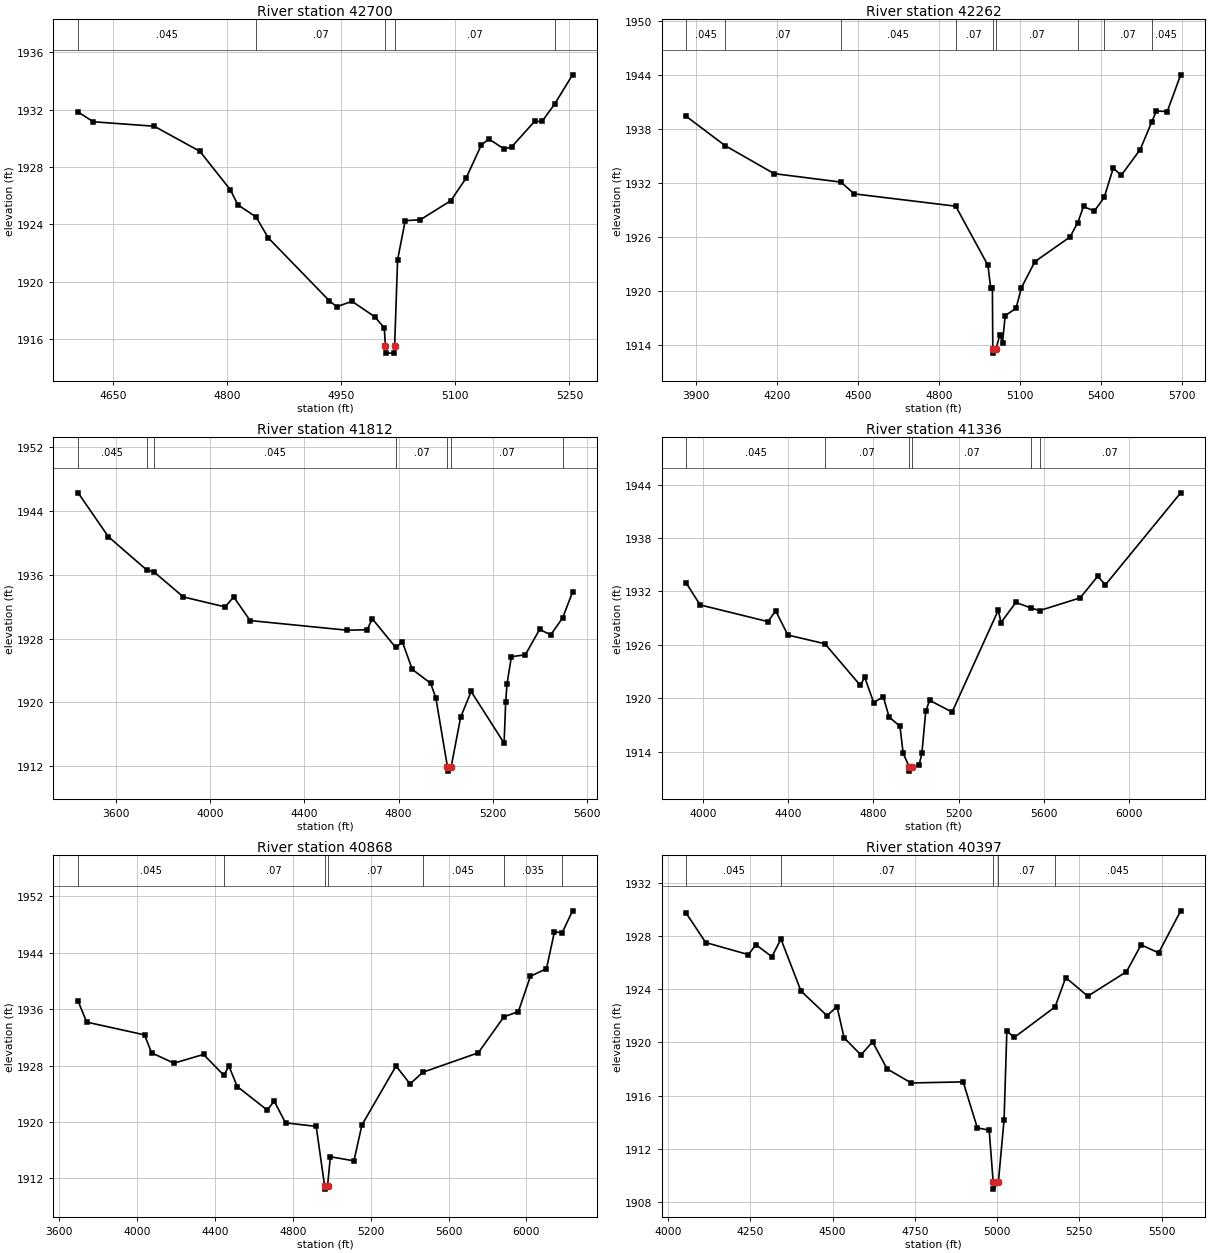
Type RM Length L Ch R = 1,42700,438,438,438
BEGIN DESCRIPTION:
Sandy Creek 49.0
END DESCRIPTION:
XS GIS Cut Line= 3
      1396155.00      6943688.03      1396155.00      6943288.00
      1396155.00      6943038.03
#Sta/Elev= 30
  4604.0 1931.84  4624.0 1931.16  4704.0 1930.85  4764.0 1929.10  4804.0 1926.42
  4814.0 1925.36  4837.9 1924.51  4854.0 1923.05  4934.0 1918.67  4944.0 1918.24
  4964.0 1918.62  4994.0 1917.54  5006.5 1916.76  5008.0 1915.50  5008.5 1915.00
  5019.6 1915.00  5020.1 1915.50  5024.0 1921.52  5034.0 1924.25  5054.0 1924.32
  5094.0 1925.65  5114.0 1927.22  5134.0 1929.53  5144.0 1929.96  5164.0 1929.26
  5174.0 1929.41  5204.0 1931.18  5214.0 1931.19  5230.4 1932.39  5254.0 1934.44
#Mann=5,-1,0
  4604.0   0.045       0  4837.9    0.07       0  5008.0    0.07       0
  5020.1    0.07       0  5230.4   0.045       0
Bank Sta=5008,5020.1
Exp/Cntr=0.3,0.1

Type RM Length L Ch R = 1,42262,450,450,450
BEGIN DESCRIPTION:
Sandy Creek 48.0
END DESCRIPTION:
XS GIS Cut Line= 3
      1395705.02      6944287.98      1396505.00      6943488.00
      1396505.00      6942788.04
#Sta/Elev= 30
  3864.4 1939.40  4007.8 1936.16  4189.6 1933.04  4436.7 1932.10  4486.6 1930.79
  4862.4 1929.42  4981.6 1922.85  4992.2 1920.29  4998.2 1920.29  4999.7 1913.59
  5000.2 1913.09  5011.8 1913.59  5025.7 1915.11  5035.7 1914.27  5045.7 1917.26
  5085.7 1918.07  5105.7 1920.36  5155.7 1923.26  5285.7 1926.00  5314.6 1927.60
  5335.7 1929.39  5375.7 1928.87  5412.4 1930.40  5445.7 1933.64  5475.7 1932.86
  5545.7 1935.72  5588.0 1938.75  5605.7 1940.01  5645.7 1939.93  5695.7 1944.02
#Mann=9,-1,0
  3864.4   0.045       0  4007.8    0.07       0  4436.7   0.045       0
  4862.4    0.07       0  4999.7    0.07       0  5011.8    0.07       0
  5314.6   0.035       0  5412.4    0.07       0  5588.0   0.045       0
Bank Sta=4999.7,5011.8
Exp/Cntr=0.3,0.1

Type RM Length L Ch R = 1,41812,476,476,476
BEGIN DESCRIPTION:
Sandy Creek 47.0
END DESCRIPTION:
XS GIS Cut Line= 3
      1395705.02      6944537.99      1396905.00      6943538.00
      1396705.02      6943038.04
#Sta/Elev= 30
  3438.6 1946.27  3566.8 1940.78  3729.2 1936.62  3761.5 1936.34  3885.7 1933.22
  4063.4 1931.97  4099.2 1933.23  4169.5 1930.26  4582.1 1929.05  4666.7 1929.11
  4688.2 1930.49  4787.5 1926.90  4816.4 1927.56  4858.1 1924.15  4936.2 1922.40
  4958.3 1920.58  5007.8 1911.89  5008.3 1911.39  5023.1 1911.89  5063.9 1918.16
  5108.3 1921.37  5248.3 1914.90  5255.1 1920.07  5260.5 1922.29  5279.3 1925.73
  5338.5 1925.97  5399.1 1929.15  5446.3 1928.47  5496.9 1930.59  5539.1 1933.82
#Mann=7,-1,0
  3438.6   0.045       0  3729.2    0.07       0  3761.5   0.045       0
  4787.5    0.07       0  5007.8    0.07       0  5023.1    0.07       0
  5496.9   0.035       0
Bank Sta=5007.8,5023.1
Exp/Cntr=0.3,0.1

Type RM Length L Ch R = 1,41336,468,468,468
BEGIN DESCRIPTION:
Sandy Creek 46.0
END DESCRIPTION:
XS GIS Cut Line= 3
      1396405.04      6944337.97      1397305.00      6943738.00
      1398504.95      6943438.01
#Sta/Elev= 30
  3922.8 1932.94  3987.4 1930.49  4305.8 1928.61  4341.9 1929.83  4399.0 1927.10
  4572.9 1926.12  4738.5 1921.45  4759.5 1922.35  4801.6 1919.50  4846.7 1920.17
  4873.7 1917.89  4924.8 1916.84  4939.8 1913.79  4968.2 1912.30  4968.7 1911.80
  4983.5 1912.30  5014.7 1912.52  5027.6 1913.79  5045.6 1918.52  5063.7 1919.76
  5169.3 1918.44  5385.8 1929.89  5398.7 1928.50  5468.3 1930.77  5538.1 1930.15
  5580.0 1929.85  5769.8 1931.28  5852.2 1933.71  5888.3 1932.75  6241.3 1943.09
#Mann=6,-1,0
  3922.8   0.045       0  4572.9    0.07       0  4968.2    0.07       0
  4983.5    0.07       0  5538.1   0.045       0  5580.0    0.07       0
Bank Sta=4968.2,4983.5
Exp/Cntr=0.3,0.1

Type RM Length L Ch R = 1,40868,471,471,471
BEGIN DESCRIPTION:
Sandy Creek 45.0
END DESCRIPTION:
XS GIS Cut Line= 3
      1396405.02      6944837.99      1397505.00      6944138.00
      1398704.96      6943838.01
#Sta/Elev= 30
  3696.7 1937.11  3740.7 1934.16  4037.9 1932.35  4074.3 1929.80  4189.4 1928.34
  4341.0 1929.58  4445.9 1926.61  4471.4 1927.93  4514.5 1925.03  4668.6 1921.69
  4704.2 1922.96  4762.6 1919.88  4920.1 1919.38  4963.1 1910.99  4963.6 1910.49
  4978.6 1910.99  4992.9 1915.08  5113.9 1914.50  5155.1 1919.58  5330.4 1927.94
  5402.5 1925.40  5467.8 1927.05  5753.0 1929.81  5884.7 1934.91  5959.1 1935.65
  6021.0 1940.66  6103.4 1941.73  6144.7 1946.99  6183.6 1946.80  6237.4 1949.93
#Mann=7,-1,0
  3696.7   0.045       0  4445.9    0.07       0  4963.1    0.07       0
  4978.6    0.07       0  5467.8   0.045       0  5884.7   0.035       0
  6183.6    0.07       0
Bank Sta=4963.1,4978.6
Exp/Cntr=0.3,0.1

Type RM Length L Ch R = 1,40397,560,560,560
BEGIN DESCRIPTION:
Sandy Creek 44.0
END DESCRIPTION:
XS GIS Cut Line= 3
      1397005.01      6944937.99      1397805.00      6944438.00
      1398305.00      6944188.00
#Sta/Elev= 30
  4055.7 1929.73  4114.7 1927.53  4244.4 1926.62  4267.4 1927.37  4315.7 1926.46
  4343.3 1927.79  4404.2 1923.88  4483.2 1922.02  4513.8 1922.70  4535.1 1920.36
  4586.4 1919.06  4621.7 1920.05  4665.9 1918.01  4739.1 1916.95  4897.1 1917.03
  4940.1 1913.57  4976.1 1913.39  4988.4 1909.45  4988.9 1908.95  5003.9 1909.45
  5021.4 1914.19  5029.8 1920.87  5052.2 1920.38  5176.4 1922.68  5208.7 1924.89
  5275.8 1923.49  5393.2 1925.33  5437.9 1927.36  5491.0 1926.75  5558.1 1929.92
#Mann=5,-1,0
  4055.7   0.045       0  4343.3    0.07       0  4988.4    0.07       0
  5003.9    0.07       0  5176.4   0.045       0
Bank Sta=4988.4,5003.9
Exp/Cntr=0.3,0.1