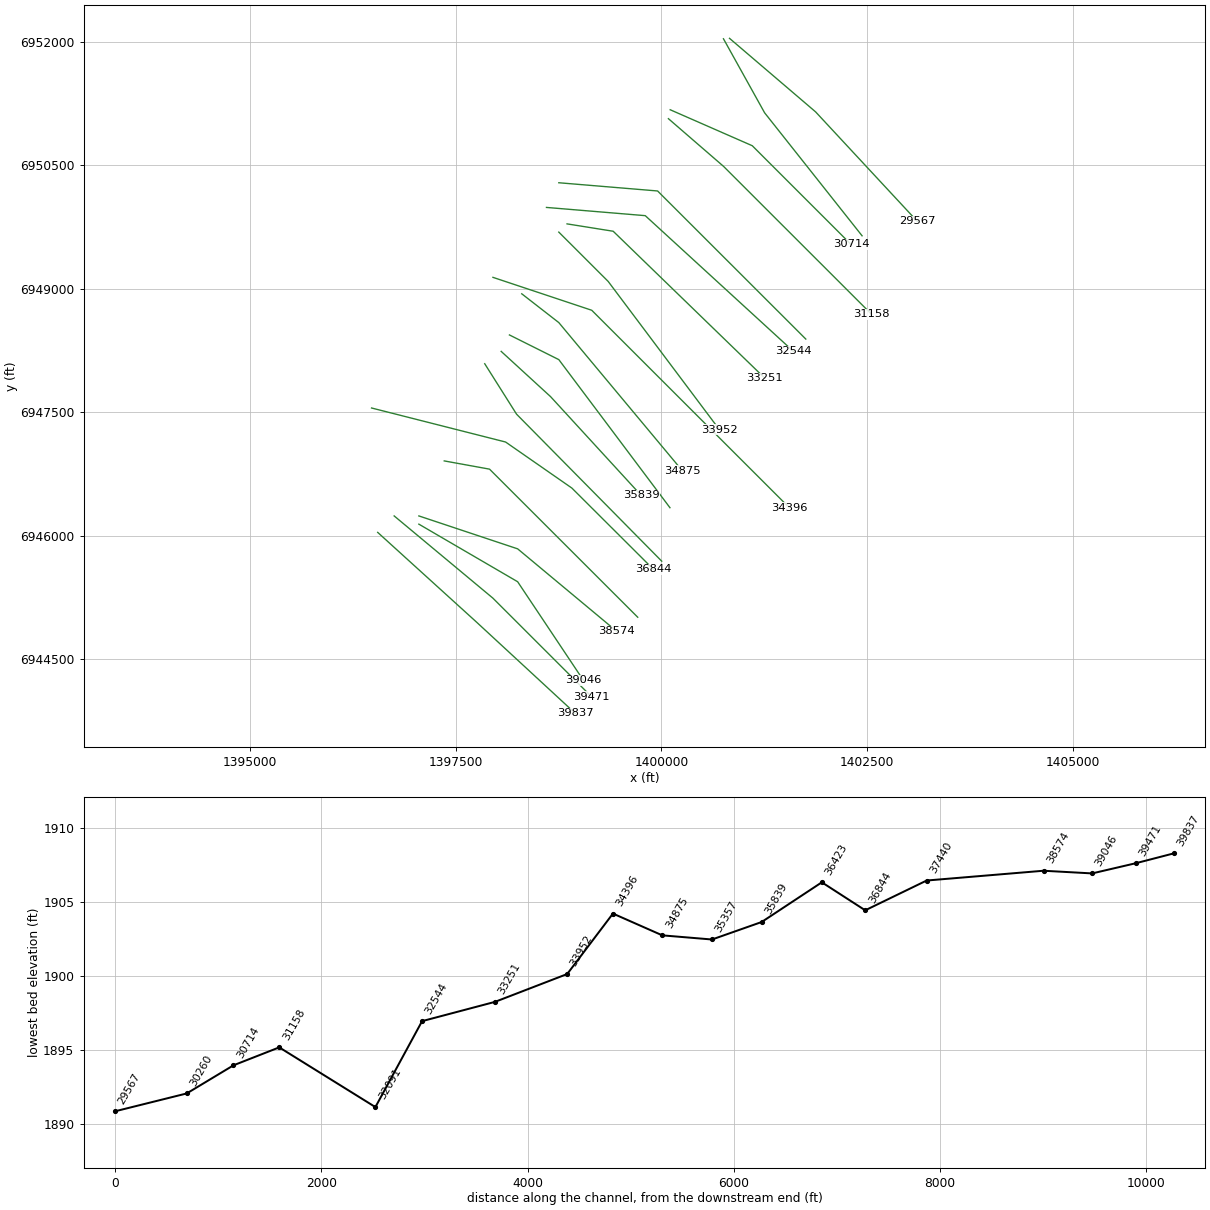
HEC-RAS study Sandy Creek.prj: Sandy Creek Base Level Engineering

--- Sandy Creek.g01 (geometry) --- (continued)

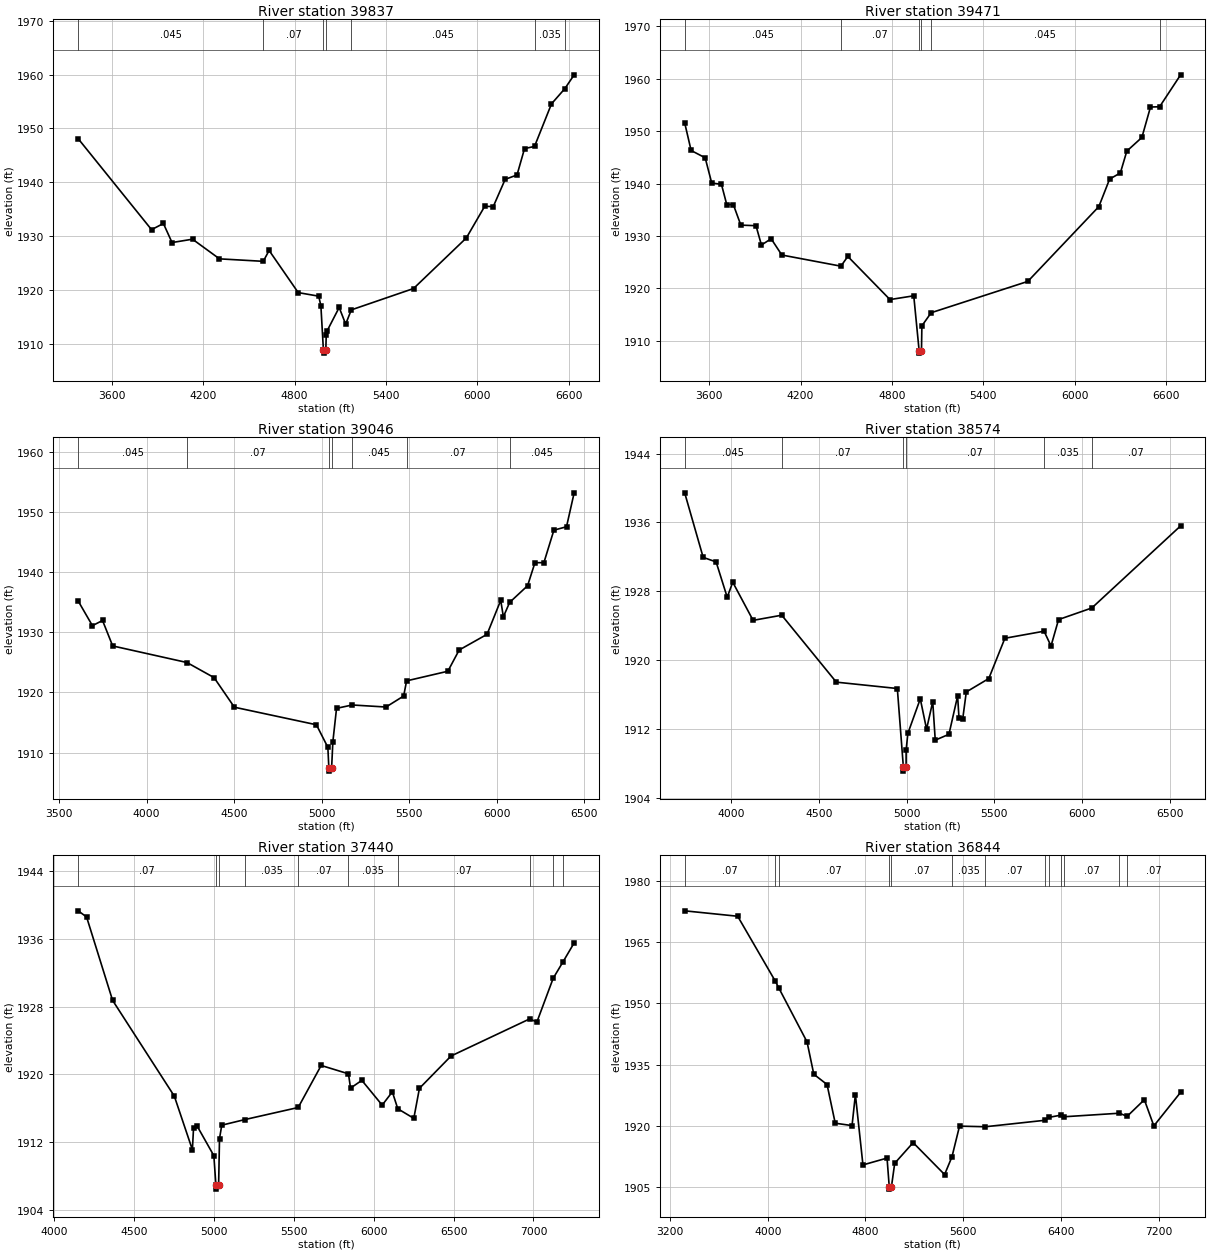
Type RM Length L Ch R = 1,39837,366,366,366
BEGIN DESCRIPTION:
Sandy Creek 43.0
END DESCRIPTION:
XS GIS Cut Line= 3
      1396555.01      6946037.99      1397754.45      6944948.19
      1398955.01      6943837.99
#Sta/Elev= 30
  3379.4 1948.08  3860.9 1931.19  3938.6 1932.34  3995.3 1928.80  4129.8 1929.42
  4306.9 1925.77  4594.2 1925.31  4632.6 1927.33  4823.8 1919.50  4958.3 1918.84
  4972.5 1917.06  4989.2 1908.76  4989.7 1908.26  5004.8 1908.76  5007.6 1911.59
  5014.4 1912.45  5092.6 1916.74  5135.2 1913.64  5172.1 1916.29  5580.8 1920.26
  5927.3 1929.65  6048.0 1935.53  6104.2 1935.48  6182.4 1940.54  6260.1 1941.35
  6309.4 1946.25  6375.0 1946.65  6486.4 1954.56  6574.2 1957.39  6635.2 1959.95
#Mann=7,-1,0
  3379.4   0.045       0  4594.2    0.07       0  4989.2    0.07       0
  5004.8    0.07       0  5172.1   0.045       0  6375.0   0.035       0
  6574.2    0.07       0
Bank Sta=4989.2,5004.8
Exp/Cntr=0.3,0.1

Type RM Length L Ch R = 1,39471,425,425,425
BEGIN DESCRIPTION:
Sandy Creek 42.0
END DESCRIPTION:
XS GIS Cut Line= 3
      1396754.99      6946238.01      1397955.00      6945238.00
      1399154.99      6944038.01
#Sta/Elev= 30
  3438.2 1951.59  3480.5 1946.31  3572.9 1944.91  3615.9 1940.09  3679.7 1939.85
  3714.8 1935.97  3757.8 1935.99  3807.2 1932.05  3906.8 1931.94  3942.6 1928.25
  4006.4 1929.45  4076.7 1926.34  4464.9 1924.21  4510.2 1926.07  4787.4 1917.83
  4943.6 1918.55  4978.8 1908.10  4979.3 1907.60  4994.4 1908.10  4997.0 1912.81
  5058.1 1915.32  5693.2 1921.30  6159.9 1935.59  6230.6 1940.84  6301.3 1942.02
  6343.8 1946.19  6442.8 1948.80  6499.3 1954.61  6559.2 1954.66  6697.3 1960.76
#Mann=6,-1,0
  3438.2   0.045       0  4464.9    0.07       0  4978.8    0.07       0
  4994.4    0.07       0  5058.1   0.045       0  6559.2   0.035       0
Bank Sta=4978.8,4994.4
Exp/Cntr=0.3,0.1

Type RM Length L Ch R = 1,39046,472,472,472
BEGIN DESCRIPTION:
Sandy Creek 41.0
END DESCRIPTION:
XS GIS Cut Line= 3
      1397054.98      6946138.01      1398255.00      6945438.00
      1399055.01      6944237.99
#Sta/Elev= 30
  3609.8 1935.19  3690.9 1931.10  3748.7 1931.96  3806.6 1927.73  4230.8 1924.97
  4385.5 1922.46  4501.3 1917.54  4969.7 1914.62  5035.1 1910.87  5040.8 1907.41
  5041.3 1906.91  5056.5 1907.41  5063.7 1911.81  5084.7 1917.35  5174.0 1917.91
  5367.1 1917.57  5467.8 1919.40  5484.7 1921.92  5720.2 1923.52  5784.8 1927.05
  5944.0 1929.66  6022.1 1935.31  6037.2 1932.57  6073.0 1934.97  6175.4 1937.74
  6217.4 1941.57  6268.5 1941.58  6325.6 1946.98  6397.7 1947.55  6441.3 1953.19
#Mann=7,-1,0
  3609.8   0.045       0  4230.8    0.07       0  5040.8    0.07       0
  5056.5    0.07       0  5174.0   0.045       0  5484.7    0.07       0
  6073.0   0.045       0
Bank Sta=5040.8,5056.5
Exp/Cntr=0.3,0.1

Type RM Length L Ch R = 1,38574,1134,1134,1134
BEGIN DESCRIPTION:
Sandy Creek 40.0
END DESCRIPTION:
XS GIS Cut Line= 3
      1397055.00      6946238.00      1398255.00      6945838.00
      1399455.03      6944837.97
#Sta/Elev= 30
  3735.1 1939.43  3840.5 1931.93  3914.3 1931.40  3977.5 1927.30  4009.2 1929.04
  4125.1 1924.61  4288.3 1925.21  4599.5 1917.43  4947.3 1916.69  4981.6 1907.59
  4982.1 1907.09  4997.3 1907.59  4997.4 1909.53  5007.2 1911.47  5078.1 1915.49
  5113.9 1911.97  5149.1 1915.16  5163.4 1910.69  5241.5 1911.37  5290.9 1915.82
  5298.7 1913.29  5319.6 1913.10  5340.4 1916.29  5468.6 1917.85  5560.4 1922.53
  5783.8 1923.35  5823.3 1921.63  5866.3 1924.70  6056.0 1926.05  6562.1 1935.59
#Mann=6,-1,0
  3735.1   0.045       0  4288.3    0.07       0  4981.6    0.07       0
  4997.3    0.07       0  5783.8   0.035       0  6056.0    0.07       0
Bank Sta=4981.6,4997.3
Exp/Cntr=0.3,0.1

Type RM Length L Ch R = 1,37440,596,596,596
BEGIN DESCRIPTION:
Sandy Creek 39.0
END DESCRIPTION:
XS GIS Cut Line= 3
      1397363.37      6946906.74      1397913.33      6946806.75
      1399713.36      6945006.73
#Sta/Elev= 30
  4150.4 1939.33  4202.9 1938.60  4365.5 1928.75  4752.1 1917.42  4865.2 1911.08
  4872.3 1913.64  4893.5 1913.93  4999.6 1910.38  5012.2 1906.93  5012.7 1906.43
  5029.4 1906.93  5034.9 1912.41  5049.1 1913.99  5195.3 1914.66  5527.5 1916.08
  5671.3 1921.05  5842.2 1920.06  5855.2 1918.37  5925.9 1919.29  6053.2 1916.36
  6116.8 1917.93  6150.9 1915.93  6251.2 1914.80  6286.5 1918.35  6484.5 1922.17
  6976.1 1926.55  7021.9 1926.19  7123.8 1931.36  7184.0 1933.26  7255.0 1935.54
#Mann=10,-1,0
  4150.4    0.07       0  5012.2    0.07       0  5029.4    0.07       0
  5195.3   0.035       0  5527.5    0.07       0  5842.2   0.035       0
  6150.9    0.07       0  6976.1   0.035       0  7123.8    0.07       0
  7184.0   0.035       0
Bank Sta=5012.2,5029.4
Exp/Cntr=0.3,0.1

Type RM Length L Ch R = 1,36844,421,421,421
BEGIN DESCRIPTION:
Sandy Creek 38.0
END DESCRIPTION:
XS GIS Cut Line= 4
      1396480.34      6947550.09      1398108.60      6947136.36
      1398914.41      6946576.00      1399905.02      6945587.98
#Sta/Elev= 30
  3320.0 1972.72  3753.9 1971.39  4061.8 1955.47  4088.9 1953.89  4321.9 1940.55
  4377.2 1932.62  4485.7 1930.09  4552.6 1920.60  4690.3 1920.01  4717.7 1927.62
  4779.6 1910.36  4976.9 1912.04  4995.1 1904.92  4995.6 1904.42  5012.5 1904.92
  5039.6 1910.76  5190.5 1915.83  5448.1 1908.00  5508.4 1912.35  5570.3 1919.88
  5781.8 1919.73  6268.2 1921.31  6303.9 1922.04  6403.1 1922.59  6426.4 1922.18
  6879.8 1923.05  6942.6 1922.28  7083.6 1926.36  7161.4 1919.94  7380.6 1928.18
#Mann=13,-1,0
  3320.0    0.07       0  4061.8   0.045       0  4088.9    0.07       0
  4995.1    0.07       0  5012.5    0.07       0  5508.4   0.035       0
  5781.8    0.07       0  6268.2   0.035       0  6303.9    0.07       0
  6403.1   0.035       0  6426.4    0.07       0  6879.8   0.035       0
  6942.6    0.07       0
Bank Sta=4995.1,5012.5
Exp/Cntr=0.3,0.1

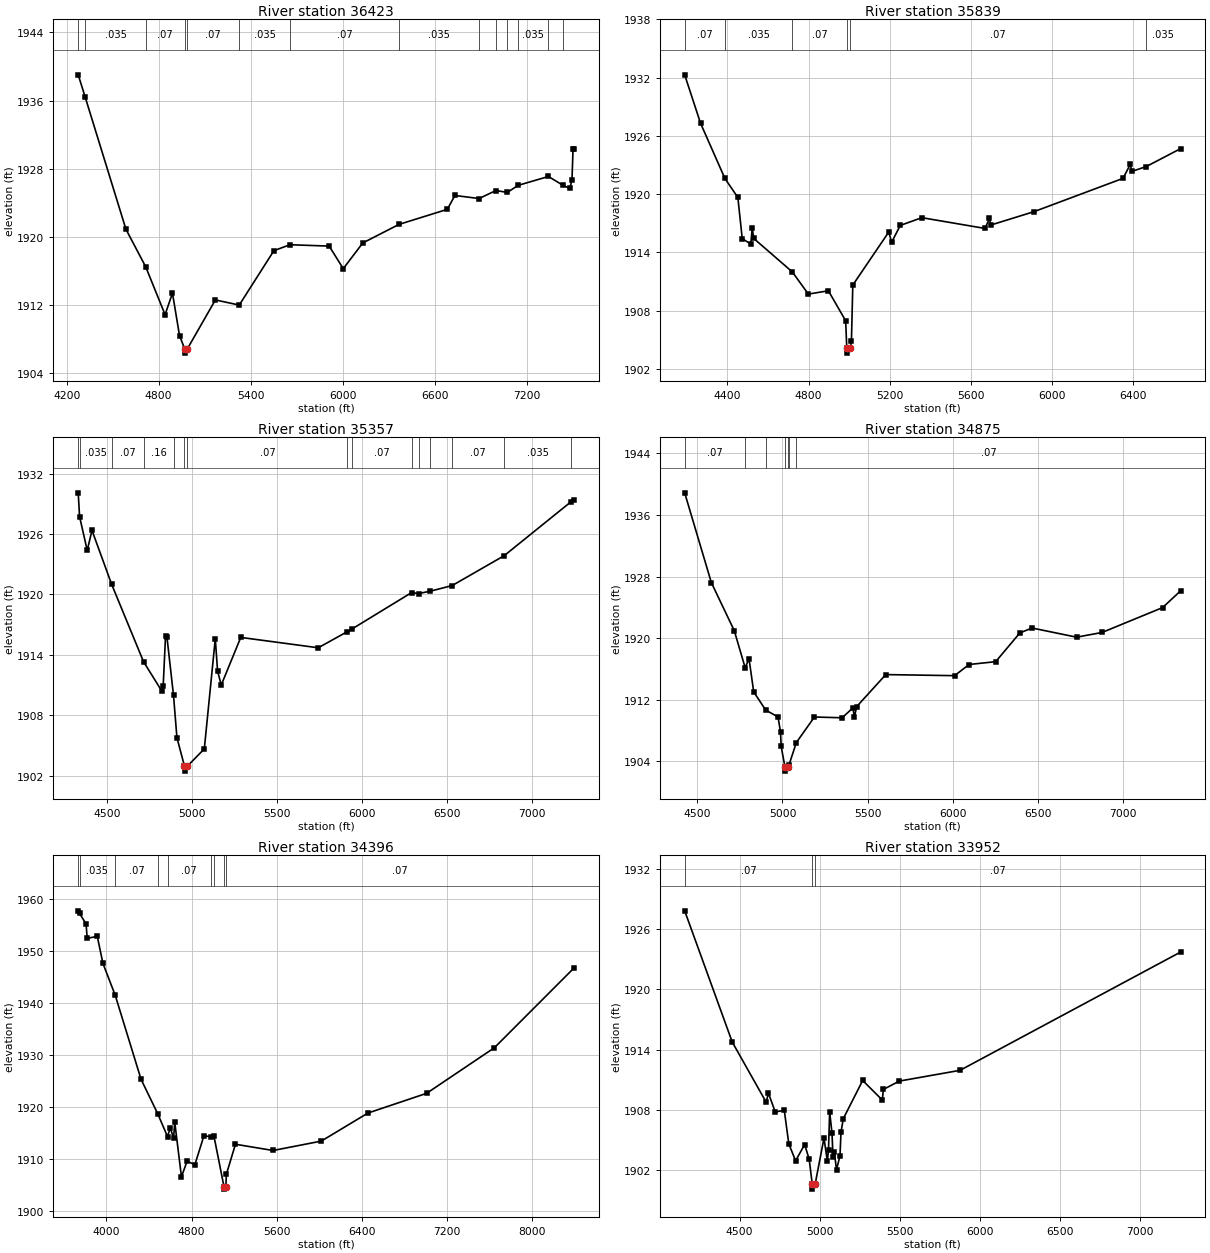
Type RM Length L Ch R = 1,36423,584,584,584
BEGIN DESCRIPTION:
Sandy Creek 37.0
END DESCRIPTION:
XS GIS Cut Line= 3
      1397855.02      6948087.97      1398241.67      6947474.91
      1400005.03      6945687.97
#Sta/Elev= 30
  4275.2 1939.02  4320.4 1936.42  4586.5 1920.87  4715.7 1916.45  4841.8 1910.83
  4890.1 1913.36  4936.0 1908.38  4969.7 1906.81  4970.2 1906.31  4987.1 1906.81
  5169.9 1912.56  5325.7 1911.96  5551.7 1918.35  5656.5 1919.05  5912.3 1918.89
  6004.3 1916.24  6131.6 1919.26  6367.9 1921.44  6683.1 1923.21  6732.6 1924.84
  6890.4 1924.48  6999.8 1925.42  7074.8 1925.20  7145.0 1926.03  7342.5 1927.07
  7435.5 1926.06  7482.2 1925.66  7496.4 1926.71  7503.4 1930.36  7510.5 1930.34
#Mann=14,-1,0
  4275.2    0.07       0  4320.4   0.035       0  4715.7    0.07       0
  4969.7    0.07       0  4987.1    0.07       0  5325.7   0.035       0
  5656.5    0.07       0  6367.9   0.035       0  6890.4    0.07       0
  6999.8   0.035       0  7074.8    0.07       0  7145.0   0.035       0
  7342.5    0.07       0  7435.5   0.035       0
Bank Sta=4969.7,4987.1
Exp/Cntr=0.3,0.1

Type RM Length L Ch R = 1,35839,482,482,482
BEGIN DESCRIPTION:
Sandy Creek 36.0
END DESCRIPTION:
XS GIS Cut Line= 3
      1398054.97      6948238.02      1398655.00      6947688.00
      1399755.03      6946487.97
#Sta/Elev= 30
  4190.2 1932.29  4268.2 1927.31  4388.2 1921.62  4452.0 1919.66  4473.6 1915.42
  4515.8 1914.86  4522.9 1916.55  4529.7 1915.45  4720.3 1911.99  4799.1 1909.71
  4897.8 1910.05  4982.9 1906.96  4988.3 1904.13  4988.8 1903.63  5005.8 1904.13
  5011.3 1904.91  5018.0 1910.64  5195.0 1916.10  5209.2 1915.05  5251.7 1916.78
  5357.8 1917.58  5669.2 1916.47  5690.8 1917.51  5697.6 1916.82  5910.3 1918.20
  6348.7 1921.63  6384.5 1923.08  6391.3 1922.34  6462.5 1922.84  6632.1 1924.69
#Mann=6,-1,0
  4190.2    0.07       0  4388.2   0.035       0  4720.3    0.07       0
  4988.3    0.07       0  5005.8    0.07       0  6462.5   0.035       0
Bank Sta=4988.3,5005.8
Exp/Cntr=0.3,0.1

Type RM Length L Ch R = 1,35357,482,482,482
BEGIN DESCRIPTION:
Sandy Creek 35.0
END DESCRIPTION:
XS GIS Cut Line= 3
      1398154.97      6948438.02      1398755.00      6948138.00
      1400105.03      6946337.97
#Sta/Elev= 30
  4329.1 1930.09  4337.1 1927.73  4382.2 1924.37  4410.2 1926.36  4526.3 1920.99
  4713.8 1913.32  4821.1 1910.41  4829.5 1910.91  4843.4 1915.84  4851.8 1915.76
  4890.4 1909.97  4910.5 1905.77  4954.9 1902.95  4955.4 1902.45  4972.4 1902.95
  5071.8 1904.66  5136.4 1915.61  5150.0 1912.36  5171.8 1911.01  5286.4 1915.73
  5742.7 1914.70  5915.0 1916.31  5940.0 1916.55  6292.4 1920.18  6334.0 1920.09
  6402.5 1920.32  6531.6 1920.88  6838.1 1923.85  7232.8 1929.22  7250.0 1929.40
#Mann=15,-1,0
  4329.1    0.07       0  4337.1   0.035       0  4526.3    0.07       0
  4713.8    0.16       0  4890.4    0.07       0  4954.9    0.07       0
  4972.4    0.07       0  5915.0   0.035       0  5940.0    0.07       0
  6292.4   0.035       0  6334.0    0.07       0  6402.5   0.035       0
  6531.6    0.07       0  6838.1   0.035       0  7232.8    0.07       0
Bank Sta=4954.9,4972.4
Exp/Cntr=0.3,0.1

Type RM Length L Ch R = 1,34875,479,479,479
BEGIN DESCRIPTION:
Sandy Creek 34.0
END DESCRIPTION:
XS GIS Cut Line= 3
      1398304.98      6948938.01      1398755.00      6948588.00
      1400255.01      6946787.99
#Sta/Elev= 30
  4425.6 1938.88  4582.2 1927.22  4717.0 1920.97  4780.6 1916.18  4803.9 1917.29
  4831.0 1913.03  4901.4 1910.66  4974.0 1909.77  4988.5 1907.80  4992.5 1905.93
  5014.9 1903.23  5015.4 1902.73  5032.5 1903.23  5038.2 1903.52  5081.5 1906.44
  5187.7 1909.76  5350.4 1909.66  5414.2 1910.95  5422.0 1909.74  5436.3 1911.12
  5606.9 1915.27  6011.0 1915.13  6096.3 1916.58  6252.5 1916.95  6394.4 1920.68
  6466.0 1921.32  6727.6 1920.13  6877.3 1920.74  7232.7 1923.97  7338.8 1926.15
#Mann=7,-1,0
  4425.6    0.07       0  4780.6    0.16       0  4901.4    0.07       0
  5014.9    0.07       0  5032.5    0.07       0  5038.2   0.033       0
  5081.5    0.07       0
Bank Sta=5014.9,5032.5
Exp/Cntr=0.3,0.1

Type RM Length L Ch R = 1,34396,444,444,444
BEGIN DESCRIPTION:
Sandy Creek 33.0
END DESCRIPTION:
XS GIS Cut Line= 3
      1397954.95      6949138.02      1399155.00      6948738.00
      1401555.02      6946337.98
#Sta/Elev= 30
  3735.2 1957.65  3747.8 1957.14  3809.0 1955.15  3819.6 1952.37  3914.4 1952.74
  3967.1 1947.58  4083.4 1941.40  4325.5 1925.29  4483.3 1918.63  4574.0 1914.30
  4599.6 1915.97  4631.2 1913.99  4641.8 1917.10  4705.0 1906.58  4757.7 1909.54
  4831.5 1908.91  4915.8 1914.42  4982.0 1914.29  5010.3 1914.39  5104.4 1904.70
  5104.9 1904.20  5122.2 1904.70  5127.4 1907.07  5212.3 1912.82  5565.8 1911.62
  6018.4 1913.42  6456.8 1918.81  7008.3 1922.60  7644.7 1931.35  8394.3 1946.70
#Mann=9,-1,0
  3735.2    0.07       0  3747.8   0.035       0  4083.4    0.07       0
  4483.3    0.16       0  4574.0    0.07       0  4982.0   0.033       0
  5010.3    0.07       0  5104.4   0.033       0  5122.2    0.07       0
Bank Sta=5104.4,5122.2
Exp/Cntr=0.3,0.1

Type RM Length L Ch R = 1,33952,701,701,701
BEGIN DESCRIPTION:
Sandy Creek 32.0
END DESCRIPTION:
XS GIS Cut Line= 3
      1398754.98      6949688.02      1399355.00      6949088.00
      1400705.03      6947287.96
#Sta/Elev= 30
  4156.6 1927.81  4453.6 1914.76  4665.7 1908.77  4679.9 1909.67  4722.3 1907.80
  4778.9 1907.96  4807.2 1904.62  4849.6 1902.94  4906.2 1904.56  4934.4 1903.10
  4953.7 1900.62  4954.2 1900.12  4971.8 1900.62  5027.0 1905.20  5047.9 1902.91
  5055.2 1904.03  5062.4 1907.83  5077.0 1905.68  5083.3 1903.35  5091.6 1903.78
  5105.2 1902.06  5127.0 1903.43  5133.3 1905.80  5147.9 1907.14  5268.7 1910.93
  5391.6 1908.98  5397.9 1910.04  5497.9 1910.87  5877.0 1911.94  7255.2 1923.71
#Mann=3,-1,0
  4156.6    0.07       0  4953.7    0.07       0  4971.8    0.07       0
Bank Sta=4953.7,4971.8
Exp/Cntr=0.3,0.1

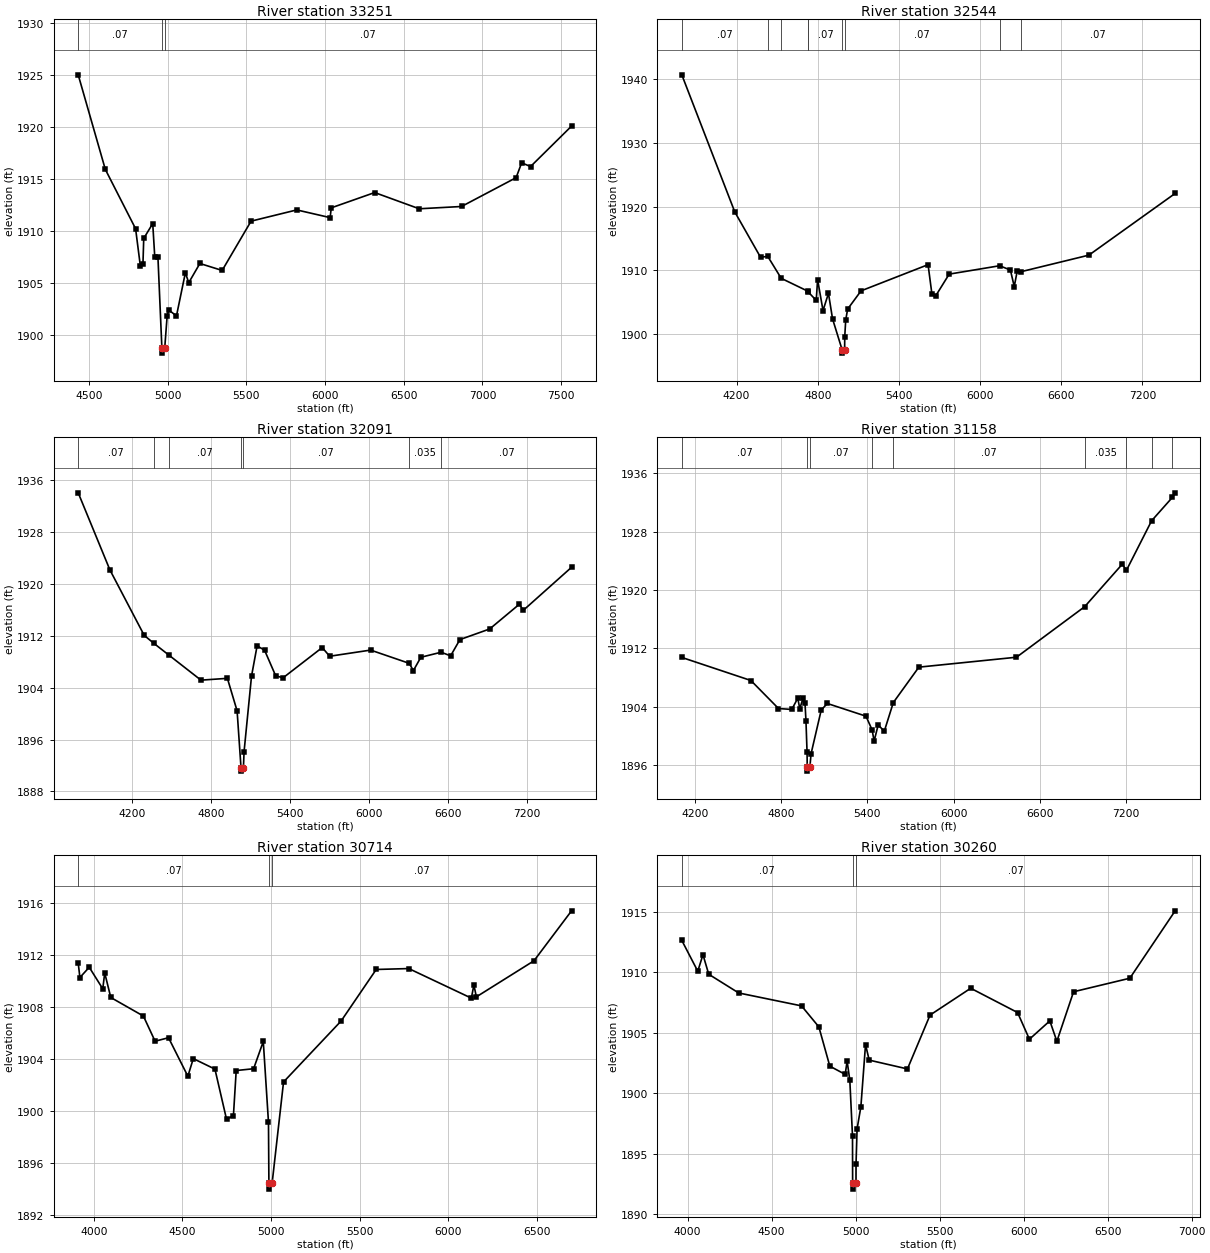
Type RM Length L Ch R = 1,33251,707,707,707
BEGIN DESCRIPTION:
Sandy Creek 31.0
END DESCRIPTION:
XS GIS Cut Line= 3
      1398855.02      6949788.00      1399415.43      6949698.52
      1401257.20      6947912.12
#Sta/Elev= 30
  4432.5 1925.00  4604.6 1915.91  4797.0 1910.20  4827.4 1906.59  4843.7 1906.82
  4848.7 1909.27  4905.8 1910.70  4918.6 1907.52  4938.8 1907.49  4963.9 1898.74
  4964.4 1898.24  4982.0 1898.74  4997.3 1901.80  5007.2 1902.39  5056.6 1901.82
  5113.1 1905.97  5134.5 1905.01  5205.2 1906.86  5346.7 1906.19  5530.4 1910.93
  5820.5 1912.01  6032.5 1911.27  6039.7 1912.21  6315.4 1913.68  6598.4 1912.12
  6867.0 1912.34  7213.7 1915.11  7248.9 1916.54  7305.5 1916.18  7565.8 1920.07
#Mann=3,-1,0
  4432.5    0.07       0  4963.9    0.07       0  4982.0    0.07       0
Bank Sta=4963.9,4982
Exp/Cntr=0.3,0.1

Type RM Length L Ch R = 1,32544,453,453,453
BEGIN DESCRIPTION:
Sandy Creek 30.0
END DESCRIPTION:
XS GIS Cut Line= 3
      1398604.98      6949988.00      1399805.00      6949888.00
      1401605.00      6948238.00
#Sta/Elev= 30
  3795.4 1940.73  4186.8 1919.16  4377.4 1912.02  4430.3 1912.17  4530.0 1908.71
  4729.2 1906.66  4731.4 1906.52  4788.9 1905.24  4798.9 1908.51  4839.0 1903.64
  4879.2 1906.35  4909.3 1902.34  4980.5 1897.44  4981.0 1896.94  4998.6 1897.44
  4999.6 1899.55  5006.7 1902.14  5020.9 1903.87  5120.1 1906.74  5615.3 1910.86
  5643.6 1906.26  5672.0 1905.96  5771.3 1909.37  6144.2 1910.69  6223.9 1910.01
  6252.2 1907.42  6273.8 1909.81  6301.7 1909.75  6804.1 1912.36  7441.4 1922.07
#Mann=9,-1,0
  3795.4    0.07       0  4430.3   0.035       0  4530.0    0.07       0
  4729.2   0.035       0  4731.4    0.07       0  4980.5    0.07       0
  4998.6    0.07       0  6144.2   0.035       0  6301.7    0.07       0
Bank Sta=4980.5,4998.6
Exp/Cntr=0.3,0.1

Type RM Length L Ch R = 1,32091,933,933,933
BEGIN DESCRIPTION:
Sandy Creek 29.0
END DESCRIPTION:
XS GIS Cut Line= 3
      1398755.00      6950288.00      1399955.00      6950188.00
      1401754.97      6948388.03
#Sta/Elev= 30
  3791.3 1934.09  4032.1 1922.20  4293.0 1912.09  4366.3 1910.86  4484.0 1908.99
  4724.5 1905.18  4925.2 1905.46  4999.0 1900.44  5028.8 1891.64  5029.3 1891.14
  5047.0 1891.64  5052.0 1894.16  5108.6 1905.80  5151.0 1910.47  5207.6 1909.81
  5292.4 1905.84  5349.0 1905.55  5646.0 1910.21  5702.6 1908.87  6013.7 1909.82
  6306.8 1907.78  6339.0 1906.66  6395.5 1908.71  6549.8 1909.49  6621.8 1908.93
  6692.5 1911.44  6918.8 1913.08  7145.1 1916.91  7173.4 1915.94  7541.0 1922.60
#Mann=7,-1,0
  3791.3    0.07       0  4366.3   0.035       0  4484.0    0.07       0
  5028.8    0.07       0  5047.0    0.07       0  6306.8   0.035       0
  6549.8    0.07       0
Bank Sta=5028.8,5047
Exp/Cntr=0.3,0.1

Type RM Length L Ch R = 1,31158,444,444,444
BEGIN DESCRIPTION:
Sandy Creek 28.0
END DESCRIPTION:
XS GIS Cut Line= 3
      1400086.23      6951066.86      1400755.00      6950488.00
      1402555.01      6948687.99
#Sta/Elev= 30
  4110.7 1910.75  4591.0 1907.59  4782.9 1903.75  4875.1 1903.62  4916.8 1905.16
  4931.1 1903.72  4953.0 1905.15  4967.2 1904.49  4973.8 1902.10  4981.5 1897.74
  4982.8 1895.67  4983.3 1895.17  5001.0 1895.67  5009.3 1897.55  5080.1 1903.55
  5122.5 1904.44  5391.2 1902.70  5433.8 1900.82  5447.7 1899.29  5476.0 1901.50
  5518.5 1900.64  5581.3 1904.57  5758.9 1909.42  6437.7 1910.78  6911.9 1917.71
  7173.1 1923.53  7202.0 1922.69  7377.1 1929.48  7521.3 1932.68  7540.8 1933.31
#Mann=9,-1,0
  4110.7    0.07       0  4982.8    0.07       0  5001.0    0.07       0
  5433.8   0.035       0  5581.3    0.07       0  6911.9   0.035       0
  7202.0    0.07       0  7377.1   0.035       0  7521.3    0.07       0
Bank Sta=4982.8,5001
Exp/Cntr=0.3,0.1

Type RM Length L Ch R = 1,30714,454,454,454
BEGIN DESCRIPTION:
Sandy Creek 27.0
END DESCRIPTION:
XS GIS Cut Line= 3
      1400107.94      6951175.36      1401105.00      6950738.00
      1402304.98      6949538.02
#Sta/Elev= 30
  3911.2 1911.39  3920.7 1910.27  3973.5 1911.06  4049.9 1909.40  4060.9 1910.62
  4095.2 1908.73  4279.3 1907.30  4345.3 1905.36  4421.2 1905.63  4530.4 1902.66
  4561.0 1904.02  4683.3 1903.21  4748.8 1899.34  4787.7 1899.63  4803.4 1903.10
  4901.7 1903.24  4956.3 1905.34  4985.6 1899.12  4988.0 1894.46  4988.5 1893.96
  5006.5 1894.46  5070.7 1902.22  5395.9 1906.92  5593.9 1910.89  5777.8 1910.96
  6131.3 1908.68  6145.5 1909.69  6159.6 1908.78  6484.9 1911.56  6697.0 1915.41
#Mann=3,-1,0
  3911.2    0.07       0  4988.0    0.07       0  5006.5    0.07       0
Bank Sta=4988,5006.5
Exp/Cntr=0.3,0.1

Type RM Length L Ch R = 1,30260,693,693,693
BEGIN DESCRIPTION:
Sandy Creek 26.0
END DESCRIPTION:
XS GIS Cut Line= 3
      1400754.98      6952038.03      1401255.00      6951138.00
      1402438.69      6949643.21
#Sta/Elev= 30
  3965.5 1912.65  4060.5 1910.10  4091.4 1911.47  4125.7 1909.85  4304.1 1908.30
  4678.2 1907.23  4781.2 1905.49  4846.4 1902.24  4937.9 1901.56  4949.3 1902.66
  4965.4 1901.08  4981.4 1896.47  4982.2 1892.56  4982.7 1892.06  5002.2 1892.56
  5002.3 1894.10  5008.7 1897.05  5031.2 1898.87  5058.9 1904.02  5080.9 1902.74
  5308.4 1902.01  5443.0 1906.47  5685.0 1908.69  5963.9 1906.68  6034.4 1904.47
  6155.9 1905.99  6197.8 1904.30  6297.2 1908.40  6632.1 1909.52  6901.8 1915.10
#Mann=3,-1,0
  3965.5    0.07       0  4982.2    0.07       0  5002.2    0.07       0
Bank Sta=4982.2,5002.2
Exp/Cntr=0.3,0.1

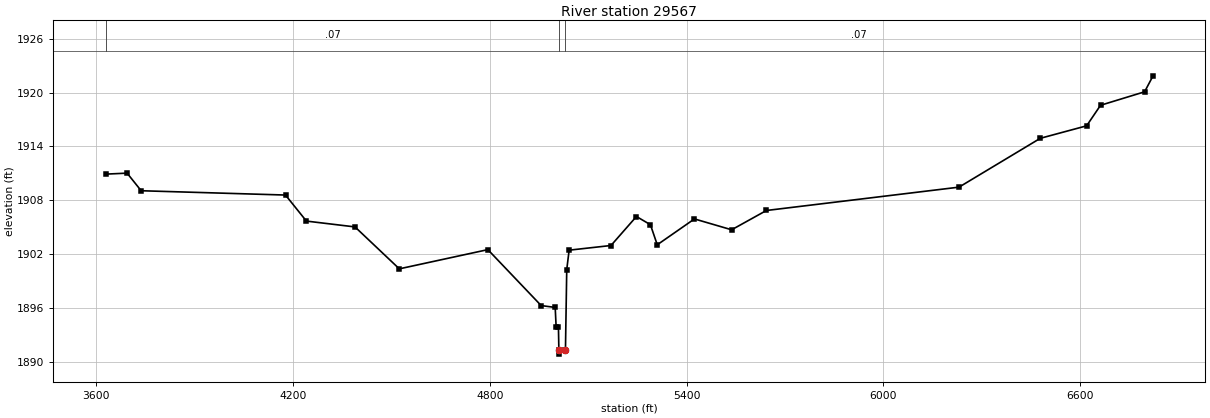
Type RM Length L Ch R = 1,29567,797,797,797
BEGIN DESCRIPTION:
Mapping XS be73e679
END DESCRIPTION:
XS GIS Cut Line= 3
      1400828.42      6952043.42      1401874.43      6951149.32
      1403110.73      6949817.58
#Sta/Elev= 30
  3629.1 1910.91  3694.1 1911.02  3737.0 1909.06  4177.1 1908.58  4240.8 1905.68
  4389.0 1905.03  4524.1 1900.36  4794.1 1902.50  4956.6 1896.27  4999.4 1896.06
  5002.3 1893.86  5009.3 1893.86  5010.6 1891.36  5011.1 1890.86  5030.7 1891.36
  5034.6 1900.28  5041.9 1902.44  5169.5 1902.96  5247.1 1906.19  5289.7 1905.28
  5310.6 1903.04  5424.0 1905.92  5537.4 1904.71  5643.4 1906.86  6230.7 1909.46
  6478.5 1914.90  6619.7 1916.29  6662.2 1918.58  6796.5 1920.08  6822.3 1921.86
#Mann=3,-1,0
  3629.1    0.07       0  5010.6    0.07       0  5030.7    0.07       0
Bank Sta=5010.6,5030.7
Exp/Cntr=0.3,0.1