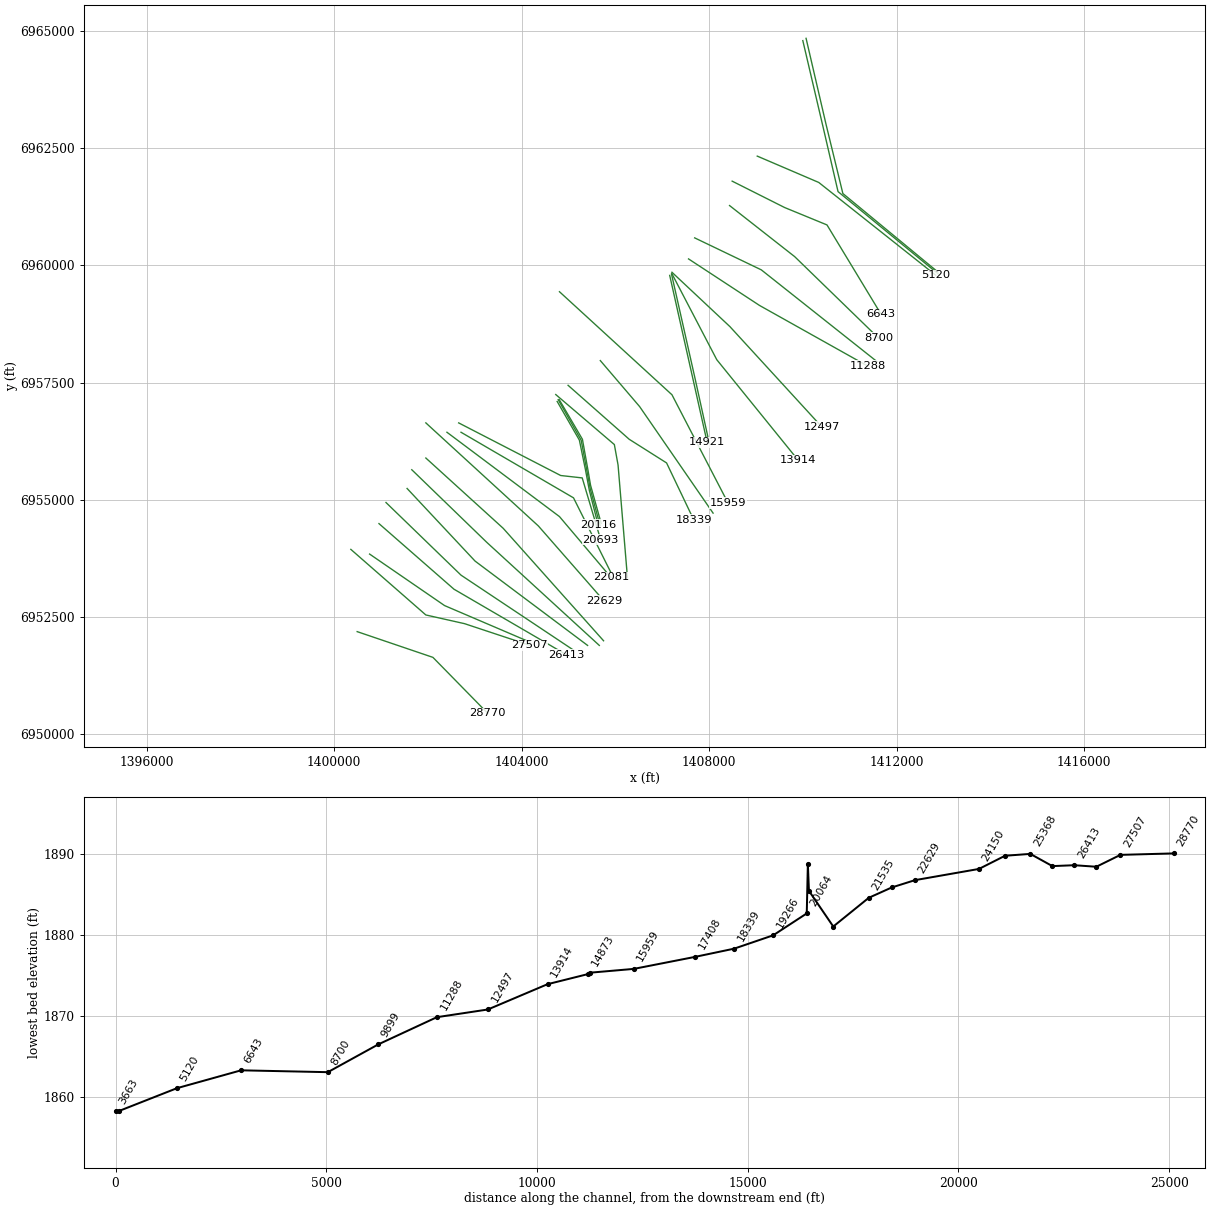
HEC-RAS study Sandy Creek.prj: Sandy Creek Base Level Engineering

--- Sandy Creek.g01 (geometry) --- (continued)

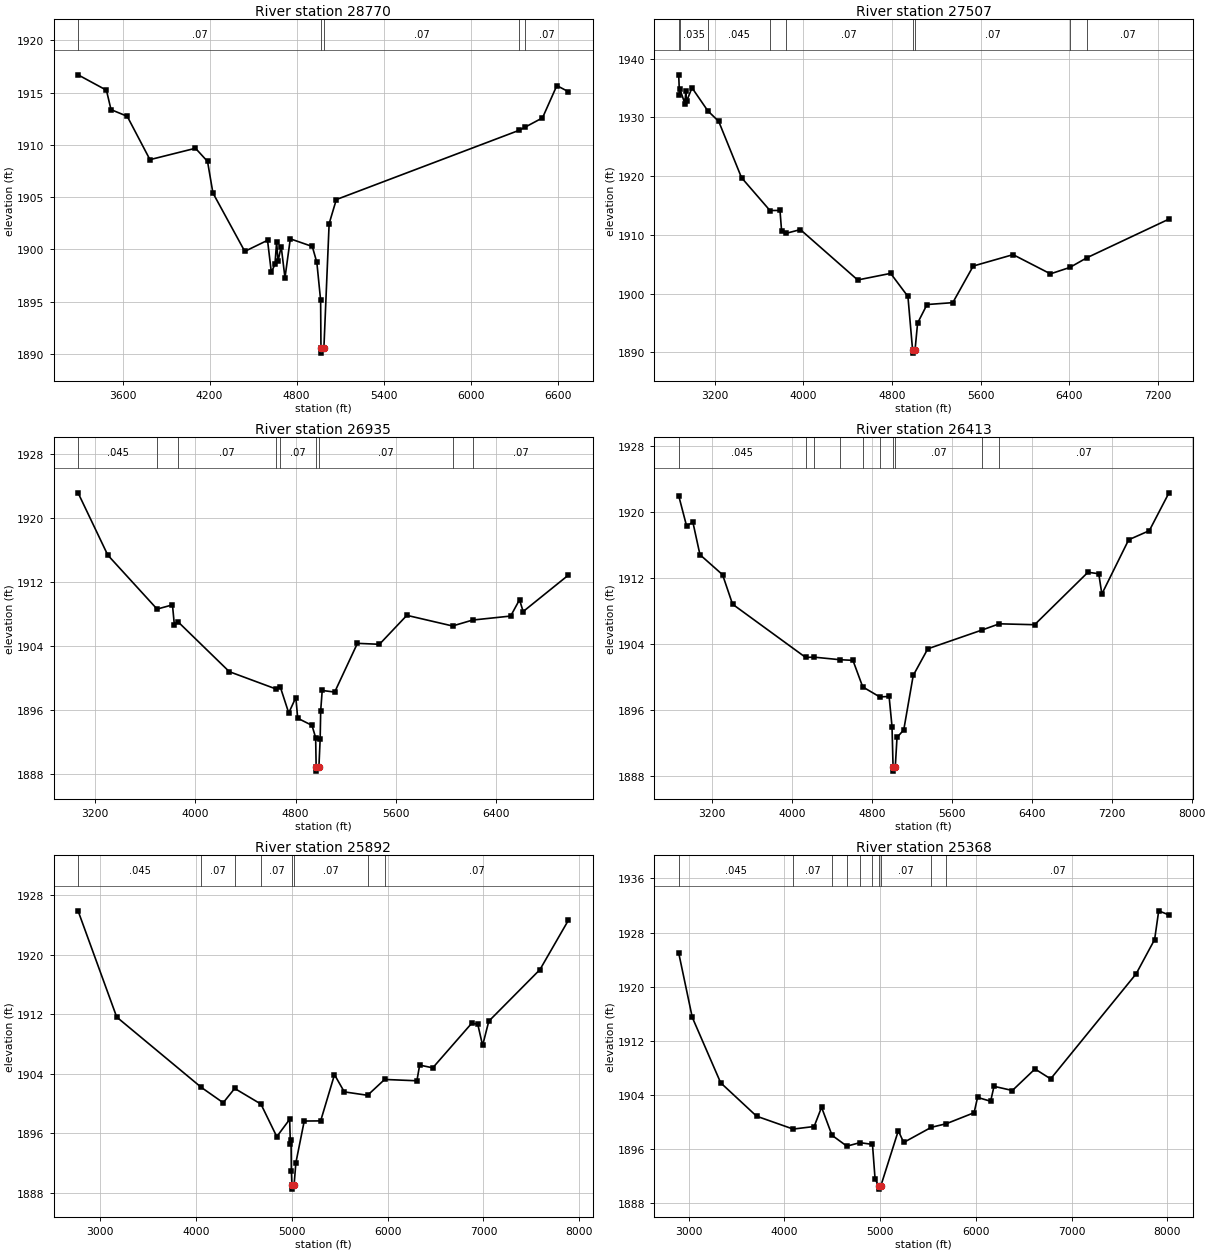
Type RM Length L Ch R = 1,28770,1263,1263,1263
BEGIN DESCRIPTION:
Sandy Creek 25.0
END DESCRIPTION:
XS GIS Cut Line= 3
      1400489.89      6952182.30      1402105.88      6951632.98
      1403276.37      6950437.48
#Sta/Elev= 30
  3293.2 1916.71  3488.7 1915.24  3520.4 1913.38  3632.1 1912.74  3788.9 1908.59
  4102.7 1909.68  4185.8 1908.42  4223.0 1905.40  4442.6 1899.81  4599.5 1900.87
  4625.6 1897.81  4650.5 1898.57  4662.3 1900.72  4671.6 1898.85  4693.6 1900.27
  4719.7 1897.28  4756.4 1901.01  4908.0 1900.28  4939.4 1898.75  4965.5 1895.12
  4967.8 1890.57  4968.3 1890.07  4988.0 1890.57  5024.1 1902.46  5073.7 1904.77
  6334.1 1911.40  6375.0 1911.70  6495.0 1912.59  6594.0 1915.68  6673.1 1915.10
#Mann=5,-1,0
  3293.2    0.07       0  4967.8    0.07       0  4988.0    0.07       0
  6334.1   0.035       0  6375.0    0.07       0
Bank Sta=4967.8,4988
Exp/Cntr=0.3,0.1

Type RM Length L Ch R = 1,27507,572,572,572
BEGIN DESCRIPTION:
Sandy Creek 24.0
END DESCRIPTION:
XS GIS Cut Line= 4
      1400355.03      6953937.97      1401955.00      6952538.00
      1402779.73      6952352.55      1404160.85      6951894.49
#Sta/Elev= 30
  2874.6 1937.25  2881.7 1933.75  2885.8 1934.79  2931.0 1932.32  2938.6 1934.49
  2945.3 1932.73  2994.6 1935.04  3137.9 1931.11  3235.7 1929.33  3441.7 1919.75
  3698.4 1914.16  3789.0 1914.17  3803.3 1910.74  3842.2 1910.27  3973.2 1910.91
  4490.4 1902.34  4788.0 1903.46  4944.1 1899.53  4986.3 1890.39  4986.8 1889.89
  5008.2 1890.39  5031.3 1895.00  5116.5 1898.16  5349.1 1898.48  5533.6 1904.71
  5893.6 1906.65  6230.8 1903.38  6405.6 1904.47  6560.9 1906.13  7301.0 1912.70
#Mann=9,-1,0
  2874.6   0.045       0  2885.8   0.035       0  3137.9   0.045       0
  3698.4   0.035       0  3842.2    0.07       0  4986.3    0.07       0
  5008.2    0.07       0  6405.6   0.035       0  6560.9    0.07       0
Bank Sta=4986.3,5008.2
Exp/Cntr=0.3,0.1

Type RM Length L Ch R = 1,26935,522,522,522
BEGIN DESCRIPTION:
Sandy Creek 23.0
END DESCRIPTION:
XS GIS Cut Line= 3
      1400755.03      6953837.98      1402355.00      6952738.00
      1404171.01      6951960.65
#Sta/Elev= 30
  3062.0 1923.20  3299.4 1915.42  3693.4 1908.67  3816.3 1909.20  3831.2 1906.71
  3859.5 1907.10  4270.3 1900.85  4641.2 1898.70  4677.7 1898.94  4745.2 1895.69
  4802.0 1897.62  4816.9 1895.03  4930.8 1894.14  4960.3 1892.60  4964.3 1888.92
  4964.8 1888.42  4986.2 1888.92  4996.2 1892.38  5000.6 1895.99  5012.7 1898.50
  5112.4 1898.30  5293.9 1904.39  5469.8 1904.27  5688.9 1907.89  6053.8 1906.56
  6214.5 1907.30  6518.3 1907.80  6589.1 1909.84  6618.1 1908.36  6979.0 1912.91
#Mann=9,-1,0
  3062.0   0.045       0  3693.4   0.035       0  3859.5    0.07       0
  4641.2   0.035       0  4677.7    0.07       0  4964.3    0.07       0
  4986.2    0.07       0  6053.8   0.035       0  6214.5    0.07       0
Bank Sta=4964.3,4986.2
Exp/Cntr=0.3,0.1

Type RM Length L Ch R = 1,26413,521,521,521
BEGIN DESCRIPTION:
Sandy Creek 22.0
END DESCRIPTION:
XS GIS Cut Line= 3
      1400955.01      6954487.99      1402555.00      6953088.00
      1404955.00      6951688.00
#Sta/Elev= 30
  2868.6 1922.00  2946.9 1918.35  3010.5 1918.78  3081.2 1914.85  3307.5 1912.42
  3407.2 1908.85  4138.9 1902.39  4221.0 1902.43  4480.3 1902.12  4611.6 1902.04
  4709.5 1898.82  4879.5 1897.61  4973.3 1897.66  5002.5 1894.01  5013.0 1889.11
  5013.5 1888.61  5035.0 1889.11  5052.5 1892.69  5119.9 1893.61  5214.6 1900.21
  5360.5 1903.44  5903.5 1905.72  6075.7 1906.47  6428.9 1906.36  6962.7 1912.72
  7070.6 1912.54  7101.6 1910.08  7370.0 1916.66  7576.3 1917.76  7773.1 1922.35
#Mann=10,-1,0
  2868.6   0.045       0  4138.9    0.07       0  4221.0   0.035       0
  4480.3    0.07       0  4709.5   0.035       0  4879.5    0.07       0
  5013.0    0.07       0  5035.0    0.07       0  5903.5   0.035       0
  6075.7    0.07       0
Bank Sta=5013,5035
Exp/Cntr=0.3,0.1

Type RM Length L Ch R = 1,25892,524,524,524
BEGIN DESCRIPTION:
Sandy Creek 21.0
END DESCRIPTION:
XS GIS Cut Line= 3
      1401104.97      6954938.03      1402705.00      6953388.00
      1405104.96      6951788.03
#Sta/Elev= 30
  2773.0 1925.90  3176.2 1911.62  4059.5 1902.16  4286.5 1900.11  4406.2 1902.03
  4679.8 1899.93  4845.2 1895.55  4979.5 1897.88  4986.7 1894.52  4993.6 1895.08
  4997.2 1890.99  5003.2 1889.00  5003.7 1888.50  5025.2 1889.00  5044.3 1892.04
  5131.4 1897.65  5302.7 1897.67  5446.9 1903.88  5549.1 1901.57  5791.9 1901.11
  5969.8 1903.24  6306.2 1903.06  6334.8 1905.17  6471.5 1904.80  6875.6 1910.76
  6940.2 1910.69  6991.3 1907.81  7055.9 1911.07  7589.2 1918.00  7885.1 1924.62
#Mann=8,-1,0
  2773.0   0.045       0  4059.5    0.07       0  4406.2   0.035       0
  4679.8    0.07       0  5003.2    0.07       0  5025.2    0.07       0
  5791.9   0.035       0  5969.8    0.07       0
Bank Sta=5003.2,5025.2
Exp/Cntr=0.3,0.1

Type RM Length L Ch R = 1,25368,599,599,599
BEGIN DESCRIPTION:
Sandy Creek 20.0
END DESCRIPTION:
XS GIS Cut Line= 3
      1401554.98      6955238.03      1403005.00      6953688.00
      1405404.97      6951888.02
#Sta/Elev= 30
  2895.2 1924.97  3036.7 1915.45  3333.7 1905.75  3708.8 1900.81  4091.0 1898.90
  4310.2 1899.28  4387.8 1902.13  4496.9 1897.98  4652.1 1896.37  4788.1 1896.89
  4919.8 1896.63  4947.1 1891.47  4985.4 1890.51  4985.9 1890.01  5007.5 1890.51
  5189.6 1898.65  5245.9 1896.92  5534.1 1899.16  5690.4 1899.69  5981.3 1901.32
  6017.7 1903.59  6154.2 1903.02  6189.6 1905.23  6381.3 1904.61  6617.7 1907.80
  6781.3 1906.33  7675.0 1921.89  7867.7 1926.96  7910.4 1931.21  8017.7 1930.60
#Mann=10,-1,0
  2895.2   0.045       0  4091.0    0.07       0  4496.9   0.035       0
  4652.1    0.07       0  4788.1   0.035       0  4919.8    0.07       0
  4985.4    0.07       0  5007.5    0.07       0  5534.1   0.035       0
  5690.4    0.07       0
Bank Sta=4985.4,5007.5
Exp/Cntr=0.3,0.1

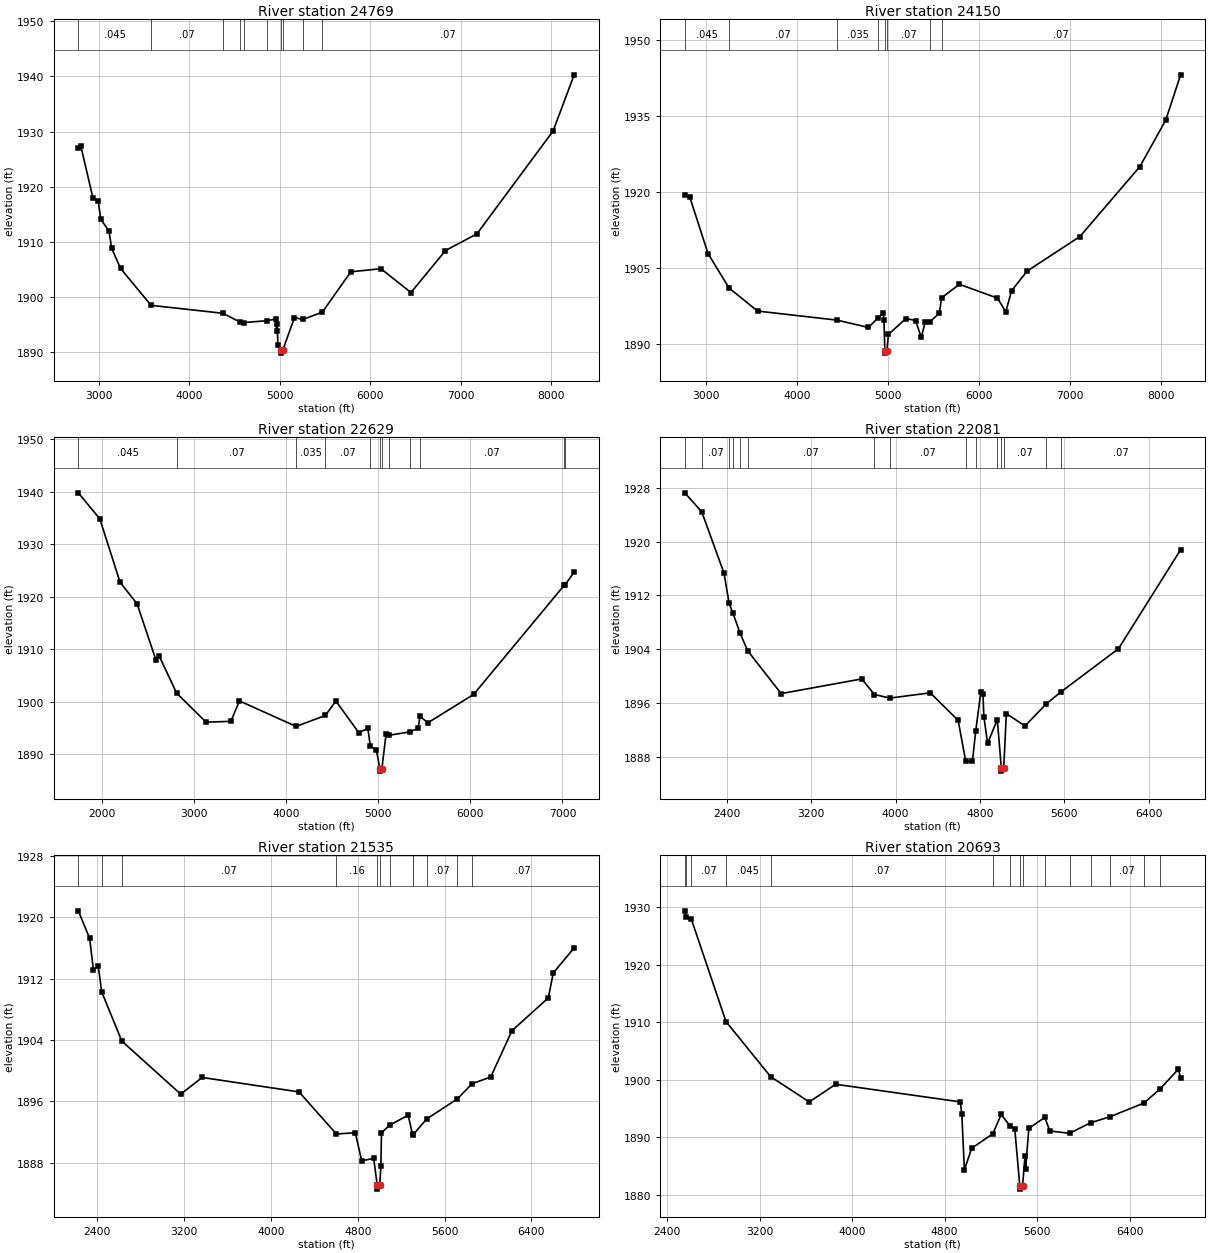
Type RM Length L Ch R = 1,24769,619,619,619
BEGIN DESCRIPTION:
Sandy Creek 19.0
END DESCRIPTION:
XS GIS Cut Line= 3
      1401655.02      6955637.98      1403255.00      6954088.00
      1405655.00      6951888.00
#Sta/Elev= 30
  2773.0 1926.99  2801.2 1927.32  2935.7 1917.85  2992.3 1917.47  3020.5 1914.09
  3112.4 1911.92  3140.7 1908.86  3239.7 1905.15  3577.9 1898.45  4372.4 1897.01
  4564.0 1895.39  4608.0 1895.33  4861.7 1895.67  4958.3 1895.97  4965.3 1893.74
  4972.5 1895.13  4979.4 1891.33  5010.9 1890.28  5011.4 1889.78  5033.0 1890.28
  5163.4 1896.23  5255.3 1895.89  5472.0 1897.22  5786.5 1904.54  6118.9 1905.10
  6451.9 1900.78  6833.5 1908.40  7180.7 1911.42  8023.0 1930.08  8256.4 1940.29
#Mann=10,-1,0
  2773.0   0.045       0  3577.9    0.07       0  4372.4   0.035       0
  4564.0    0.07       0  4608.0   0.035       0  4861.7    0.07       0
  5010.9    0.07       0  5033.0    0.07       0  5255.3   0.035       0
  5472.0    0.07       0
Bank Sta=5010.9,5033
Exp/Cntr=0.3,0.1

Type RM Length L Ch R = 1,24150,1521,1521,1521
BEGIN DESCRIPTION:
Sandy Creek 18.0
END DESCRIPTION:
XS GIS Cut Line= 3
      1401955.00      6955888.00      1403604.64      6954388.36
      1405745.94      6951987.01
#Sta/Elev= 30
  2770.6 1919.32  2827.0 1918.90  3025.7 1907.82  3257.2 1901.00  3570.3 1896.46
  4442.2 1894.67  4788.0 1893.22  4895.6 1895.15  4950.9 1896.06  4958.3 1894.66
  4968.2 1888.65  4968.7 1888.15  4990.3 1888.65  5007.6 1891.84  5199.1 1894.98
  5305.3 1894.59  5368.8 1891.26  5411.4 1894.31  5463.3 1894.37  5567.0 1896.03
  5591.3 1899.07  5786.8 1901.75  6204.9 1899.02  6296.8 1896.32  6360.4 1900.48
  6530.1 1904.34  7111.2 1911.19  7770.0 1925.01  8053.4 1934.16  8217.4 1943.13
#Mann=8,-1,0
  2770.6   0.045       0  3257.2    0.07       0  4442.2   0.035       0
  4895.6    0.07       0  4968.2    0.07       0  4990.3    0.07       0
  5463.3   0.035       0  5591.3    0.07       0
Bank Sta=4968.2,4990.3
Exp/Cntr=0.3,0.1

Type RM Length L Ch R = 1,22629,548,548,548
BEGIN DESCRIPTION:
Sandy Creek 17.0
END DESCRIPTION:
XS GIS Cut Line= 3
      1401954.97      6956638.02      1404355.00      6954438.00
      1405754.98      6952838.02
#Sta/Elev= 30
  1744.8 1939.80  1978.2 1934.84  2197.7 1922.75  2382.1 1918.66  2586.8 1907.96
  2622.6 1908.71  2811.3 1901.63  3131.9 1896.09  3400.8 1896.25  3493.3 1900.14
  4108.6 1895.28  4426.3 1897.37  4540.3 1900.13  4788.2 1894.10  4887.4 1894.90
  4914.2 1891.51  4979.3 1890.84  5017.2 1887.26  5017.7 1886.76  5039.9 1887.26
  5085.5 1893.92  5112.9 1893.58  5339.5 1894.23  5432.9 1894.90  5452.9 1897.19
  5539.2 1895.98  6035.6 1901.38  7021.7 1922.24  7029.8 1922.31  7126.6 1924.69
#Mann=12,-1,0
  1744.8   0.045       0  2811.3    0.07       0  4108.6   0.035       0
  4426.3    0.07       0  4914.2    0.16       0  5017.2    0.07       0
  5039.9    0.16       0  5112.9    0.07       0  5339.5   0.035       0
  5452.9    0.07       0  7021.7   0.035       0  7029.8    0.07       0
Bank Sta=5017.2,5039.9
Exp/Cntr=0.3,0.1

Type RM Length L Ch R = 1,22081,546,546,546
BEGIN DESCRIPTION:
Sandy Creek 16.0
END DESCRIPTION:
XS GIS Cut Line= 3
      1402404.96      6956438.03      1404805.00      6954638.00
      1405905.01      6953337.99
#Sta/Elev= 30
  1999.9 1927.28  2160.3 1924.46  2371.8 1915.34  2419.8 1910.85  2456.3 1909.37
  2522.9 1906.45  2595.4 1903.80  2913.5 1897.40  3678.1 1899.58  3799.0 1897.26
  3944.4 1896.73  4328.1 1897.51  4592.7 1893.42  4664.6 1887.30  4728.1 1887.32
  4759.3 1891.81  4807.2 1897.59  4828.1 1897.41  4836.4 1893.98  4871.8 1890.00
  4964.1 1893.52  5002.2 1886.36  5002.7 1885.86  5025.0 1886.36  5050.0 1894.42
  5226.8 1892.58  5427.4 1895.85  5564.3 1897.61  6113.4 1904.08  6702.9 1918.81
#Mann=15,-1,0
  1999.9   0.045       0  2160.3    0.07       0  2419.8   0.045       0
  2456.3    0.07       0  2522.9   0.045       0  2595.4    0.07       0
  3799.0   0.035       0  3944.4    0.07       0  4664.6   0.033       0
  4759.3    0.16       0  4964.1    0.07       0  5002.2    0.07       0
  5025.0    0.07       0  5427.4   0.035       0  5564.3    0.07       0
Bank Sta=5002.2,5025
Exp/Cntr=0.3,0.1

Type RM Length L Ch R = 1,21535,842,842,842
BEGIN DESCRIPTION:
Sandy Creek 15.0
END DESCRIPTION:
XS GIS Cut Line= 3
      1402705.01      6956437.99      1405105.00      6955038.00
      1405904.99      6953438.02
#Sta/Elev= 30
  2225.7 1920.82  2329.5 1917.24  2364.6 1913.15  2409.7 1913.60  2440.8 1910.27
  2626.3 1903.86  3168.8 1896.95  3366.4 1899.12  4258.7 1897.24  4602.5 1891.76
  4777.2 1891.92  4835.9 1888.26  4946.3 1888.59  4979.0 1885.08  4979.5 1884.58
  5002.0 1885.08  5012.6 1887.60  5018.1 1891.91  5094.2 1892.92  5264.1 1894.20
  5303.9 1891.72  5310.1 1891.67  5433.8 1893.71  5716.2 1896.32  5853.2 1898.31
  6024.4 1899.18  6220.0 1905.21  6555.4 1909.49  6600.2 1912.72  6793.0 1916.00
#Mann=12,-1,0
  2225.7    0.07       0  2440.8   0.045       0  2626.3    0.07       0
  4602.5    0.16       0  4979.0    0.07       0  5002.0    0.16       0
  5094.2   0.045       0  5303.9    0.07       0  5310.1   0.045       0
  5433.8    0.07       0  5716.2   0.035       0  5853.2    0.07       0
Bank Sta=4979,5002
Exp/Cntr=0.3,0.1

Type RM Length L Ch R = 1,20693,577,577,577
BEGIN DESCRIPTION:
Sandy Creek 14.0
END DESCRIPTION:
XS GIS Cut Line= 4
      1402655.01      6956638.00      1404831.03      6955514.82
      1405290.22      6955463.56      1405684.71      6954141.40
#Sta/Elev= 30
  2551.2 1929.36  2562.8 1928.25  2607.7 1927.92  2907.4 1910.14  3294.1 1900.56
  3628.2 1896.17  3856.6 1899.24  4934.9 1896.18  4948.2 1894.08  4970.7 1884.38
  5034.2 1888.14  5216.9 1890.64  5288.8 1893.99  5364.7 1892.04  5406.5 1891.49
  5450.4 1881.53  5450.9 1881.03  5473.5 1881.53  5495.1 1886.71  5500.3 1884.54
  5528.2 1891.59  5666.9 1893.48  5709.6 1891.13  5880.4 1890.73  6062.3 1892.55
  6229.0 1893.59  6524.2 1895.98  6663.4 1898.42  6822.3 1901.85  6841.8 1900.38
#Mann=15,-1,0
  2551.2    0.07       0  2562.8   0.045       0  2607.7    0.07       0
  2907.4   0.045       0  3294.1    0.07       0  5216.9    0.16       0
  5364.7    0.07       0  5450.4    0.07       0  5473.5    0.07       0
  5666.9    0.16       0  5880.4    0.07       0  6062.3   0.045       0
  6229.0    0.07       0  6524.2   0.035       0  6663.4    0.07       0
Bank Sta=5450.4,5473.5
Exp/Cntr=0.3,0.1

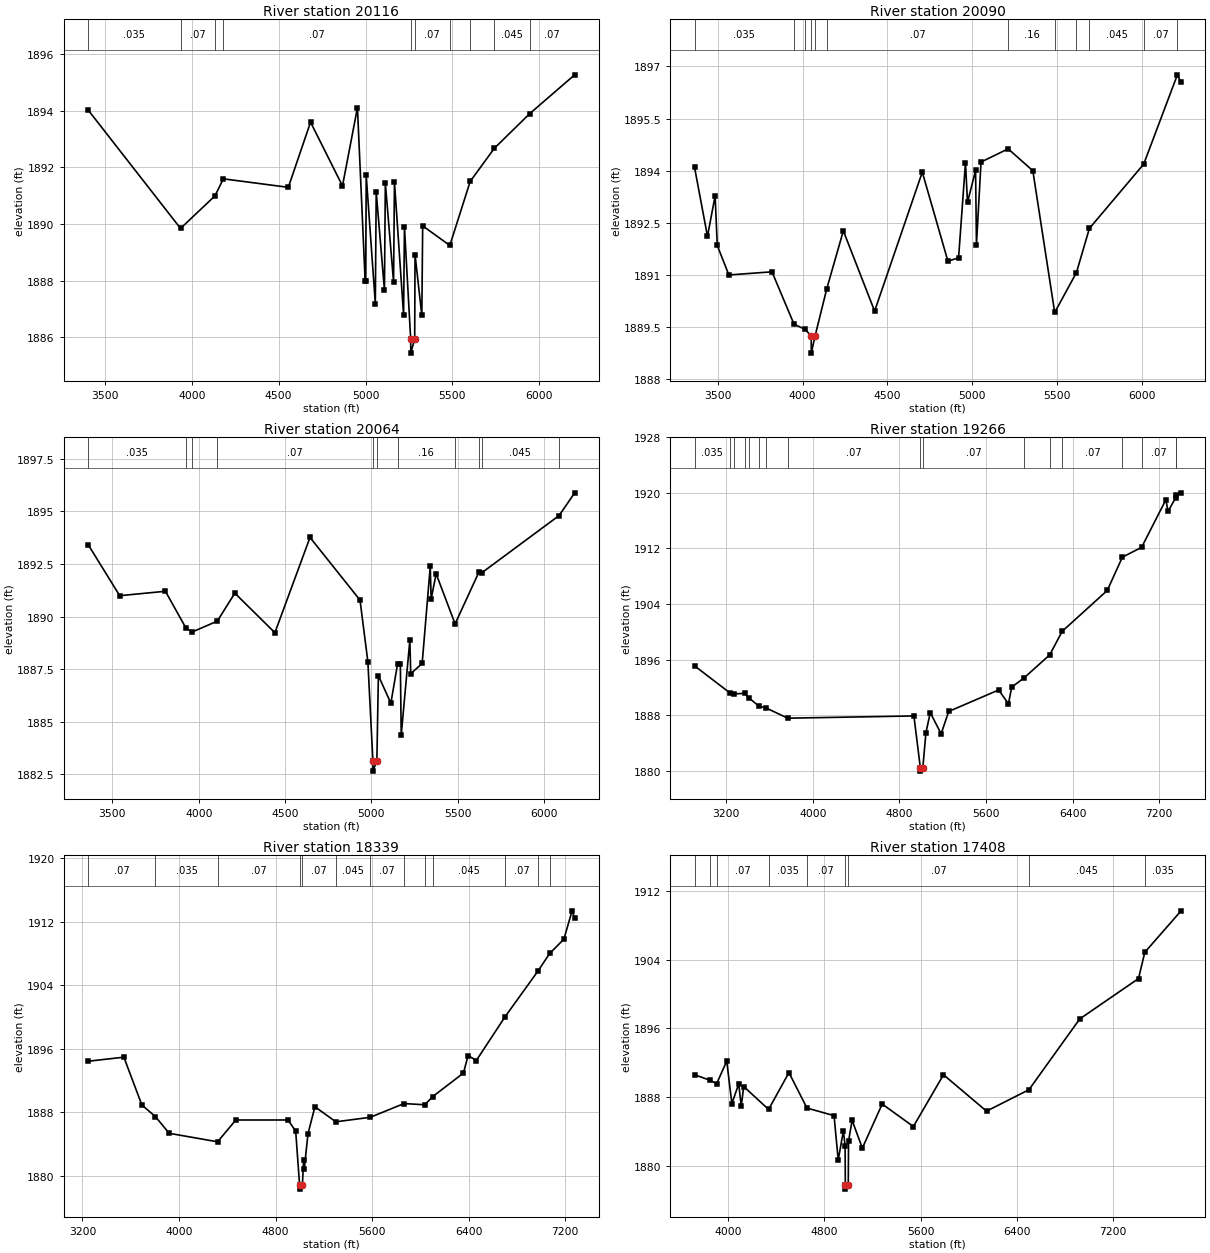
Type RM Length L Ch R = 1,20116,26,26,26
BEGIN DESCRIPTION:
Mapping XS a97d8688
END DESCRIPTION:
XS GIS Cut Line= 5
      1404756.37      6957095.51      1405229.46      6956270.85
      1405359.67      6955637.17      1405442.13      6955198.80
      1405628.77      6954465.28
#Sta/Elev= 30
  3403.3 1894.02  3935.3 1889.84  4133.5 1890.99  4181.7 1891.59  4555.7 1891.29
  4683.6 1893.59  4867.4 1891.34  4953.5 1894.10  4998.0 1887.98  5000.9 1887.98
  5004.0 1891.71  5056.4 1887.19  5061.5 1891.13  5108.9 1887.67  5114.0 1891.44
  5161.4 1887.95  5166.5 1891.48  5219.0 1886.79  5224.1 1889.88  5259.9 1885.94
  5260.4 1885.44  5283.0 1885.94  5285.0 1888.92  5324.0 1886.77  5329.0 1889.93
  5485.3 1889.24  5602.5 1891.50  5741.8 1892.67  5945.0 1893.89  6203.9 1895.26
#Mann=10,-1,0
  3403.3   0.035       0  3935.3    0.07       0  4133.5   0.035       0
  4181.7    0.07       0  5259.9    0.07       0  5283.0    0.07       0
  5485.3   0.045       0  5602.5    0.07       0  5741.8   0.045       0
  5945.0    0.07       0
Bank Sta=5259.9,5283
Exp/Cntr=0.3,0.1

Type RM Length L Ch R = 1,20090,26,26,26
BEGIN DESCRIPTION:
Mapping XS 81b52b2a
END DESCRIPTION:
XS GIS Cut Line= 4
      1404778.08      6957134.56      1405268.52      6956266.51
      1405463.84      6955220.50      1405672.18      6954443.55
#Sta/Elev= 30
  3363.9 1894.10  3440.3 1892.11  3485.2 1893.28  3497.8 1891.85  3566.0 1891.00
  3820.1 1891.09  3950.1 1889.58  4013.0 1889.44  4051.1 1889.25  4051.6 1888.75
  4074.2 1889.25  4143.1 1890.61  4240.3 1892.27  4424.5 1889.96  4705.3 1893.96
  4856.0 1891.40  4918.9 1891.49  4959.6 1894.23  4971.6 1893.09  5019.1 1894.01
  5024.2 1891.87  5051.2 1894.25  5210.9 1894.63  5356.3 1894.00  5485.1 1889.92
  5613.2 1891.07  5689.4 1892.34  6009.3 1894.19  6207.5 1896.76  6229.4 1896.54
#Mann=12,-1,0
  3363.9   0.035       0  3950.1    0.07       0  4013.0   0.035       0
  4051.1    0.07       0  4074.2   0.035       0  4143.1    0.07       0
  5210.9    0.16       0  5485.1   0.045       0  5613.2    0.07       0
  5689.4   0.045       0  6009.3    0.07       0  6207.5   0.035       0
Bank Sta=4051.1,4074.2
Exp/Cntr=0.3,0.1

Type RM Length L Ch R = 1,20064,798,798,798
BEGIN DESCRIPTION:
Mapping XS e9427eb5
END DESCRIPTION:
XS GIS Cut Line= 5
      1404799.75      6957134.60      1405294.56      6956288.21
      1405411.75      6955637.17      1405468.18      6955307.31
      1405693.87      6954495.68
#Sta/Elev= 30
  3359.4 1893.42  3542.4 1890.99  3807.2 1891.20  3927.0 1889.44  3963.9 1889.27
  4107.7 1889.78  4209.4 1891.11  4441.6 1889.23  4644.9 1893.76  4934.7 1890.78
  4980.2 1887.85  5009.2 1883.15  5009.7 1882.65  5032.3 1883.15  5041.1 1887.19
  5113.4 1885.88  5152.6 1887.76  5168.4 1887.73  5173.4 1884.36  5223.4 1888.88
  5228.5 1887.28  5294.7 1887.77  5341.6 1892.38  5346.8 1890.84  5375.8 1892.03
  5485.5 1889.65  5624.7 1892.13  5638.7 1892.07  6088.2 1894.80  6178.4 1895.88
#Mann=11,-1,0
  3359.4   0.035       0  3927.0    0.07       0  3963.9   0.035       0
  4107.7    0.07       0  5009.2    0.07       0  5032.3    0.07       0
  5152.6    0.16       0  5485.5   0.045       0  5624.7    0.07       0
  5638.7   0.045       0  6088.2    0.07       0
Bank Sta=5009.2,5032.3
Exp/Cntr=0.3,0.1

Type RM Length L Ch R = 1,19266,927,927,927
BEGIN DESCRIPTION:
Sandy Creek 12.0
END DESCRIPTION:
XS GIS Cut Line= 4
      1404726.02      6957243.04      1405975.99      6956175.36
      1406055.00      6955738.00      1406255.00      6953338.04
#Sta/Elev= 30
  2906.4 1895.09  3235.3 1891.18  3267.0 1891.05  3368.8 1891.13  3413.0 1890.43
  3502.4 1889.28  3568.1 1889.03  3767.2 1887.56  4933.8 1887.88  4993.2 1880.44
  4993.7 1879.94  5016.3 1880.44  5044.9 1885.46  5085.0 1888.36  5185.4 1885.31
  5255.6 1888.53  5717.2 1891.62  5807.5 1889.62  5837.6 1892.02  5953.4 1893.38
  6188.4 1896.66  6304.9 1900.07  6720.7 1905.94  6860.3 1910.73  7038.3 1912.15
  7262.6 1919.00  7282.6 1917.31  7351.4 1919.25  7356.0 1919.63  7403.0 1919.99
#Mann=17,-1,0
  2906.4   0.035       0  3235.3    0.07       0  3267.0   0.035       0
  3368.8    0.07       0  3413.0   0.035       0  3502.4    0.07       0
  3568.1   0.035       0  3767.2    0.07       0  4993.2    0.07       0
  5016.3    0.07       0  5953.4   0.045       0  6188.4   0.035       0
  6304.9    0.07       0  6860.3   0.035       0  7038.3    0.07       0
  7351.4   0.035       0  7356.0    0.07       0
Bank Sta=4993.2,5016.3
Exp/Cntr=0.3,0.1

Type RM Length L Ch R = 1,18339,931,931,931
BEGIN DESCRIPTION:
Mapping XS 55448423
END DESCRIPTION:
XS GIS Cut Line= 4
      1404988.97      6957439.90      1406292.83      6956288.21
      1407089.78      6955783.48      1407670.63      6954566.27
#Sta/Elev= 30
  3246.9 1894.42  3543.1 1894.93  3692.0 1888.91  3804.2 1887.44  3918.7 1885.33
  4319.5 1884.26  4470.8 1887.01  4903.3 1887.01  4966.8 1885.61  4999.2 1878.79
  4999.7 1878.29  5022.6 1878.79  5032.1 1881.93  5038.0 1880.81  5068.6 1885.27
  5126.2 1888.68  5299.7 1886.78  5584.9 1887.35  5864.2 1889.08  6036.3 1888.93
  6103.0 1889.97  6357.0 1892.93  6395.3 1895.14  6463.4 1894.51  6701.3 1900.02
  6975.0 1905.81  7071.2 1908.01  7188.9 1909.81  7257.0 1913.39  7278.6 1912.46
#Mann=13,-1,0
  3246.9    0.07       0  3804.2   0.035       0  4319.5    0.07       0
  4999.2    0.07       0  5022.6    0.07       0  5299.7   0.045       0
  5584.9    0.07       0  5864.2   0.045       0  6036.3    0.07       0
  6103.0   0.045       0  6701.3    0.07       0  6975.0   0.035       0
  7071.2    0.07       0
Bank Sta=4999.2,5022.6
Exp/Cntr=0.3,0.1

Type RM Length L Ch R = 1,17408,1449,1449,1449
BEGIN DESCRIPTION:
Mapping XS 2bf8199d
END DESCRIPTION:
XS GIS Cut Line= 3
      1405676.50      6957967.91      1406514.18      6956987.00
      1408081.94      6954711.88
#Sta/Elev= 30
  3717.4 1890.60  3846.7 1889.94  3901.6 1889.54  3985.7 1892.19  4028.5 1887.23
  4085.5 1889.52  4106.5 1886.93  4127.3 1889.22  4334.2 1886.55  4503.9 1890.84
  4654.1 1886.71  4879.4 1885.83  4914.5 1880.66  4957.3 1884.06  4971.6 1882.31
  4973.6 1877.77  4974.1 1877.27  4998.1 1877.77  5000.2 1882.82  5029.8 1885.29
  5115.4 1882.05  5280.6 1887.18  5540.3 1884.56  5791.2 1890.59  6149.6 1886.35
  6503.2 1888.85  6926.0 1897.09  7415.6 1901.79  7468.0 1904.85  7770.3 1909.68
#Mann=9,-1,0
  3717.4    0.07       0  3846.7   0.035       0  3901.6    0.07       0
  4334.2   0.035       0  4654.1    0.07       0  4973.6    0.07       0
  4998.1    0.07       0  6503.2   0.045       0  7468.0   0.035       0
Bank Sta=4973.6,4998.1
Exp/Cntr=0.3,0.1

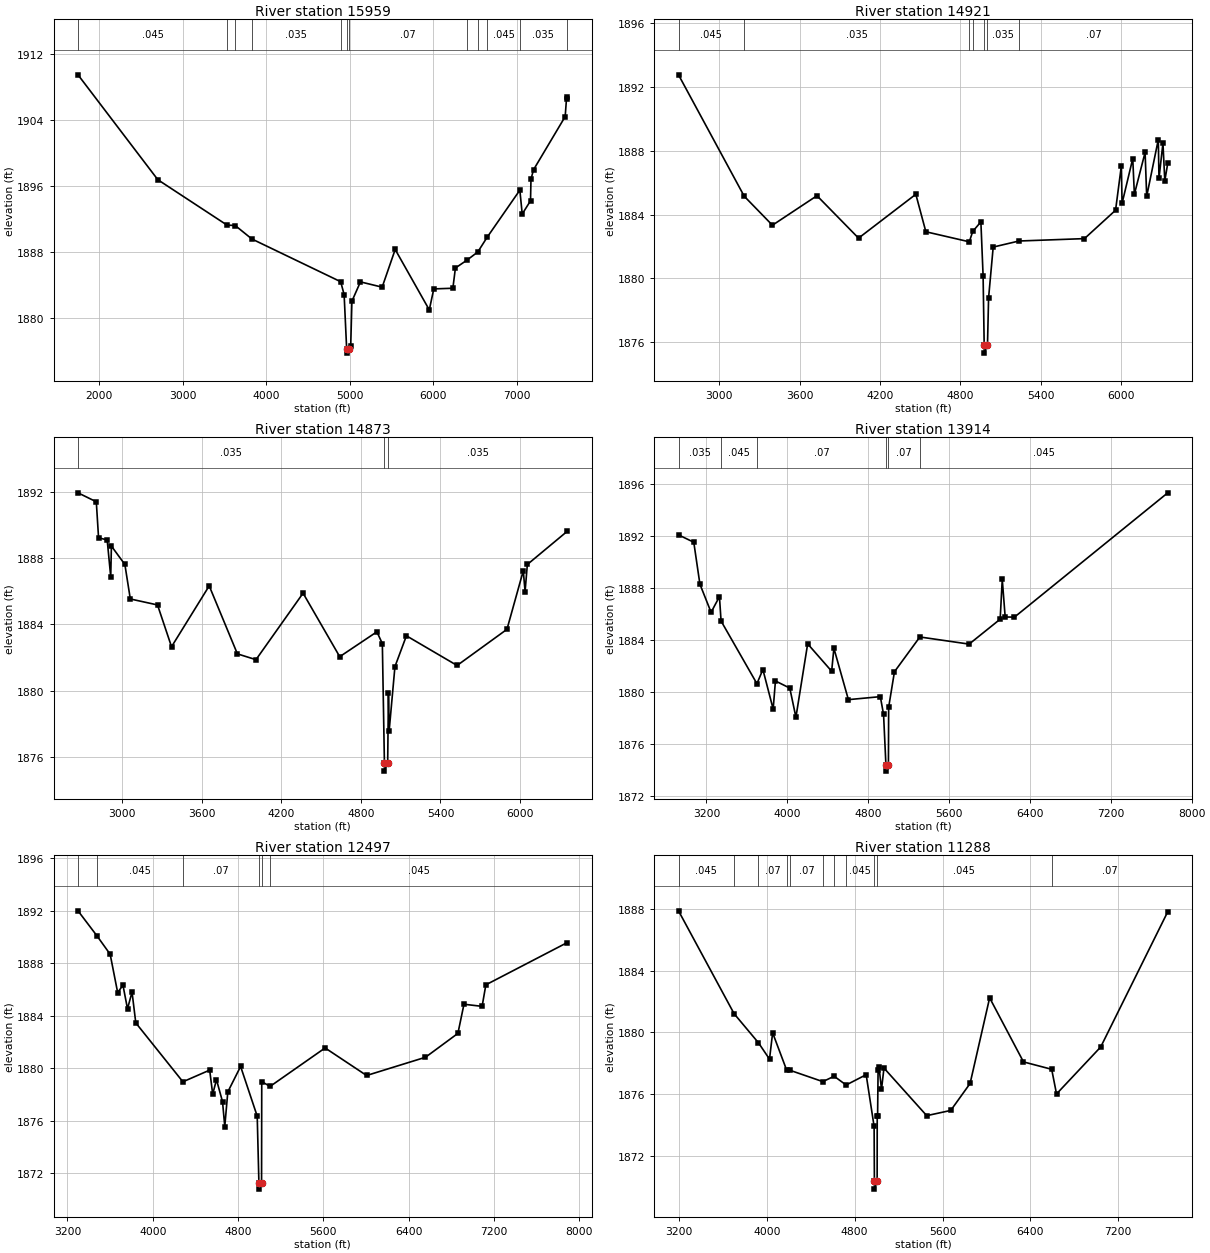
Type RM Length L Ch R = 1,15959,1038,1038,1038
BEGIN DESCRIPTION:
Sandy Creek 10.0
END DESCRIPTION:
XS GIS Cut Line= 3
      1404805.03      6959437.97      1407205.00      6957238.00
      1408400.44      6954929.49
#Sta/Elev= 30
  1749.0 1909.46  2704.4 1896.77  3532.5 1891.28  3630.4 1891.23  3829.8 1889.60
  4893.0 1884.43  4934.1 1882.87  4964.4 1876.29  4964.9 1875.79  4989.0 1876.29
  5013.0 1876.69  5027.2 1882.07  5129.3 1884.41  5389.3 1883.77  5545.3 1888.33
  5953.5 1881.02  6007.0 1883.56  6235.6 1883.64  6266.0 1886.09  6403.1 1887.03
  6533.9 1888.03  6644.7 1889.79  7037.3 1895.51  7065.5 1892.62  7164.9 1894.22
  7170.5 1896.83  7200.7 1897.97  7579.8 1904.41  7596.8 1906.75  7604.4 1906.57
#Mann=12,-1,0
  1749.0   0.045       0  3532.5    0.07       0  3630.4   0.045       0
  3829.8   0.035       0  4893.0    0.07       0  4964.4    0.07       0
  4989.0    0.07       0  6403.1   0.045       0  6533.9    0.07       0
  6644.7   0.045       0  7037.3   0.035       0  7596.8    0.07       0
Bank Sta=4964.4,4989
Exp/Cntr=0.3,0.1

Type RM Length L Ch R = 1,14921,48,48,48
BEGIN DESCRIPTION:
Mapping XS 094f19e9
END DESCRIPTION:
XS GIS Cut Line= 3
      1407156.54      6959786.48      1407655.68      6957559.91
      1407955.16      6956223.08
#Sta/Elev= 30
  2695.8 1892.77  3186.1 1885.16  3396.8 1883.34  3729.3 1885.19  4039.6 1882.53
  4467.2 1885.28  4542.1 1882.93  4866.4 1882.30  4891.9 1882.95  4952.8 1883.55
  4969.3 1880.18  4977.5 1875.82  4978.0 1875.32  5002.1 1875.82  5010.3 1878.79
  5044.7 1881.97  5236.9 1882.35  5725.9 1882.50  5958.1 1884.28  6001.5 1887.07
  6006.6 1884.71  6086.4 1887.52  6098.5 1885.28  6178.6 1887.91  6190.4 1885.15
  6277.1 1888.71  6282.2 1886.27  6311.8 1888.49  6325.6 1886.13  6347.6 1887.22
#Mann=7,-1,0
  2695.8   0.045       0  3186.1   0.035       0  4866.4    0.07       0
  4891.9   0.035       0  4977.5   0.035       0  5002.1   0.035       0
  5236.9    0.07       0
Bank Sta=4977.5,5002.1
Exp/Cntr=0.3,0.1

Type RM Length L Ch R = 1,14873,959,959,959
BEGIN DESCRIPTION:
Mapping XS f3013257
END DESCRIPTION:
XS GIS Cut Line= 3
      1407195.60      6959812.56      1407699.08      6957577.27
      1407998.57      6956214.38
#Sta/Elev= 30
  2668.6 1891.93  2806.5 1891.39  2823.5 1889.22  2888.5 1889.09  2915.2 1886.87
  2920.3 1888.72  3021.8 1887.61  3062.8 1885.53  3267.8 1885.17  3373.4 1882.65
  3657.3 1886.32  3869.7 1882.22  4009.7 1881.87  4364.6 1885.88  4640.9 1882.05
  4920.9 1883.55  4962.0 1882.84  4977.6 1875.65  4978.1 1875.15  5002.2 1875.65
  5008.0 1879.88  5013.1 1877.56  5056.9 1881.45  5143.4 1883.31  5525.3 1881.52
  5901.1 1883.70  6024.0 1887.23  6037.6 1885.98  6054.7 1887.61  6355.3 1889.61
#Mann=3,-1,0
  2668.6   0.035       0  4977.6   0.035       0  5002.2   0.035       0
Bank Sta=4977.6,5002.2
Exp/Cntr=0.3,0.1

Type RM Length L Ch R = 1,13914,1417,1417,1417
BEGIN DESCRIPTION:
Sandy Creek 7.0
END DESCRIPTION:
XS GIS Cut Line= 3
      1407200.80      6959828.17      1408160.24      6957987.51
      1409898.75      6955839.50
#Sta/Elev= 30
  2924.3 1892.11  3075.4 1891.54  3136.0 1888.31  3246.5 1886.14  3329.2 1887.35
  3345.2 1885.47  3699.9 1880.64  3759.0 1881.73  3860.5 1878.68  3883.0 1880.85
  4025.0 1880.30  4085.6 1878.05  4201.7 1883.71  4439.1 1881.60  4461.2 1883.37
  4604.6 1879.41  4920.5 1879.64  4952.5 1878.27  4975.7 1874.40  4976.2 1873.90
  5000.6 1874.40  5002.9 1878.82  5060.2 1881.56  5311.6 1884.24  5798.9 1883.69
  6105.8 1885.61  6126.6 1888.67  6155.4 1885.78  6247.3 1885.77  7763.4 1895.35
#Mann=6,-1,0
  2924.3   0.035       0  3345.2   0.045       0  3699.9    0.07       0
  4975.7    0.07       0  5000.6    0.07       0  5311.6   0.045       0
Bank Sta=4975.7,5000.6
Exp/Cntr=0.3,0.1

Type RM Length L Ch R = 1,12497,1209,1209,1209
BEGIN DESCRIPTION:
Mapping XS 5b1feb64
END DESCRIPTION:
XS GIS Cut Line= 3
      1407204.30      6959853.39      1408440.40      6958693.68
      1410395.25      6956559.66
#Sta/Elev= 30
  3298.7 1891.98  3475.9 1890.08  3600.3 1888.67  3670.7 1885.75  3720.5 1886.31
  3763.0 1884.51  3805.5 1885.79  3840.7 1883.44  4282.7 1878.95  4533.8 1879.84
  4562.1 1878.01  4597.7 1879.11  4654.4 1877.43  4675.4 1875.54  4703.8 1878.18
  4823.9 1880.12  4979.7 1876.33  4995.5 1871.27  4996.0 1870.77  5020.5 1871.27
  5022.2 1878.96  5100.7 1878.60  5616.6 1881.53  6005.7 1879.43  6558.2 1880.82
  6862.2 1882.64  6919.0 1884.86  7089.2 1884.70  7124.3 1886.34  7887.7 1889.56
#Mann=6,-1,0
  3298.7   0.035       0  3475.9   0.045       0  4282.7    0.07       0
  4995.5    0.07       0  5020.5    0.07       0  5100.7   0.045       0
Bank Sta=4995.5,5020.5
Exp/Cntr=0.3,0.1

Type RM Length L Ch R = 1,11288,1389,1389,1389
BEGIN DESCRIPTION:
Mapping XS b62421e1
END DESCRIPTION:
XS GIS Cut Line= 3
      1407558.46      6960138.12      1409072.34      6959145.07
      1411378.17      6957852.14
#Sta/Elev= 30
  3196.5 1887.89  3702.7 1881.21  3924.5 1879.32  4024.9 1878.26  4053.4 1879.97
  4182.0 1877.53  4213.9 1877.53  4510.6 1876.80  4613.4 1877.15  4722.5 1876.58
  4905.0 1877.25  4977.3 1873.89  4979.9 1870.32  4980.4 1869.82  5004.9 1870.32
  5005.6 1874.60  5009.1 1874.60  5013.5 1877.57  5021.5 1877.77  5044.5 1876.30
  5067.1 1877.68  5456.3 1874.59  5675.0 1874.93  5851.1 1876.68  6029.1 1882.24
  6337.3 1878.08  6593.9 1877.60  6638.1 1876.00  7040.3 1879.05  7650.6 1887.83
#Mann=11,-1,0
  3196.5   0.045       0  3702.7   0.035       0  3924.5    0.07       0
  4182.0   0.045       0  4213.9    0.07       0  4510.6   0.045       0
  4613.4    0.07       0  4722.5   0.045       0  4979.9   0.045       0
  5004.9   0.045       0  6593.9    0.07       0
Bank Sta=4979.9,5004.9
Exp/Cntr=0.3,0.1

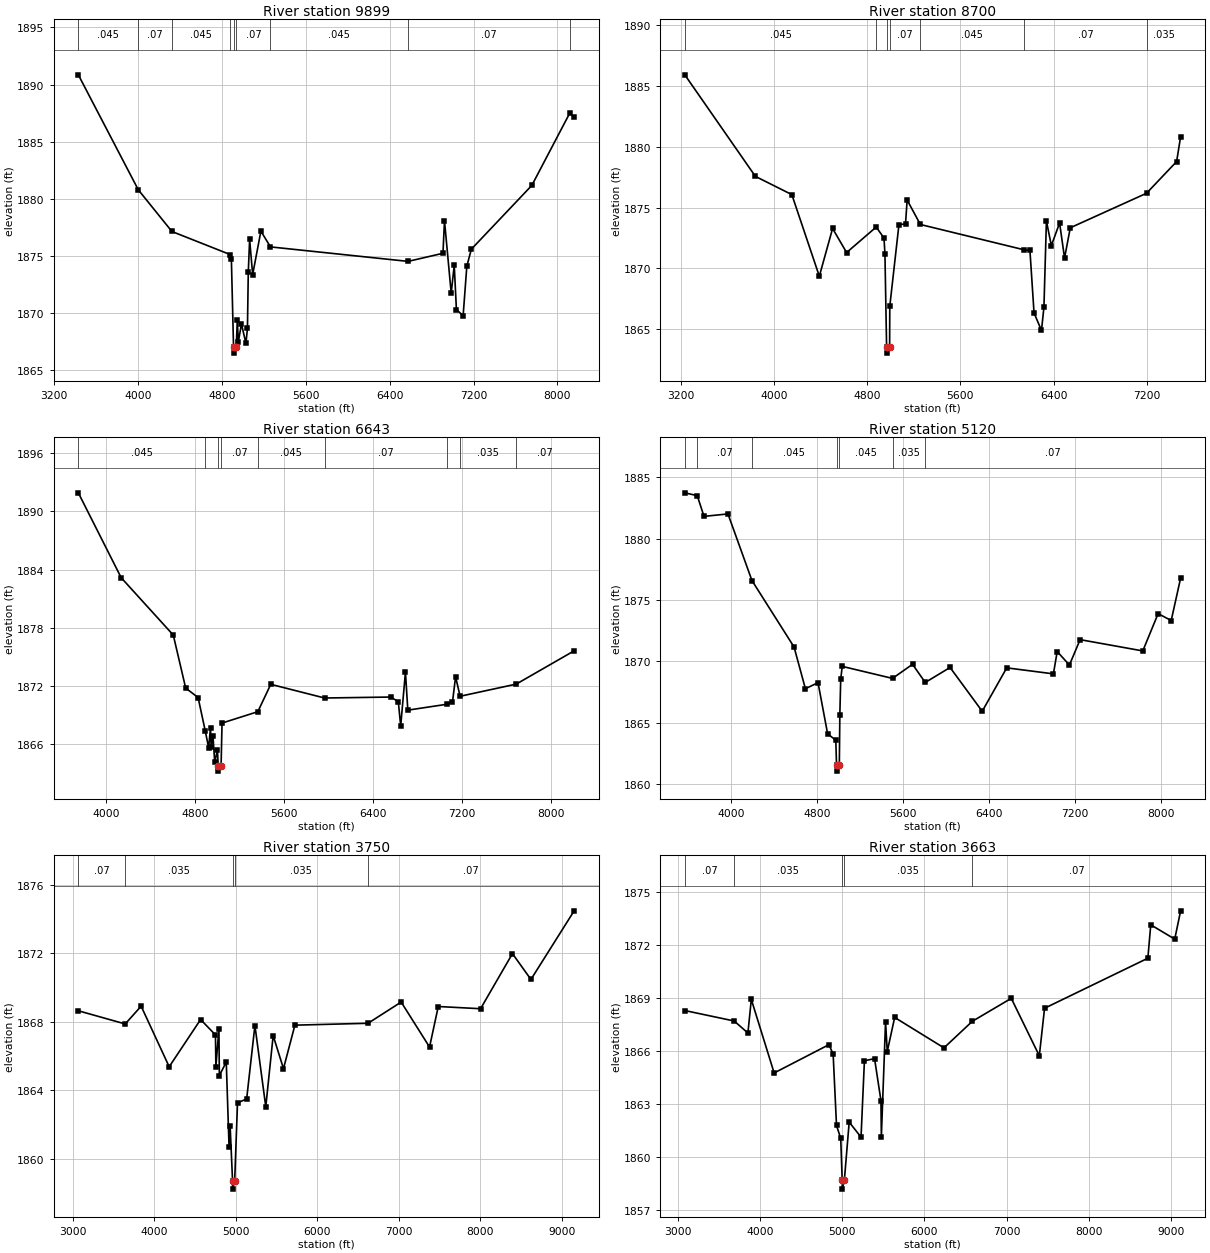
Type RM Length L Ch R = 1,9899,1199,1199,1199
BEGIN DESCRIPTION:
Mapping XS b2128afa
END DESCRIPTION:
XS GIS Cut Line= 3
      1407688.97      6960587.20      1409110.42      6959904.58
      1411579.96      6957945.01
#Sta/Elev= 30
  3429.5 1890.85  4001.7 1880.77  4322.1 1877.12  4877.5 1875.10  4889.2 1874.73
  4910.0 1866.96  4910.5 1866.46  4935.8 1866.96  4945.6 1869.32  4956.0 1867.46
  4985.3 1869.01  5028.2 1867.32  5042.6 1868.63  5050.5 1873.54  5063.4 1876.42
  5092.3 1873.34  5170.8 1877.15  5262.1 1875.77  6574.7 1874.50  6907.6 1875.21
  6922.0 1878.07  6986.1 1871.71  7015.0 1874.16  7035.8 1870.28  7099.9 1869.74
  7135.1 1874.08  7178.4 1875.57  7755.2 1881.16  8117.2 1887.50  8158.9 1887.13
#Mann=9,-1,0
  3429.5   0.045       0  4001.7    0.07       0  4322.1   0.045       0
  4877.5    0.07       0  4910.0    0.07       0  4935.8    0.07       0
  5262.1   0.045       0  6574.7    0.07       0  8117.2   0.035       0
Bank Sta=4910,4935.8
Exp/Cntr=0.3,0.1

Type RM Length L Ch R = 1,8700,2057,2057,2057
BEGIN DESCRIPTION:
Mapping XS 702d8b00
END DESCRIPTION:
XS GIS Cut Line= 3
      1408433.43      6961277.03      1409822.34      6960186.74
      1411607.39      6958451.65
#Sta/Elev= 30
  3235.2 1885.93  3841.0 1877.57  4153.8 1876.07  4389.7 1869.35  4503.5 1873.28
  4623.8 1871.30  4878.0 1873.40  4944.7 1872.49  4952.8 1871.19  4967.0 1863.52
  4967.5 1863.02  4992.9 1863.52  4994.4 1866.88  5072.7 1873.58  5129.3 1873.67
  5143.4 1875.62  5256.7 1873.61  6149.3 1871.52  6197.1 1871.47  6232.3 1866.33
  6296.1 1864.89  6317.2 1866.79  6338.5 1873.89  6381.0 1871.87  6451.7 1873.74
  6494.1 1870.85  6543.5 1873.34  7197.6 1876.18  7455.9 1878.79  7490.3 1880.84
#Mann=7,-1,0
  3235.2   0.045       0  4878.0    0.07       0  4967.0    0.07       0
  4992.9    0.07       0  5256.7   0.045       0  6149.3    0.07       0
  7197.6   0.035       0
Bank Sta=4967,4992.9
Exp/Cntr=0.3,0.1

Type RM Length L Ch R = 1,6643,1523,1523,1523
BEGIN DESCRIPTION:
Mapping XS b91c743d
END DESCRIPTION:
XS GIS Cut Line= 4
      1408489.05      6961797.83      1409607.06      6961235.35
      1410511.52      6960863.58      1411666.08      6958955.51
#Sta/Elev= 30
  3752.3 1891.91  4137.6 1883.17  4606.3 1877.26  4717.9 1871.80  4829.5 1870.83
  4893.8 1867.39  4924.4 1865.66  4941.1 1867.73  4946.7 1865.74  4963.4 1866.84
  4979.1 1864.15  5003.8 1865.45  5010.2 1863.75  5010.7 1863.25  5036.2 1863.75
  5044.8 1868.20  5366.6 1869.37  5483.1 1872.19  5967.2 1870.78  6562.5 1870.88
  6630.4 1870.40  6651.7 1867.90  6694.4 1873.45  6715.8 1869.53  7070.2 1870.14
  7117.3 1870.34  7145.4 1872.97  7186.0 1870.96  7690.8 1872.21  8211.9 1875.64
#Mann=9,-1,0
  3752.3   0.045       0  4893.8    0.07       0  5010.2    0.07       0
  5036.2    0.07       0  5366.6   0.045       0  5967.2    0.07       0
  7070.2   0.045       0  7186.0   0.035       0  7690.8    0.07       0
Bank Sta=5010.2,5036.2
Exp/Cntr=0.3,0.1

Type RM Length L Ch R = 1,5120,1370,1370,1370
BEGIN DESCRIPTION:
Mapping XS 903d4e7d
END DESCRIPTION:
XS GIS Cut Line= 3
      1409023.77      6962332.55      1410336.23      6961770.07
      1412830.99      6959790.41
#Sta/Elev= 30
  3570.7 1883.73  3686.5 1883.50  3749.4 1881.81  3972.4 1882.01  4195.3 1876.58
  4587.1 1871.16  4692.6 1867.76  4810.2 1868.25  4899.4 1864.08  4975.5 1863.56
  4982.2 1861.54  4982.7 1861.04  5008.3 1861.54  5013.1 1865.63  5021.1 1868.53
  5035.3 1869.58  5503.3 1868.60  5689.2 1869.75  5807.7 1868.27  6038.5 1869.49
  6337.5 1865.92  6565.7 1869.46  6999.9 1868.97  7035.1 1870.79  7148.9 1869.69
  7248.2 1871.76  7831.4 1870.84  7974.0 1873.88  8095.8 1873.32  8183.4 1876.78
#Mann=7,-1,0
  3570.7   0.045       0  3686.5    0.07       0  4195.3   0.045       0
  4982.2   0.045       0  5008.3   0.045       0  5503.3   0.035       0
  5807.7    0.07       0
Bank Sta=4982.2,5008.3
Exp/Cntr=0.3,0.1

Type RM Length L Ch R = 1,3750,87,87,87
BEGIN DESCRIPTION:
Mapping XS a8cdeed6
END DESCRIPTION:
XS GIS Cut Line= 4
      1409995.95      6964797.88      1410433.45      6962929.79
      1410747.21      6961574.62      1412887.21      6959814.50
#Sta/Elev= 30
  3070.9 1868.65  3645.9 1867.88  3841.1 1868.92  4185.1 1865.38  4570.3 1868.14
  4752.6 1867.24  4757.7 1865.38  4795.0 1867.60  4800.2 1864.86  4885.1 1865.66
  4919.5 1860.67  4932.7 1861.89  4962.1 1858.73  4962.6 1858.23  4988.3 1858.73
  5022.9 1863.27  5135.1 1863.50  5236.4 1867.79  5369.6 1863.04  5460.2 1867.20
  5586.7 1865.27  5726.6 1867.81  6623.7 1867.92  7030.0 1869.16  7378.0 1866.53
  7484.9 1868.90  8003.6 1868.77  8394.6 1871.99  8621.3 1870.48  9151.4 1874.49
#Mann=5,-1,0
  3070.9    0.07       0  3645.9   0.035       0  4962.1   0.035       0
  4988.3   0.035       0  6623.7    0.07       0
Bank Sta=4962.1,4988.3
Exp/Cntr=0.3,0.1

Type RM Length L Ch R = 1,3663,396,396,396
BEGIN DESCRIPTION:
Mapping XS 0134c0e4
END DESCRIPTION:
XS GIS Cut Line= 4
      1410065.39      6964846.49      1410489.01      6963020.07
      1410850.12      6961533.96      1412877.04      6959858.82
#Sta/Elev= 30
  3084.0 1868.29  3684.5 1867.70  3852.0 1867.02  3893.4 1868.92  4171.2 1864.76
  4837.8 1866.36  4889.2 1865.83  4930.2 1861.79  4981.6 1861.06  4999.4 1858.69
  4999.9 1858.19  5025.6 1858.69  5084.5 1861.98  5228.6 1861.13  5269.8 1865.45
  5393.3 1865.57  5470.9 1863.20  5476.0 1861.16  5527.0 1867.66  5547.6 1865.97
  5637.9 1867.90  6238.0 1866.18  6582.5 1867.68  7056.9 1868.98  7398.2 1865.73
  7462.0 1868.42  8719.1 1871.25  8754.3 1873.14  9046.1 1872.33  9117.8 1873.93
#Mann=5,-1,0
  3084.0    0.07       0  3684.5   0.035       0  4999.4   0.035       0
  5025.6   0.035       0  6582.5    0.07       0
Bank Sta=4999.4,5025.6
Exp/Cntr=0.3,0.1