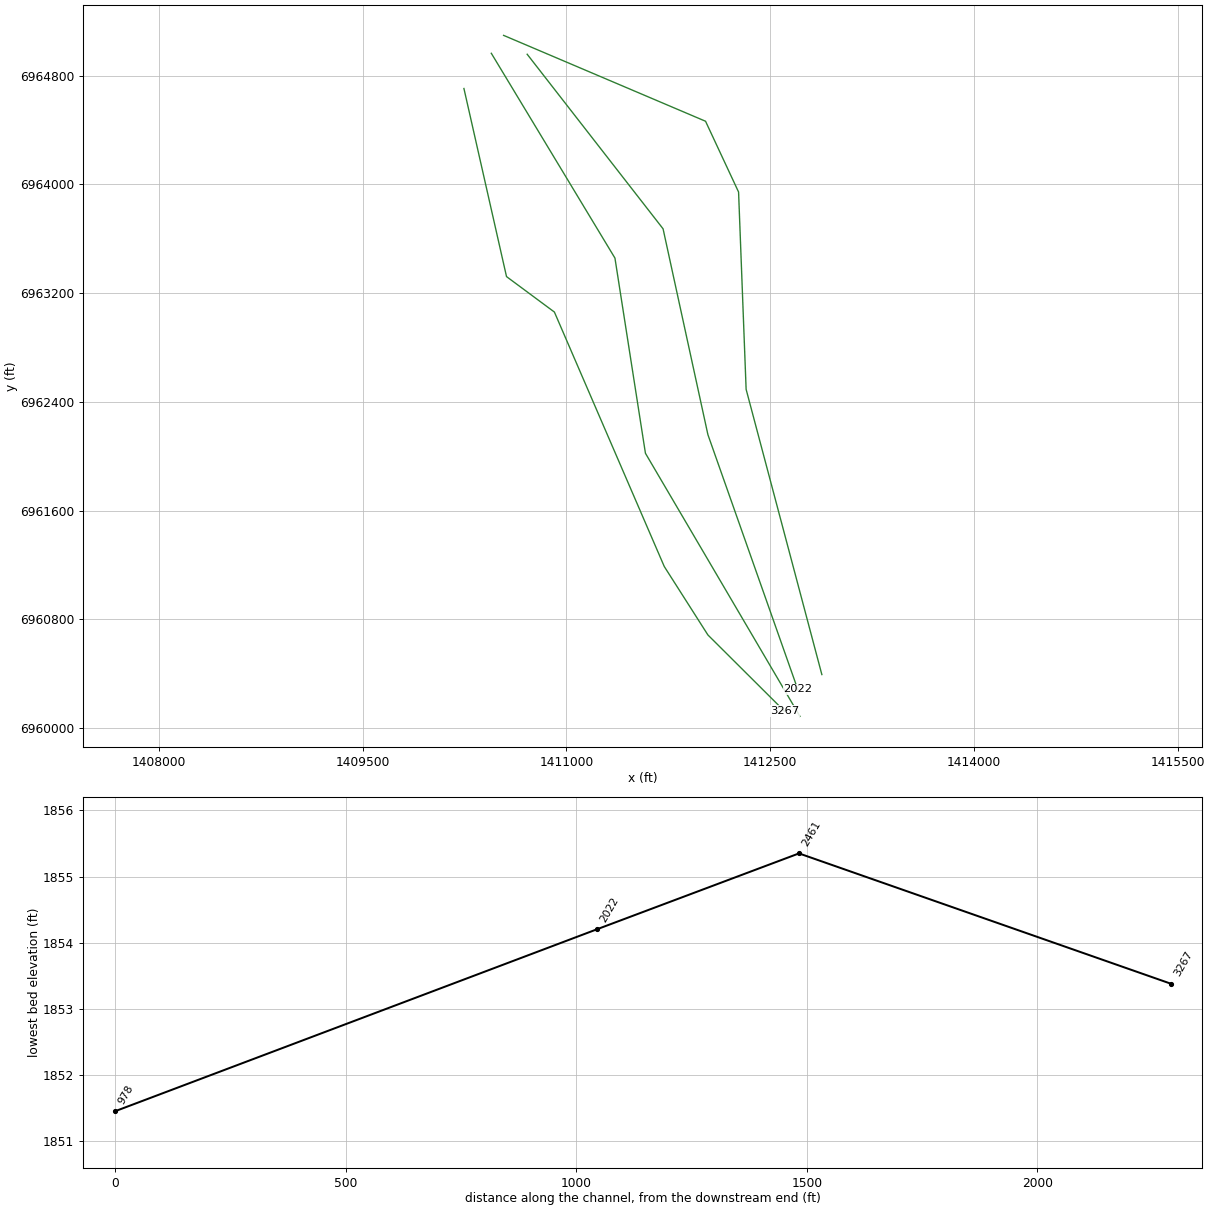
HEC-RAS study Sandy Creek.prj: Sandy Creek Base Level Engineering

--- Sandy Creek.g01 (geometry) --- (continued)

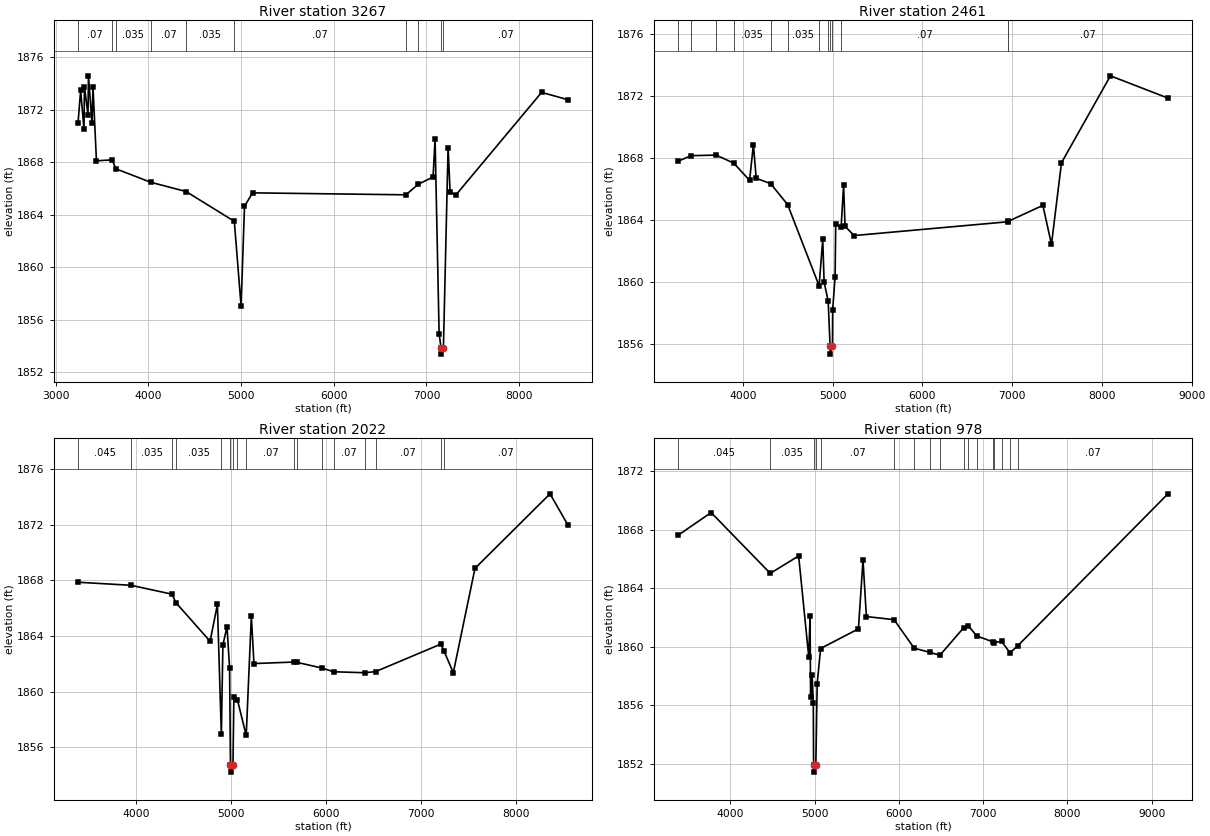
Type RM Length L Ch R = 1,3267,806,806,806
BEGIN DESCRIPTION:
Mapping XS 034768a2
END DESCRIPTION:
XS GIS Cut Line= 6
      1410245.81      6964705.38      1410559.17      6963321.40
      1410911.61      6963060.29      1411720.06      6961187.86
      1412041.12      6960684.33      1412603.61      6960124.45
#Sta/Elev= 30
  3239.6 1870.99  3267.7 1873.46  3303.7 1870.50  3308.8 1873.75  3346.9 1871.59
  3352.0 1874.57  3390.0 1870.97  3401.0 1873.72  3438.3 1868.10  3607.4 1868.17
  3648.3 1867.49  4022.5 1866.47  4406.0 1865.76  4926.5 1863.49  4999.6 1857.04
  5036.3 1864.63  5123.1 1865.66  6779.3 1865.51  6908.3 1866.30  7071.7 1866.87
  7093.5 1869.75  7137.1 1854.95  7157.4 1853.88  7157.9 1853.38  7183.6 1853.88
  7234.0 1869.11  7255.6 1865.74  7314.9 1865.47  8243.6 1873.31  8528.0 1872.75
#Mann=10,-1,0
  3239.6    0.07       0  3607.4   0.045       0  3648.3   0.035       0
  4022.5    0.07       0  4406.0   0.035       0  4926.5    0.07       0
  6779.3   0.035       0  6908.3    0.07       0  7157.4    0.07       0
  7183.6    0.07       0
Bank Sta=7157.4,7183.6
Exp/Cntr=0.3,0.1

Type RM Length L Ch R = 1,2461,439,439,439
BEGIN DESCRIPTION:
Mapping XS deffcda5
END DESCRIPTION:
XS GIS Cut Line= 4
      1410447.35      6964964.51      1411357.06      6963457.57
      1411581.45      6962021.18      1412718.18      6960085.41
#Sta/Elev= 30
  3276.2 1867.81  3421.0 1868.17  3700.7 1868.21  3896.9 1867.69  4073.5 1866.58
  4116.2 1868.88  4147.2 1866.71  4307.0 1866.37  4497.4 1865.01  4848.4 1859.76
  4888.6 1862.76  4904.1 1859.99  4949.4 1858.78  4970.5 1855.85  4971.0 1855.35
  4997.0 1855.85  4999.2 1858.21  5026.4 1860.35  5033.3 1863.74  5093.8 1863.59
  5121.1 1866.27  5137.2 1863.61  5238.4 1863.01  6949.5 1863.90  6956.1 1863.93
  7341.4 1864.96  7437.2 1862.44  7548.6 1867.71  8094.3 1873.33  8735.1 1871.89
#Mann=13,-1,0
  3276.2   0.045       0  3421.0    0.07       0  3700.7   0.045       0
  3896.9   0.035       0  4307.0    0.07       0  4497.4   0.035       0
  4848.4    0.07       0  4949.4   0.035       0  4970.5   0.035       0
  4997.0   0.035       0  5093.8    0.07       0  6949.5   0.035       0
  6956.1    0.07       0
Bank Sta=4970.5,4997
Exp/Cntr=0.3,0.1

Type RM Length L Ch R = 1,2022,1044,1044,1044
BEGIN DESCRIPTION:
Mapping XS cfad7f4b
END DESCRIPTION:
XS GIS Cut Line= 4
      1410711.25      6964957.55      1411711.23      6963672.85
      1412041.12      6962158.29      1412702.57      6960283.32
#Sta/Elev= 30
  3384.3 1867.86  3942.9 1867.64  4375.2 1867.00  4416.4 1866.39  4776.9 1863.61
  4853.8 1866.26  4895.6 1856.92  4911.7 1863.34  4955.1 1864.66  4982.3 1861.71
  4991.6 1854.70  4992.1 1854.20  5018.1 1854.70  5027.5 1859.61  5064.2 1859.42
  5157.7 1856.84  5211.7 1865.41  5239.4 1862.01  5666.4 1862.12  5697.4 1862.09
  5961.4 1861.68  6078.3 1861.42  6406.6 1861.35  6521.4 1861.43  7210.4 1863.41
  7242.8 1862.92  7341.3 1861.35  7570.1 1868.86  8361.3 1874.22  8550.6 1871.97
#Mann=17,-1,0
  3384.3   0.045       0  3942.9   0.035       0  4375.2    0.07       0
  4416.4   0.035       0  4895.6    0.07       0  4991.6    0.07       0
  5018.1    0.07       0  5064.2   0.035       0  5157.7    0.07       0
  5666.4   0.035       0  5697.4    0.07       0  5961.4   0.035       0
  6078.3    0.07       0  6406.6   0.035       0  6521.4    0.07       0
  7210.4   0.035       0  7242.8    0.07       0
Bank Sta=4991.6,5018.1
Exp/Cntr=0.3,0.1

Type RM Length L Ch R = 1,978,0,0,0
BEGIN DESCRIPTION:
Mapping XS 0646b21f
END DESCRIPTION:
XS GIS Cut Line= 5
      1410537.66      6965096.44      1412023.73      6964464.51
      1412266.79      6963943.68      1412322.37      6962491.62
      1412879.61      6960392.86
#Sta/Elev= 30
  3380.1 1867.62  3773.0 1869.17  4475.0 1865.02  4811.6 1866.21  4931.1 1859.34
  4947.6 1862.10  4953.0 1856.61  4971.2 1858.11  4985.5 1856.19  4988.9 1851.95
  4989.4 1851.45  5015.4 1851.95  5031.6 1857.49  5072.4 1859.89  5520.8 1861.23
  5575.4 1865.92  5615.4 1862.07  5943.7 1861.86  6183.1 1859.91  6367.0 1859.63
  6487.6 1859.43  6770.5 1861.31  6825.9 1861.45  6923.6 1860.75  7118.8 1860.34
  7127.0 1860.28  7219.3 1860.38  7319.8 1859.60  7409.3 1860.06  9194.3 1870.45
#Mann=17,-1,0
  3380.1   0.045       0  4475.0   0.035       0  4988.9   0.035       0
  5015.4   0.035       0  5072.4    0.07       0  5943.7   0.035       0
  6183.1    0.07       0  6367.0   0.035       0  6487.6    0.07       0
  6770.5   0.035       0  6825.9    0.07       0  6923.6   0.035       0
  7118.8    0.07       0  7127.0   0.035       0  7219.3    0.07       0
  7319.8   0.035       0  7409.3    0.07       0
Bank Sta=4988.9,5015.4
Exp/Cntr=0.3,0.1

Chan Stop Cuts=-1