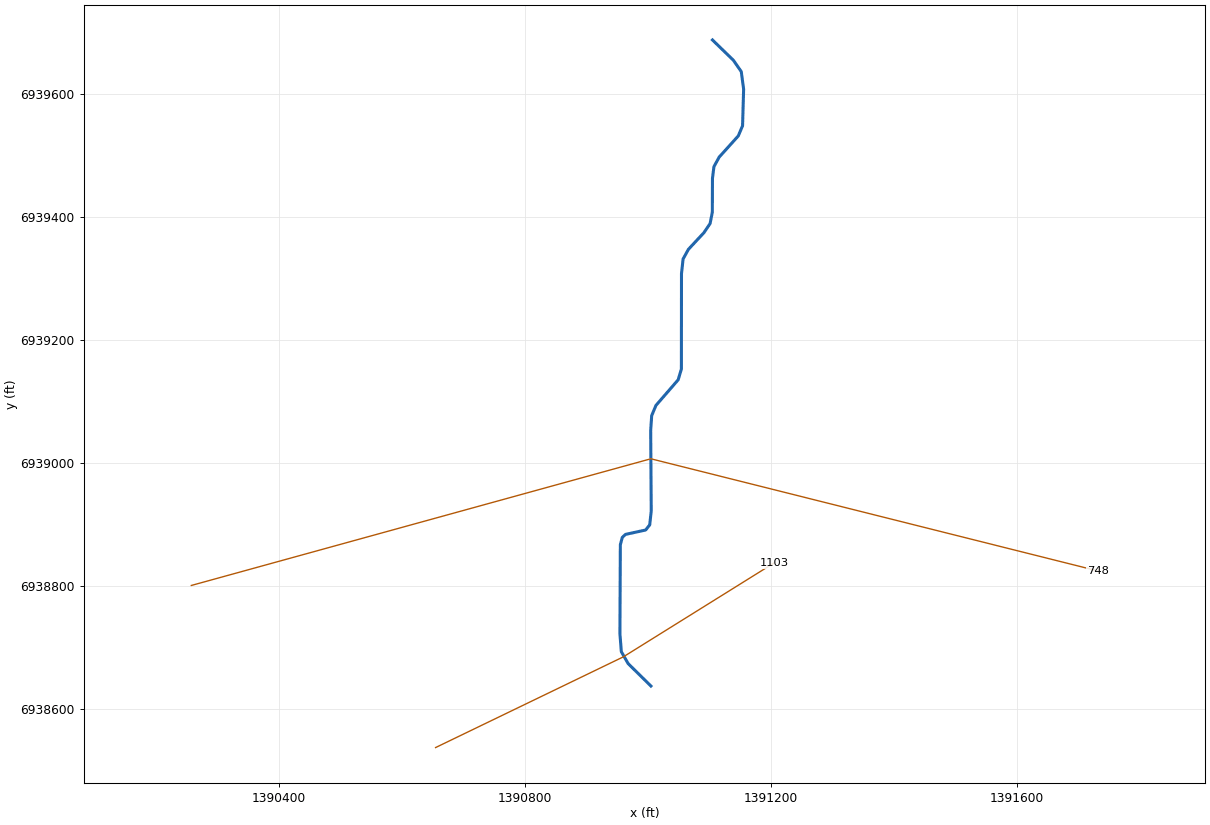
--- Sandy Creek Trib1.prj (project) ---

Proj Title=Sandy Creek Trib1 Base Level Engineering
Current Plan=p01
Default Exp/Contr=0.3,0.1
English Units
Geom File=g01
Flow File=f01
Plan File=p01
BEGIN DESCRIPTION:
Sandy Creek Trib1
END DESCRIPTION:

--- Sandy Creek Trib1.p01 (plan) ---

Plan Title=Multiple Run
Short Identifier=Multiple
Geom File=g01
Flow File=f01
Subcritical Flow
K Sum by GR= 0
Std Step Tol= 0.01
Critical Tol= 0.01
Num of Std Step Trials= 20
Max Error Tol= 0.3
Flow Tol Ratio= 0.001
Split Flow NTrial= 30
Split Flow Tol= 0.02
Split Flow Ratio= 0.02
Log Output Level= 0
Friction Slope Method= 1
Unsteady Friction Slope Method= 2
Unsteady Bridges Friction Slope Method= 1
Parabolic Critical Depth
Global Vel Dist=  1 , 1 , 1
Global Log Level= 0
CheckData=True
Encroach Param= -1, 0, 0, 0
BEGIN DESCRIPTION:
Multiple Run
END DESCRIPTION:

--- Sandy Creek Trib1.f01 (steady flow) ---

Flow Title=Multiple
Number of Profiles=7
Profile Names=10-year,25-year,50-year,1pct_min,100-year,1pct_plu,500-year
River Rch & RM= Sandy Creek Trib,Reach-1,1103
     251     355     441     273     545    1087     842
Boundary for River Rch & Prof#=Sandy Creek Trib,Reach-1,1
Up Type=0
Dn Type=3
Dn Slope=0.005
Boundary for River Rch & Prof#=Sandy Creek Trib,Reach-1,2
Up Type=0
Dn Type=3
Dn Slope=0.005
Boundary for River Rch & Prof#=Sandy Creek Trib,Reach-1,3
Up Type=0
Dn Type=3
Dn Slope=0.005
Boundary for River Rch & Prof#=Sandy Creek Trib,Reach-1,4
Up Type=0
Dn Type=3
Dn Slope=0.005
Boundary for River Rch & Prof#=Sandy Creek Trib,Reach-1,5
Up Type=0
Dn Type=3
Dn Slope=0.005
Boundary for River Rch & Prof#=Sandy Creek Trib,Reach-1,6
Up Type=0
Dn Type=3
Dn Slope=0.005
Boundary for River Rch & Prof#=Sandy Creek Trib,Reach-1,7
Up Type=0
Dn Type=3
Dn Slope=0.005

--- Sandy Creek Trib1.g01 (geometry) ---

Geom Title=Existing Conditions

River Reach=Sandy Creek Trib,Reach-1
Reach XY= 30
      1391005.00      6938638.00      1390967.92      6938674.50
      1390956.89      6938693.79      1390954.58      6938722.84
      1390955.29      6938867.70      1390958.46      6938879.54
      1390963.58      6938884.42      1390996.41      6938891.58
      1391003.03      6938899.97      1391005.49      6938922.51
      1391004.58      6939053.17      1391006.22      6939077.49
      1391013.14      6939094.06      1391049.25      6939135.67
      1391054.48      6939153.22      1391054.65      6939308.15
      1391057.26      6939332.06      1391065.85      6939347.65
      1391091.17      6939374.87      1391101.14      6939389.60
      1391104.76      6939408.10      1391105.00      6939463.00
      1391107.36      6939482.03      1391115.90      6939497.63
      1391146.91      6939531.96      1391153.91      6939548.54
      1391155.64      6939608.03      1391151.81      6939636.60
      1391138.96      6939655.05      1391105.00      6939688.00

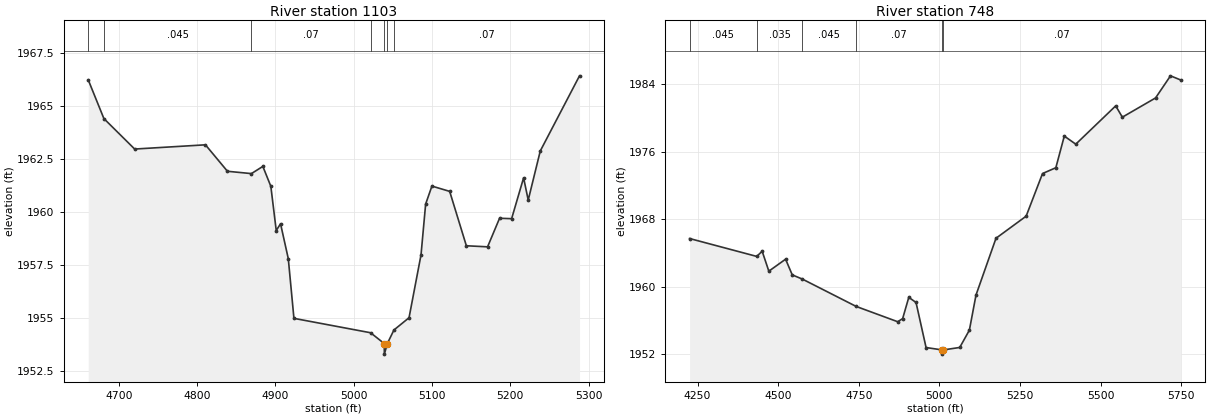
Type RM Length L Ch R = 1,1103,355,355,355
BEGIN DESCRIPTION:
Sandy Creek Trib1 2.0
END DESCRIPTION:
XS GIS Cut Line= 3
      1390654.98      6938537.99      1390960.14      6938685.42
      1391204.99      6938837.99
#Sta/Elev= 30
  4661.1 1966.24  4681.1 1964.41  4720.4 1962.97  4810.8 1963.17  4838.9 1961.92
  4869.5 1961.81  4884.1 1962.15  4894.3 1961.21  4901.2 1959.12  4906.7 1959.44
  4916.6 1957.79  4923.8 1954.97  5021.7 1954.29  5039.1 1953.78  5039.3 1953.28
  5043.1 1953.78  5051.5 1954.42  5070.8 1955.00  5086.1 1957.97  5092.0 1960.37
  5100.0 1961.22  5122.7 1960.97  5144.0 1958.40  5171.1 1958.35  5186.4 1959.70
  5201.8 1959.68  5217.1 1961.61  5223.0 1960.56  5238.4 1962.88  5288.5 1966.43
#Mann=7,-1,0
  4661.1   0.035       0  4681.1   0.045       0  4869.5    0.07       0
  5021.7    0.16       0  5039.1    0.07       0  5043.1    0.16       0
  5051.5    0.07       0
Bank Sta=5039.1,5043.1
Exp/Cntr=0.3,0.1

Type RM Length L Ch R = 1,748,0,0,0
BEGIN DESCRIPTION:
Mapping XS 27ca0ea9
END DESCRIPTION:
XS GIS Cut Line= 3
      1390258.04      6938801.45      1391004.88      6939007.34
      1391730.97      6938825.16
#Sta/Elev= 30
  4225.3 1965.69  4433.5 1963.57  4450.4 1964.18  4471.1 1961.82  4523.0 1963.24
  4543.7 1961.38  4575.2 1960.88  4742.0 1957.64  4870.6 1955.83  4886.0 1956.20
  4905.0 1958.72  4927.5 1958.11  4958.6 1952.77  5008.4 1952.49  5008.7 1951.99
  5012.4 1952.49  5063.0 1952.78  5092.9 1954.83  5113.5 1959.00  5175.4 1965.72
  5268.9 1968.34  5319.7 1973.39  5361.0 1974.08  5387.2 1977.83  5422.8 1976.87
  5546.6 1981.41  5567.2 1980.07  5670.2 1982.35  5716.5 1984.97  5748.6 1984.47
#Mann=6,-1,0
  4225.3   0.045       0  4433.5   0.035       0  4575.2   0.045       0
  4742.0    0.07       0  5008.4    0.07       0  5012.4    0.07       0
Bank Sta=5008.4,5012.4
Exp/Cntr=0.3,0.1

Chan Stop Cuts=-1