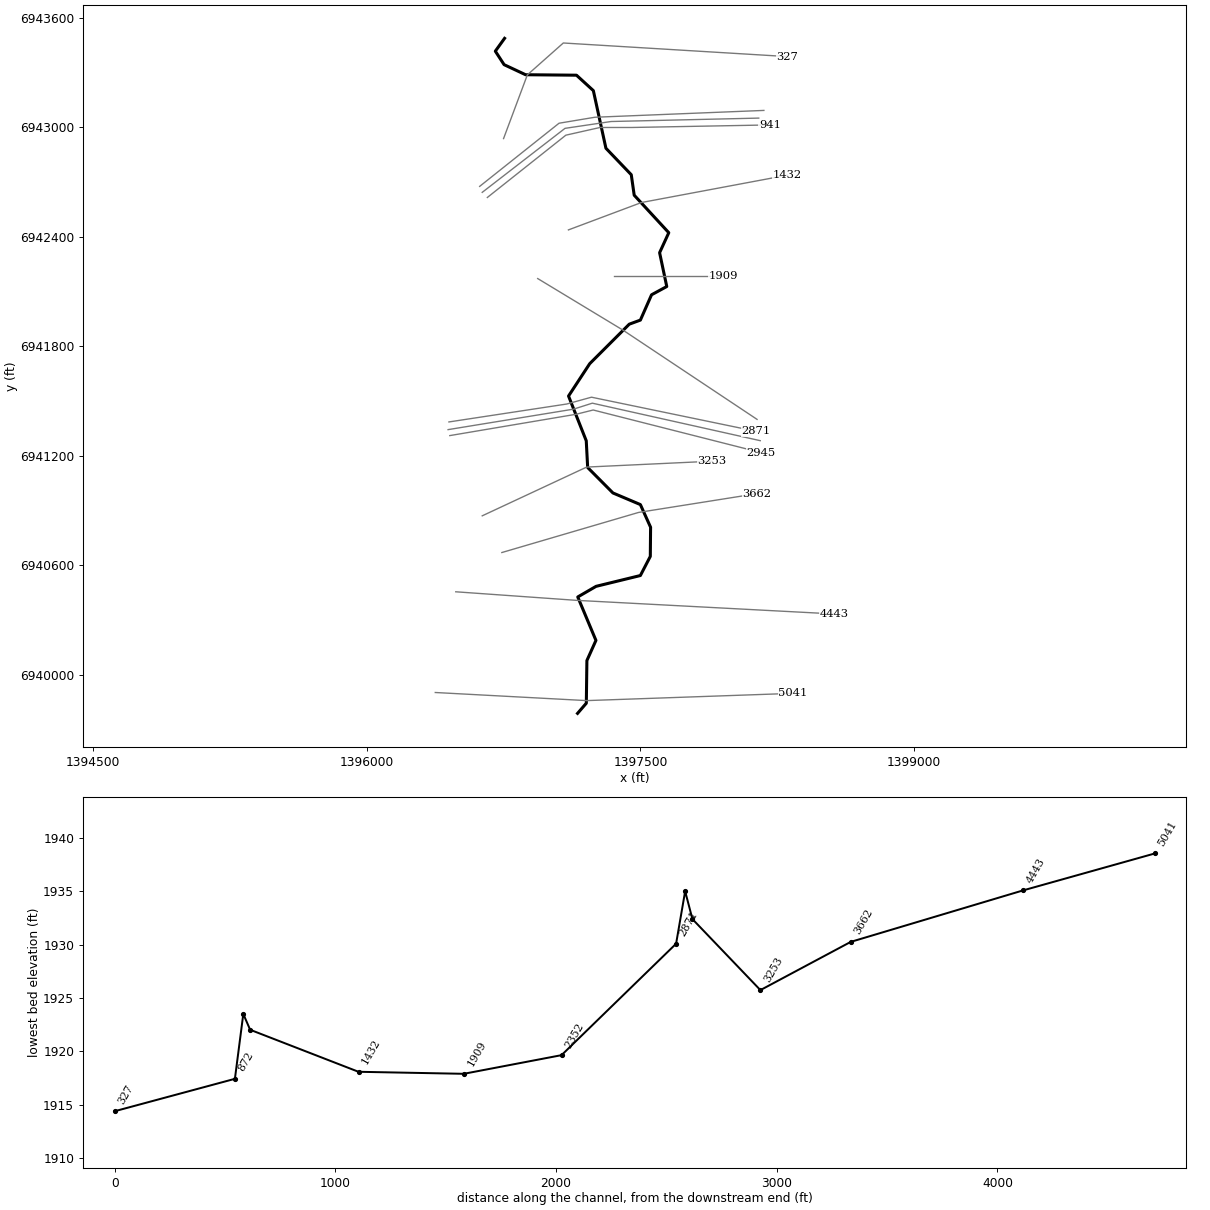
--- Sandy Creek Trib2.prj (project) ---

Proj Title=Sandy Creek Trib2 Base Level Engineering
Current Plan=p01
Default Exp/Contr=0.3,0.1
English Units
Geom File=g01
Flow File=f01
Plan File=p01
Y Axis Title=Elevation
X Axis Title(PF)=Main Channel Distance
X Axis Title(XS)=Station
BEGIN DESCRIPTION:
Sandy Creek Trib2
END DESCRIPTION:
DSS Export Rating Curves= 0
DSS Export Rating Curve Sorted= 0
DSS Export Volume Flow Curves= 0
DXF OffsetX= 0
DXF OffsetY= 0
DXF ScaleX= 1
DXF ScaleY= 10

--- Sandy Creek Trib2.p01 (plan) ---

Plan Title=Multiple Run
Short Identifier=Multiple
Geom File=g01
Flow File=f01
Subcritical Flow
K Sum by GR= 0
Std Step Tol= 0.01
Critical Tol= 0.01
Num of Std Step Trials= 20
Max Error Tol= 0.3
Flow Tol Ratio= 0.001
Split Flow NTrial= 30
Split Flow Tol= 0.02
Split Flow Ratio= 0.02
Log Output Level= 0
Friction Slope Method= 1
Unsteady Friction Slope Method= 2
Unsteady Bridges Friction Slope Method= 1
Parabolic Critical Depth
Global Vel Dist=  1 , 1 , 1
Global Log Level= 0
CheckData=True
Encroach Param= -1, 0, 0, 0
BEGIN DESCRIPTION:
Multiple Run
END DESCRIPTION:

--- Sandy Creek Trib2.f01 (steady flow) ---

Flow Title=Multiple
Number of Profiles=7
Profile Names=10-year,25-year,50-year,1pct_min,100-year,1pct_plu,500-year
River Rch & RM= Sandy Creek Trib,Reach-1,5041
     251     355     442     274     547    1092     849
River Rch & RM= Sandy Creek Trib,Reach-1,3662
     278     396     496     309     616    1229     962
River Rch & RM= Sandy Creek Trib,Reach-1,2871
     396     574     727     458     913    1822    1460
River Rch & RM= Sandy Creek Trib,Reach-1,910
     391     566     715     449     897    1789    1429
Boundary for River Rch & Prof#=Sandy Creek Trib,Reach-1,1
Up Type=0
Dn Type=3
Dn Slope=0.005
Boundary for River Rch & Prof#=Sandy Creek Trib,Reach-1,2
Up Type=0
Dn Type=3
Dn Slope=0.005
Boundary for River Rch & Prof#=Sandy Creek Trib,Reach-1,3
Up Type=0
Dn Type=3
Dn Slope=0.005
Boundary for River Rch & Prof#=Sandy Creek Trib,Reach-1,4
Up Type=0
Dn Type=3
Dn Slope=0.005
Boundary for River Rch & Prof#=Sandy Creek Trib,Reach-1,5
Up Type=0
Dn Type=3
Dn Slope=0.005
Boundary for River Rch & Prof#=Sandy Creek Trib,Reach-1,6
Up Type=0
Dn Type=3
Dn Slope=0.005
Boundary for River Rch & Prof#=Sandy Creek Trib,Reach-1,7
Up Type=0
Dn Type=3
Dn Slope=0.005

--- Sandy Creek Trib2.g01 (geometry) ---

Geom Title=Existing Conditions
Program Version=4.10

River Reach=Sandy Creek Trib,Reach-1
Reach XY= 30
        1397155.        6939788.      1397203.11      6939843.78
      1397206.22       6940077.5      1397255.82        6940188.
      1397156.16      6940426.01      1397256.52      6940484.26
      1397499.42      6940543.58      1397553.81      6940648.48
      1397555.37      6940808.16      1397499.42      6940932.42
      1397348.95      6940996.14      1397210.47      6941135.55
      1397202.73      6941282.06       1397105.6      6941527.38
      1397221.65      6941704.67      1397438.52      6941921.27
      1397499.41      6941943.61      1397560.66      6942082.39
      1397643.98      6942127.64      1397604.78      6942313.08
      1397655.05      6942422.66      1397465.52      6942628.21
      1397449.48      6942740.43      1397310.52      6942885.57
      1397241.64      6943201.35      1397149.16      6943285.95
      1396870.21      6943288.51      1396752.38      6943343.72
      1396704.32      6943417.67        1396755.        6943488.

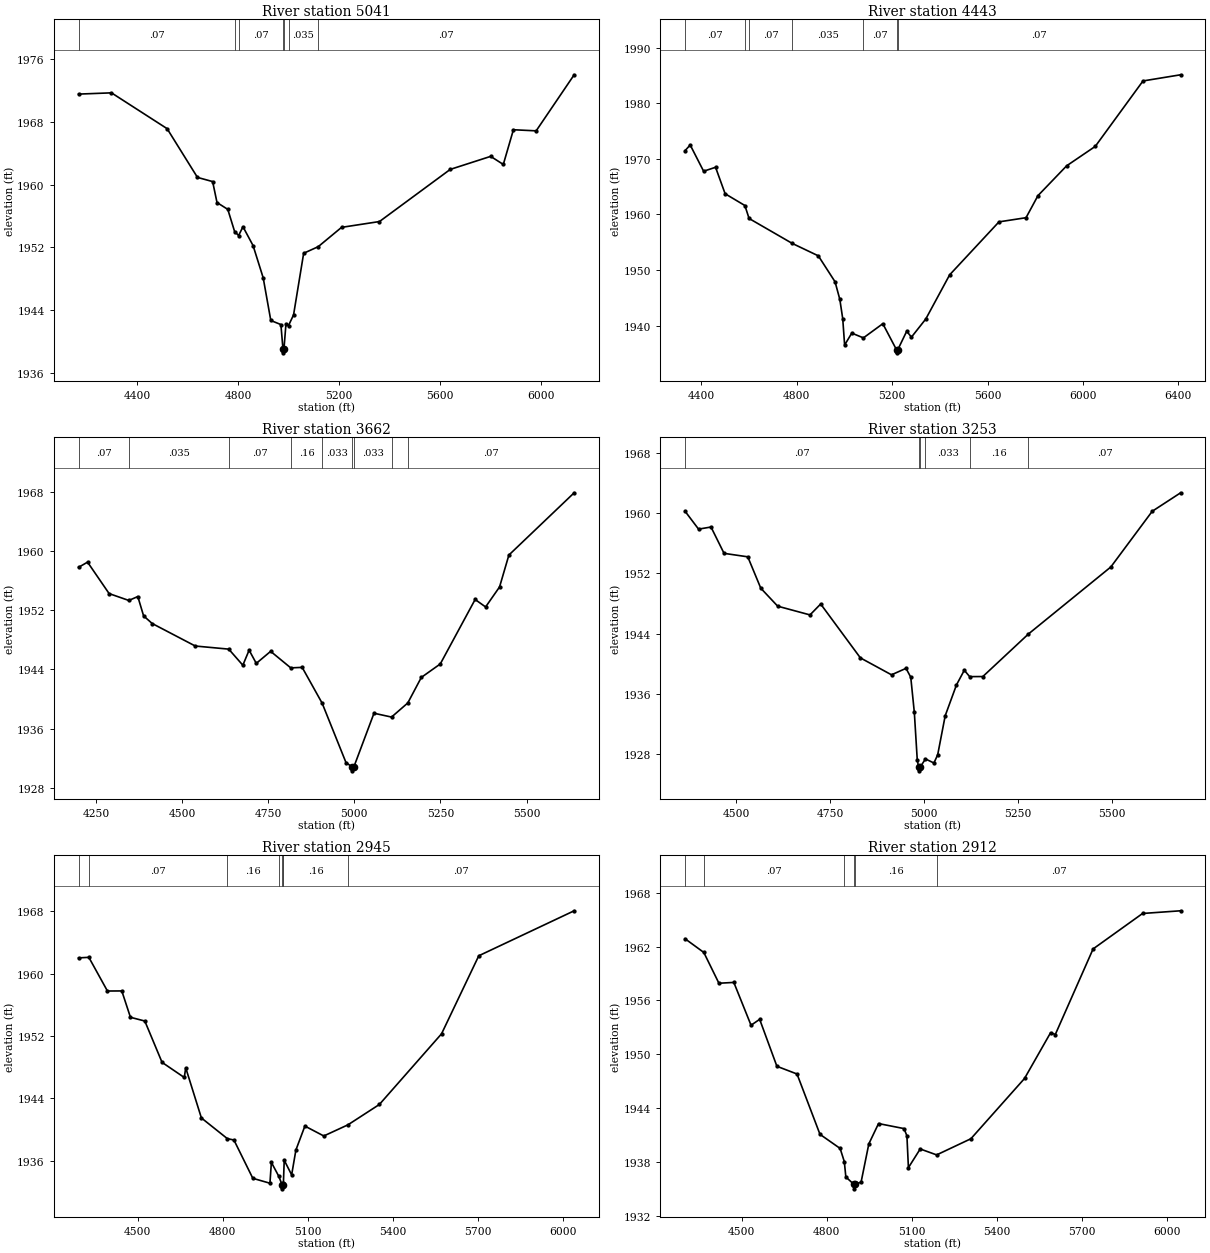
Type RM Length L Ch R = 1 ,5041    ,598,598,598
BEGIN DESCRIPTION:
Mapping XS 16e90582
END DESCRIPTION:
XS GIS Cut Line= 3
      1396375.21       6939902.4      1397205.02      6939857.99
      1398335.42      6939897.73
#Sta/Elev= 30
    4169 1971.52    4299 1971.68  4519.3 1967.12  4639.5 1960.91  4699.6 1960.38
  4716.9 1957.71  4759.6 1956.84  4786.6 1954.02  4802.5 1953.51  4819.7 1954.63
  4859.8 1952.22  4899.8 1948.12  4929.9 1942.69  4969.9 1942.17    4978 1939.07
  4978.2 1938.57    4982 1939.07    4990 1942.28  5000.1 1942.05    5020  1943.4
    5060 1951.25  5117.7 1952.09  5210.1 1954.55  5360.2 1955.29  5640.4 1961.93
  5800.5 1963.59  5850.5 1962.56  5890.5 1966.98  5980.6 1966.84  6131.1 1973.98
#Mann= 7 ,-1 , 0
    4169     .07       0  4786.6    .035       0  4802.5     .07       0
    4978    .035       0    4982     .07       0  5000.1    .035       0
  5117.7     .07       0
Bank Sta=4978,4982
XS Rating Curve= 0 ,0
Exp/Cntr=0.3,0.1

Type RM Length L Ch R = 1 ,4443    ,781,781,781
BEGIN DESCRIPTION:
Mapping XS c6afc6d2
END DESCRIPTION:
XS GIS Cut Line= 3
      1396487.48      6940454.43      1397147.12      6940407.64
      1398562.65       6940332.9
#Sta/Elev= 30
  4331.2 1971.48  4352.6 1972.49  4408.9 1967.77    4459 1968.48  4499.1 1963.72
    4582  1961.6  4599.6 1959.27  4780.9 1954.78  4890.1 1952.55  4960.3 1947.88
  4980.3 1944.71  4992.5 1941.24  5000.4  1936.5  5030.4 1938.65  5079.2 1937.79
  5160.6 1940.34  5218.7  1935.6  5218.9  1935.1  5222.7  1935.6  5260.8 1938.98
  5280.8 1937.93  5340.9 1941.19    5441 1949.13  5647.9 1958.66  5761.4 1959.41
  5811.5 1963.38  5931.7 1968.74  6051.9 1972.24  6252.1 1984.01    6410 1985.12
#Mann= 7 ,-1 , 0
  4331.2     .07       0    4582    .035       0  4599.6     .07       0
  4780.9    .035       0  5079.2     .07       0  5218.7      .1       0
  5222.7     .07       0
Bank Sta=5218.7,5222.7
XS Rating Curve= 0 ,0
Exp/Cntr=0.3,0.1

Type RM Length L Ch R = 1 ,3662    ,409,409,409
BEGIN DESCRIPTION:
Sandy Creek Trib2 8.0
END DESCRIPTION:
XS GIS Cut Line= 3
       1396740.1      6940669.61      1397489.79      6940889.43
      1398138.92      6940992.42
#Sta/Elev= 30
  4199.7 1957.83  4225.6 1958.53  4288.2 1954.27  4345.4 1953.34  4371.5 1953.87
  4388.3 1951.25  4413.2 1950.22  4538.3 1947.17  4635.4 1946.75  4676.4 1944.57
  4694.6 1946.61  4715.4 1944.82  4757.1 1946.45  4815.5 1944.21  4848.6 1944.28
  4906.6 1939.43  4975.8 1931.39  4994.4 1930.77  4994.6 1930.27  4998.4 1930.77
  5057.1 1938.07    5108 1937.55  5155.2 1939.46  5194.5 1942.92  5249.5 1944.74
  5350.7 1953.47  5381.1 1952.46  5421.6 1955.17  5448.7 1959.49  5638.2 1967.92
#Mann= 9 ,-1 , 0
  4199.7     .07       0  4345.4    .035       0  4635.4     .07       0
  4815.5     .16       0  4906.6    .033       0  4994.4     .07       0
  4998.4    .033       0    5108     .16       0  5155.2     .07       0
Bank Sta=4994.4,4998.4
XS Rating Curve= 0 ,0
Exp/Cntr=0.3,0.1

Type RM Length L Ch R = 1 ,3253    ,308,308,308
BEGIN DESCRIPTION:
Sandy Creek Trib2 7.0
END DESCRIPTION:
XS GIS Cut Line= 3
      1396632.56       6940870.8        1397205.        6941138.
      1397890.52      6941170.16
#Sta/Elev= 30
  4364.1 1960.24  4399.9 1957.87    4433 1958.15  4467.7 1954.65  4530.8 1954.19
  4565.4 1950.02  4610.4 1947.63  4696.3 1946.47  4724.7 1947.92  4830.3 1940.76
  4913.1 1938.51  4951.7 1939.37  4964.3 1938.19  4973.8 1933.51  4981.6 1927.19
  4985.2 1926.25  4985.4 1925.75  4989.2 1926.25  5003.5 1927.33  5025.9 1926.79
  5035.9 1927.88  5055.9 1933.07  5085.9 1937.17  5106.7 1939.12  5120.9 1938.27
    5156 1938.28  5277.4 1943.94  5496.4 1952.84  5606.5 1960.24  5682.1  1962.7
#Mann= 6 ,-1 , 0
  4364.1     .07       0  4985.2     .07       0  4989.2     .07       0
  5003.5    .033       0  5120.9     .16       0  5277.4     .07       0
Bank Sta=4985.2,4989.2
XS Rating Curve= 0 ,0
Exp/Cntr=0.3,0.1

Type RM Length L Ch R = 1 ,2945    ,33,33,33
BEGIN DESCRIPTION:
Mapping XS dd080311
END DESCRIPTION:
XS GIS Cut Line= 4
      1396454.79      6941310.54      1397147.12      6941427.48
      1397240.68      6941450.87      1398161.12      6941217.26
#Sta/Elev= 30
  4291.5 1962.03  4327.5  1962.1  4393.1 1957.78  4443.8 1957.79  4474.3 1954.41
    4525 1953.93  4585.8 1948.63  4664.2 1946.69  4669.3 1947.93  4724.6  1941.5
  4816.1 1938.85  4839.4 1938.67    4906 1933.76  4966.4 1933.13  4971.5  1935.8
  4997.6 1934.02  5009.6 1932.91  5009.8 1932.41  5013.7 1932.91  5013.9 1933.11
  5016.8 1936.08    5043  1934.2    5058 1937.39  5089.7 1940.46  5156.4 1939.19
  5241.7 1940.62  5352.5 1943.23  5571.8 1952.29  5703.2  1962.3  6039.7 1968.07
#Mann= 8 ,-1 , 0
  4291.5    .045       0  4327.5     .07       0  4816.1     .16       0
  4997.6    .033       0  5009.6    .033       0  5013.7    .033       0
  5013.9     .16       0  5241.7     .07       0
Bank Sta=5009.6,5013.7
XS Rating Curve= 0 ,0
Exp/Cntr=0.3,0.1

Type RM Length L Ch R = 1 ,2912    ,41,41,41
BEGIN DESCRIPTION:
Mapping XS df86f0e4
END DESCRIPTION:
XS GIS Cut Line= 4
      1396445.39      6941343.27      1397133.09      6941455.55
      1397236.01       6941488.3      1398156.42      6941282.72
#Sta/Elev= 30
    4300 1962.87    4366 1961.35  4419.3 1957.92  4471.9 1958.01  4532.6 1953.24
    4563  1953.9  4623.8 1948.67  4694.8 1947.81  4775.8 1941.09  4846.8 1939.52
  4861.6 1938.05    4867 1936.34  4895.4 1935.52  4895.6 1935.02  4899.5 1935.52
  4920.8 1935.77  4948.1 1940.03  4982.3 1942.29  5072.3 1941.73  5082.4 1940.92
  5087.7 1937.38  5129.3 1939.46  5187.3  1938.8  5308.1  1940.6  5497.2 1947.31
  5589.2 1952.41  5605.8 1952.21  5739.1 1961.74  5913.7 1965.69  6047.9 1965.99
#Mann= 6 ,-1 , 0
    4300    .045       0    4366     .07       0  4861.6     .16       0
  4895.4     .07       0  4899.5     .16       0  5187.3     .07       0
Bank Sta=4895.4,4899.5
XS Rating Curve= 0 ,0
Exp/Cntr=0.3,0.1

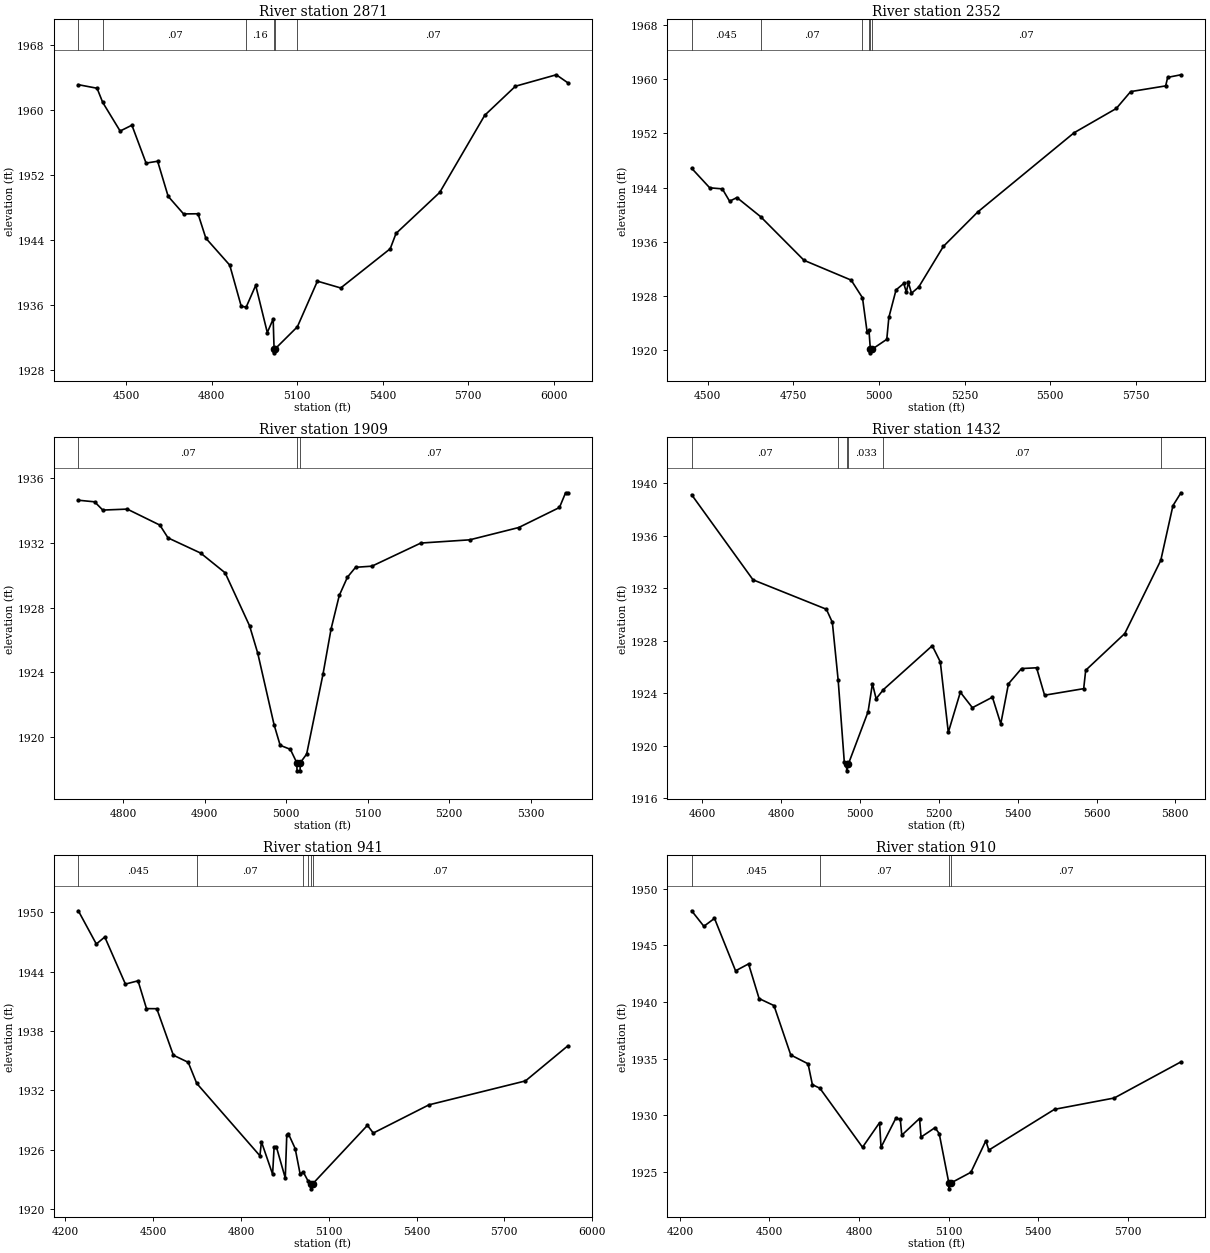
Type RM Length L Ch R = 1 ,2871    ,519,519,519
BEGIN DESCRIPTION:
Mapping XS 2584876e
END DESCRIPTION:
XS GIS Cut Line= 4
      1396450.07      6941385.38      1397095.66      6941483.62
      1397231.33      6941521.05      1398134.18      6941333.93
#Sta/Elev= 30
  4332.6 1963.13  4398.3 1962.69  4418.1 1960.95  4479.2 1957.42  4520.5 1958.14
  4570.2 1953.47  4610.7  1953.7  4647.6 1949.38  4701.7 1947.21  4752.3 1947.23
  4779.8 1944.22  4863.6  1940.9    4904 1935.82  4921.3 1935.74  4954.6 1938.41
  4995.3  1932.6  5015.9 1934.27    5019  1930.6  5019.3  1930.1  5023.1  1930.6
  5100.8 1933.31    5171 1938.93  5252.7 1938.09  5426.3 1942.92  5446.7 1944.81
  5599.9 1949.86  5757.7 1959.36  5865.4 1962.94  6008.6 1964.35  6048.4 1963.38
#Mann= 6 ,-1 , 0
  4332.6    .045       0  4418.1     .07       0  4921.3     .16       0
    5019     .07       0  5023.1     .16       0  5100.8     .07       0
Bank Sta=5019,5023.1
XS Rating Curve= 0 ,0
Exp/Cntr=0.3,0.1

Type RM Length L Ch R = 1 ,2352    ,443,443,443
BEGIN DESCRIPTION:
Sandy Creek Trib2 5.0
END DESCRIPTION:
XS GIS Cut Line= 3
      1396936.61      6942171.31        1397405.        6941888.
      1398138.93      6941399.39
#Sta/Elev= 30
  4452.8 1946.86  4505.5 1943.98  4542.4 1943.82  4563.7    1942    4585 1942.54
  4654.3 1939.72    4781 1933.29  4918.7 1930.37  4951.8 1927.76  4965.1 1922.78
  4970.7 1922.96  4974.8 1920.15  4975.1 1919.65    4979 1920.15  5022.7 1921.64
  5028.8 1924.87  5049.8 1928.93  5072.3 1929.88  5079.8 1928.61  5085.9 1930.02
  5094.9 1928.44  5115.9 1929.34    5188 1935.34  5288.5 1940.42  5569.7 1952.09
    5693 1955.67    5735 1958.16  5837.2    1959  5843.2 1960.26  5881.9 1960.64
#Mann= 6 ,-1 , 0
  4452.8    .045       0  4654.3     .07       0  4951.8     .16       0
  4970.7     .07       0  4974.8     .07       0    4979     .07       0
Bank Sta=4974.8,4979
XS Rating Curve= 0 ,0
Exp/Cntr=0.3,0.1

Type RM Length L Ch R = 1 ,1909    ,477,477,477
BEGIN DESCRIPTION:
Sandy Creek Trib2 4.0
END DESCRIPTION:
XS GIS Cut Line= 3
      1397354.97        6942188.        1397605.        6942188.
      1397954.97        6942188.
#Sta/Elev= 30
  4745.2 1934.64  4765.2 1934.54  4775.2 1934.03  4805.2 1934.09  4845.2  1933.1
  4855.2 1932.31  4895.2 1931.37  4925.2 1930.15  4955.2 1926.87  4965.2 1925.18
  4985.2 1920.76  4992.7 1919.48  5005.2 1919.23  5013.1  1918.4  5013.4  1917.9
  5017.1  1917.9  5017.4  1918.4  5025.2 1918.94  5045.2 1923.87  5055.2 1926.69
  5065.2 1928.75  5075.2 1929.88  5085.2 1930.49  5105.2 1930.56  5165.2 1931.99
  5225.2 1932.19  5285.2 1932.95  5335.2 1934.19  5342.7  1935.1  5345.2  1935.1
#Mann= 3 ,-1 , 0
  4745.2     .07       0  5013.1     .07       0  5017.4     .07       0
Bank Sta=5013.1,5017.4
XS Rating Curve= 0 ,0
Exp/Cntr=0.3,0.1

Type RM Length L Ch R = 1 ,1432    ,491,491,491
BEGIN DESCRIPTION:
Sandy Creek Trib2 3.0
END DESCRIPTION:
XS GIS Cut Line= 3
      1397105.01      6942438.01        1397505.        6942588.
      1398304.97        6942738.
#Sta/Elev= 30
  4573.1 1939.12  4728.8 1932.64  4914.8  1930.4    4930  1929.4  4944.8 1924.98
  4960.2  1918.8  4966.1 1918.59  4966.4 1918.09  4970.4 1918.59  5020.6 1922.59
  5031.7 1924.73    5041 1923.58  5059.6 1924.28  5183.4 1927.62  5203.8 1926.39
  5224.1 1921.02  5254.6 1924.08  5285.2  1922.9    5336  1923.7  5357.2 1921.67
  5376.7 1924.72  5409.8 1925.88    5448 1925.94  5468.3 1923.85  5567.5 1924.35
  5572.6 1925.75  5671.8 1928.55    5763 1934.12  5793.9 1938.29  5814.2 1939.27
#Mann= 6 ,-1 , 0
  4573.1     .07       0  4944.8    .033       0  4966.1    .033       0
  4970.4    .033       0  5059.6     .07       0    5763    .035       0
Bank Sta=4966.1,4970.4
XS Rating Curve= 0 ,0
Exp/Cntr=0.3,0.1

Type RM Length L Ch R = 1 ,941     ,31,31,31
BEGIN DESCRIPTION:
Mapping XS d7466591
END DESCRIPTION:
XS GIS Cut Line= 5
      1396660.58      6942615.72      1397090.98      6942957.24
      1397278.11      6942999.34       1397451.2      6942999.34
      1398209.04      6943013.38
#Sta/Elev= 30
  4244.2 1950.14  4305.7 1946.78  4334.6 1947.49  4405.1 1942.73  4448.3 1943.06
  4477.2 1940.25  4512.4 1940.24    4569 1935.54  4619.8 1934.82  4648.9 1932.69
  4864.9 1925.37    4870 1926.79  4908.2 1923.51  4913.3 1926.21  4920.8  1926.3
  4951.5 1923.12  4956.6 1927.45  4961.8 1927.62  4985.4  1926.1  5002.3 1923.52
  5012.8 1923.74  5029.1 1922.84  5039.6 1922.53    5040 1922.03  5045.1 1922.53
  5232.3 1928.45  5252.3 1927.67  5442.4 1930.52  5772.4 1932.94  5916.5 1936.47
#Mann= 6 ,-1 , 0
  4244.2    .045       0  4648.9     .07       0  5012.8    .033       0
  5029.1     .07       0  5039.6     .07       0  5045.1     .07       0
Bank Sta=5039.6,5045.1
XS Rating Curve= 0 ,0
Exp/Cntr=0.3,0.1

Type RM Length L Ch R = 1 ,910     ,38,38,38
BEGIN DESCRIPTION:
Mapping XS f31ea680
END DESCRIPTION:
XS GIS Cut Line= 4
      1396632.54      6942643.82       1397086.3      6942994.67
      1397338.93      6943032.09      1398148.25       6943050.8
#Sta/Elev= 30
  4239.4 1948.06  4280.4 1946.69  4315.9 1947.39  4386.5 1942.76    4430 1943.37
  4465.3 1940.31  4515.1 1939.69  4571.3 1935.33  4629.2 1934.55  4643.7 1932.71
  4668.9 1932.39  4811.6 1927.18  4868.6 1929.35  4873.6 1927.18  4922.9 1929.73
  4938.1 1929.65  4943.1 1928.25  5002.5 1929.72  5007.6 1928.08  5054.3 1928.91
  5068.4 1928.39  5100.8 1924.01  5101.2 1923.51  5106.3 1924.01  5174.5 1924.97
  5224.5 1927.75  5234.5 1926.93  5454.5 1930.53  5654.6 1931.53  5877.9 1934.72
#Mann= 4 ,-1 , 0
  4239.4    .045       0  4668.9     .07       0  5100.8     .07       0
  5106.3     .07       0
Bank Sta=5100.8,5106.3
XS Rating Curve= 0 ,0
Exp/Cntr=0.3,0.1

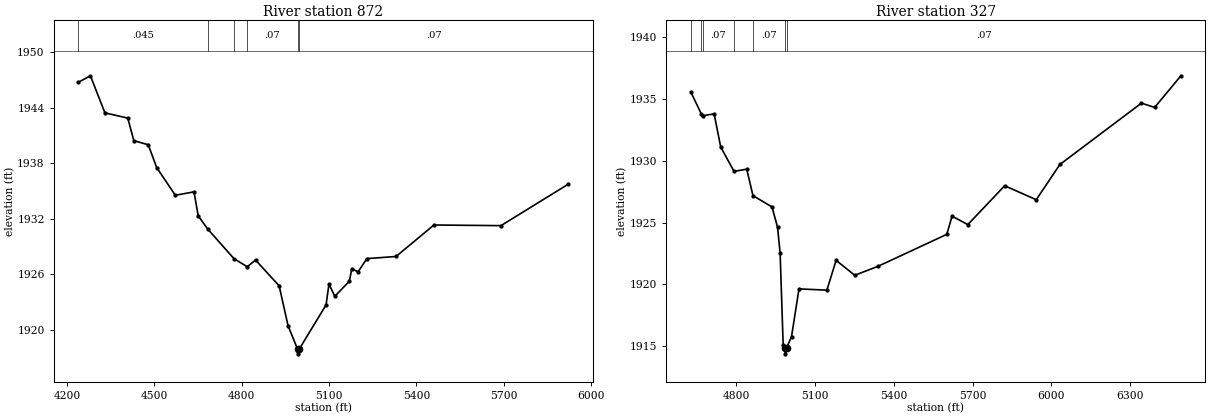
Type RM Length L Ch R = 1 ,872     ,545,545,545
BEGIN DESCRIPTION:
Mapping XS a7b87e0a
END DESCRIPTION:
XS GIS Cut Line= 4
      1396618.46      6942676.53      1397053.56      6943022.74
      1397250.04      6943055.48      1398176.36      6943092.91
#Sta/Elev= 30
  4239.5 1946.75  4280.9 1947.45  4330.6 1943.45  4409.1 1942.88  4429.9 1940.45
  4479.5    1940  4508.4 1937.54  4572.4 1934.55  4636.5 1934.92  4650.9 1932.33
  4683.6  1930.9  4773.6 1927.71  4819.4 1926.83  4847.7 1927.56  4928.8 1924.77
  4959.2 1920.48    4992 1917.93  4992.4 1917.43  4997.5 1917.93  5089.8 1922.71
  5099.8 1924.96  5119.8 1923.64  5169.8 1925.27  5177.9 1926.59  5199.9 1926.29
  5229.9 1927.71    5330 1927.94  5460.1 1931.34  5690.3 1931.27  5921.8 1935.76
#Mann= 6 ,-1 , 0
  4239.5    .045       0  4683.6     .07       0  4773.6    .045       0
  4819.4     .07       0    4992     .07       0  4997.5     .07       0
Bank Sta=4992,4997.5
XS Rating Curve= 0 ,0
Exp/Cntr=0.3,0.1

Type RM Length L Ch R = 1 ,327     ,0,0,0
BEGIN DESCRIPTION:
Sandy Creek Trib2 1.0
END DESCRIPTION:
XS GIS Cut Line= 4
      1396749.48      6942938.55      1396879.91      6943287.79
      1397076.95      6943462.48      1398304.96        6943388.
#Sta/Elev= 30
  4627.2 1935.56  4667.8 1933.75  4672.1 1933.64  4715.9 1933.79  4740.9 1931.12
  4791.6 1929.14  4840.1 1929.32  4863.8 1927.18  4936.2 1926.27  4957.5 1924.62
  4967.3 1922.51  4978.9 1915.08  4986.8 1914.89  4987.2 1914.39  4992.4 1914.89
  5010.7 1915.79  5039.1 1919.64  5145.3 1919.54  5180.5 1921.95  5251.5 1920.74
  5341.5 1921.48    5602 1924.05    5622 1925.52  5682.1 1924.84  5822.4 1927.98
  5942.6 1926.85  6032.8  1929.7  6343.4 1934.66  6393.5 1934.31  6493.6 1936.87
#Mann= 7 ,-1 , 0
  4627.2    .035       0  4667.8    .045       0  4672.1     .07       0
  4791.6    .035       0  4863.8     .07       0  4986.8     .07       0
  4992.4     .07       0
Bank Sta=4986.8,4992.4
XS Rating Curve= 0 ,0
Exp/Cntr=0.3,0.1

Chan Stop Cuts=-1
Use User Specified Reach Order=0
Composite Channel Slope=5