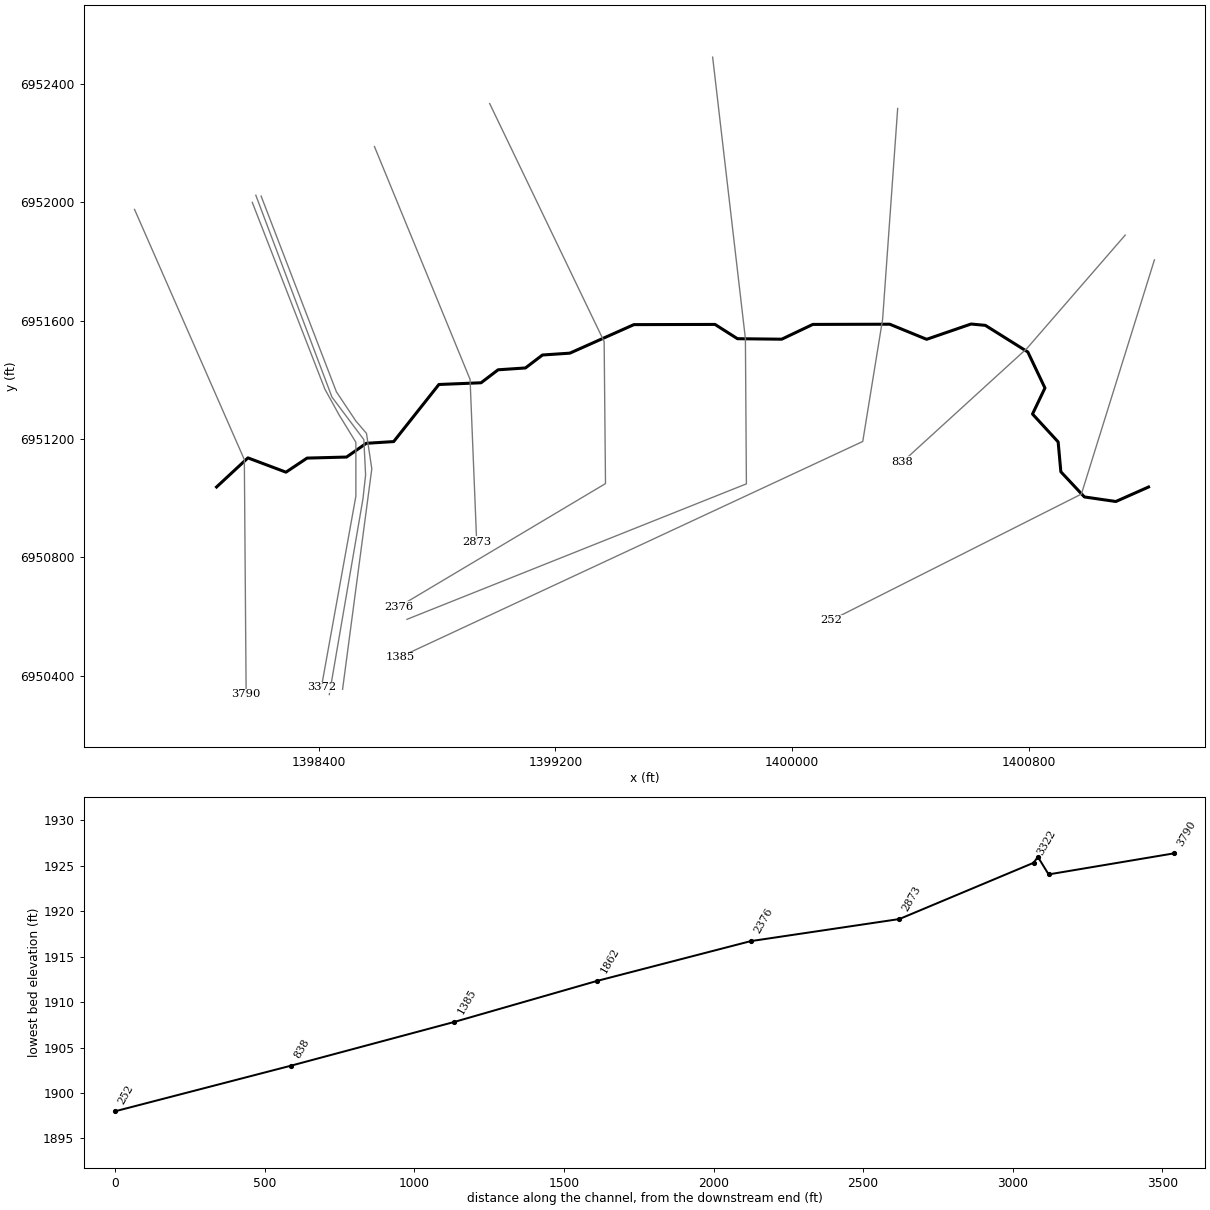
--- Sandy Creek Trib3.prj (project) ---

Proj Title=Sandy Creek Trib3 Base Level Engineering
Current Plan=p01
Default Exp/Contr=0.3,0.1
English Units
Geom File=g01
Flow File=f01
Plan File=p01
BEGIN DESCRIPTION:
Sandy Creek Trib3
END DESCRIPTION:

--- Sandy Creek Trib3.p01 (plan) ---

Plan Title=Multiple Run
Short Identifier=Multiple
Geom File=g01
Flow File=f01
Subcritical Flow
K Sum by GR= 0
Std Step Tol= 0.01
Critical Tol= 0.01
Num of Std Step Trials= 20
Max Error Tol= 0.3
Flow Tol Ratio= 0.001
Split Flow NTrial= 30
Split Flow Tol= 0.02
Split Flow Ratio= 0.02
Log Output Level= 0
Friction Slope Method= 1
Unsteady Friction Slope Method= 2
Unsteady Bridges Friction Slope Method= 1
Parabolic Critical Depth
Global Vel Dist=  1 , 1 , 1
Global Log Level= 0
CheckData=True
Encroach Param= -1, 0, 0, 0
BEGIN DESCRIPTION:
Multiple Run
END DESCRIPTION:

--- Sandy Creek Trib3.f01 (steady flow) ---

Flow Title=Multiple
Number of Profiles=7
Profile Names=10-year,25-year,50-year,1pct_min,100-year,1pct_plu,500-year
River Rch & RM= Sandy Creek Trib,Reach-1,3790
     257     361     449     277     553    1103     851
River Rch & RM= Sandy Creek Trib,Reach-1,1385
     316     452     566     352     703    1403    1100
Boundary for River Rch & Prof#=Sandy Creek Trib,Reach-1,1
Up Type=0
Dn Type=3
Dn Slope=0.005
Boundary for River Rch & Prof#=Sandy Creek Trib,Reach-1,2
Up Type=0
Dn Type=3
Dn Slope=0.005
Boundary for River Rch & Prof#=Sandy Creek Trib,Reach-1,3
Up Type=0
Dn Type=3
Dn Slope=0.005
Boundary for River Rch & Prof#=Sandy Creek Trib,Reach-1,4
Up Type=0
Dn Type=3
Dn Slope=0.005
Boundary for River Rch & Prof#=Sandy Creek Trib,Reach-1,5
Up Type=0
Dn Type=3
Dn Slope=0.005
Boundary for River Rch & Prof#=Sandy Creek Trib,Reach-1,6
Up Type=0
Dn Type=3
Dn Slope=0.005
Boundary for River Rch & Prof#=Sandy Creek Trib,Reach-1,7
Up Type=0
Dn Type=3
Dn Slope=0.005

--- Sandy Creek Trib3.g01 (geometry) ---

Geom Title=Existing Conditions

River Reach=Sandy Creek Trib,Reach-1
Reach XY= 30
      1398055.00      6951038.00      1398161.03      6951136.44
      1398289.60      6951088.10      1398360.93      6951135.70
      1398494.49      6951139.23      1398560.98      6951185.64
      1398653.72      6951191.52      1398806.46      6951384.46
      1398949.06      6951390.27      1399006.60      6951434.14
      1399099.03      6951440.35      1399156.60      6951484.15
      1399249.03      6951490.35      1399465.50      6951586.78
      1399739.78      6951587.48      1399815.51      6951539.22
      1399965.18      6951537.54      1400070.22      6951587.48
      1400330.08      6951588.20      1400455.00      6951537.18
      1400605.00      6951588.82      1400653.42      6951584.33
      1400796.98      6951494.34      1400854.86      6951372.59
      1400812.83      6951284.60      1400899.45      6951190.43
      1400908.61      6951089.48      1400988.21      6951004.39
      1401094.48      6950988.99      1401205.00      6951038.00

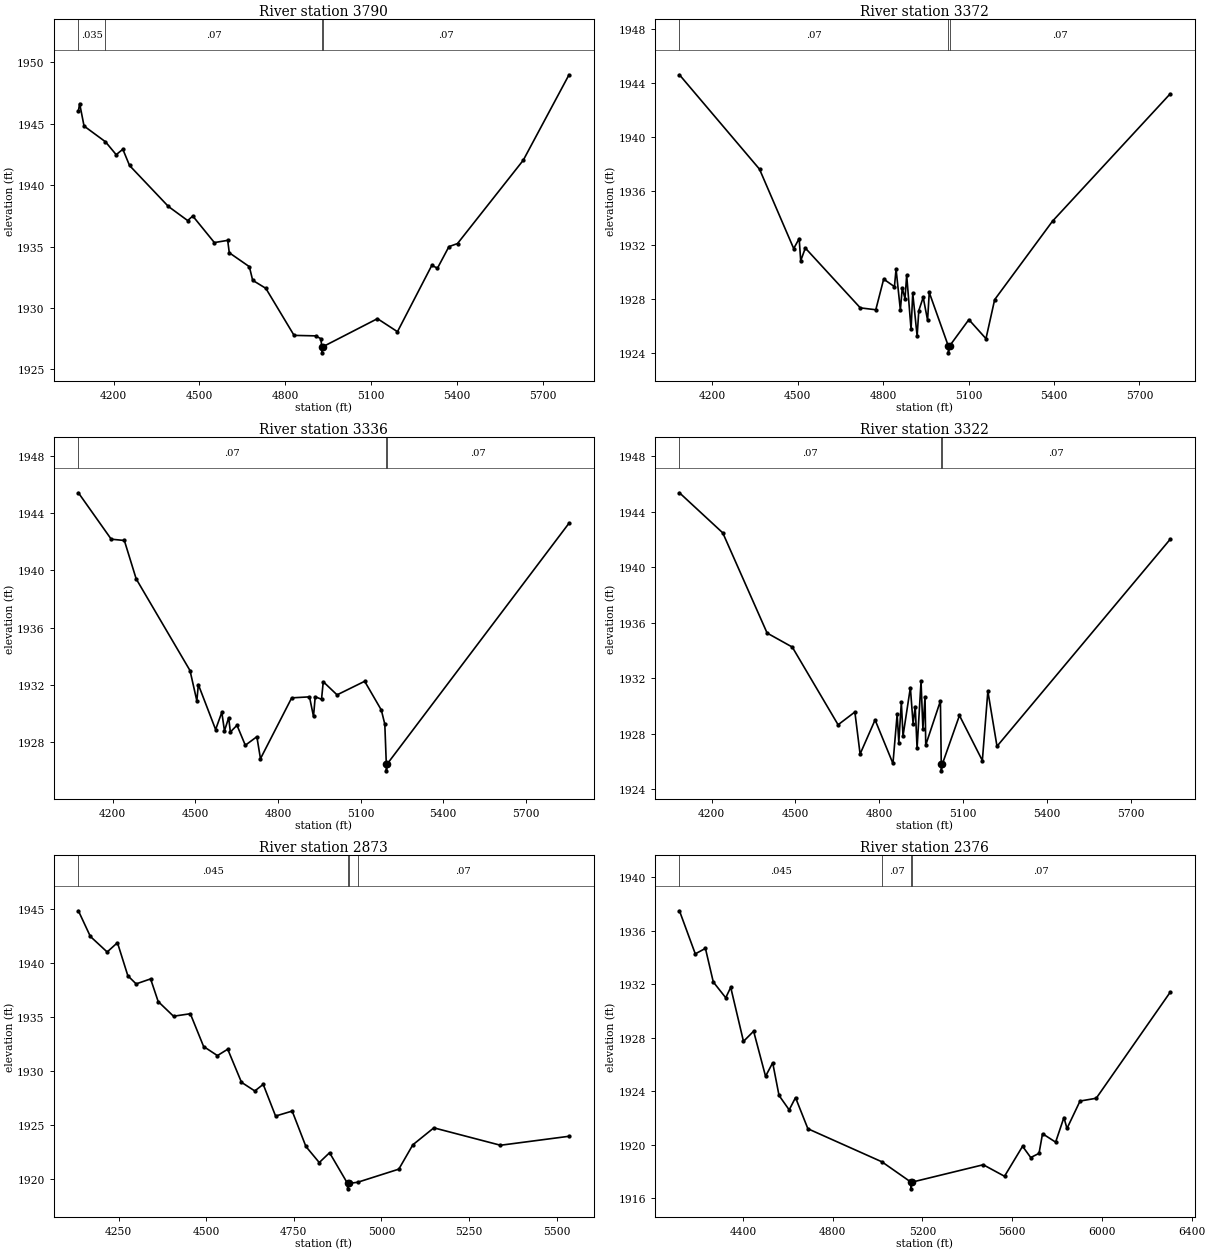
Type RM Length L Ch R = 1,3790,418,418,418
BEGIN DESCRIPTION:
Sandy Creek Trib3 4.0
END DESCRIPTION:
XS GIS Cut Line= 3
      1397777.82      6951976.16      1398148.92      6951130.61
      1398155.00      6950338.04
#Sta/Elev= 30
  4076.6 1946.02  4081.0 1946.63  4096.4 1944.80  4171.3 1943.52  4208.8 1942.47
  4232.1 1942.91  4255.5 1941.59  4391.3 1938.26  4458.8 1937.11  4476.7 1937.48
  4552.2 1935.32  4598.8 1935.50  4604.4 1934.49  4674.5 1933.36  4686.2 1932.25
  4732.1 1931.60  4831.0 1927.77  4906.6 1927.73  4924.5 1927.50  4928.0 1926.85
  4928.2 1926.35  4932.0 1926.85  5122.6 1929.13  5192.6 1928.07  5312.6 1933.46
  5332.6 1933.24  5372.6 1934.99  5402.6 1935.24  5632.6 1942.02  5792.6 1948.97
#Mann=4,-1,0
  4076.6   0.035       0  4171.3    0.07       0  4928.0    0.07       0
  4932.0    0.07       0
Bank Sta=4928,4932
Exp/Cntr=0.3,0.1

Type RM Length L Ch R = 1,3372,36,36,36
BEGIN DESCRIPTION:
Mapping XS 95370e16
END DESCRIPTION:
XS GIS Cut Line= 6
      1398175.79      6952000.10      1398421.14      6951368.77
      1398469.02      6951282.00      1398525.87      6951189.24
      1398525.87      6951006.71      1398409.41      6950361.69
#Sta/Elev= 30
  4084.5 1944.63  4365.7 1937.64  4485.8 1931.76  4505.0 1932.50  4510.4 1930.86
  4526.6 1931.80  4719.7 1927.37  4774.1 1927.23  4801.8 1929.50  4839.6 1928.94
  4845.3 1930.24  4860.4 1927.22  4867.1 1928.83  4876.7 1928.05  4882.6 1929.79
  4898.0 1925.78  4903.9 1928.45  4919.3 1925.28  4925.2 1927.17  4940.6 1928.15
  4956.0 1926.46  4961.9 1928.51  5028.9 1924.54  5029.2 1924.04  5033.0 1924.54
  5101.0 1926.50  5161.1 1925.09  5191.6 1927.98  5394.8 1933.79  5807.7 1943.21
#Mann=3,-1,0
  4084.5    0.07       0  5028.9    0.07       0  5033.0    0.07       0
Bank Sta=5028.9,5033
Exp/Cntr=0.3,0.1

Type RM Length L Ch R = 1,3336,14,14,14
BEGIN DESCRIPTION:
Mapping XS 8ade9881
END DESCRIPTION:
XS GIS Cut Line= 6
      1398187.74      6952024.08      1398445.08      6951341.84
      1398552.80      6951198.22      1398558.78      6951078.53
      1398549.81      6950997.74      1398436.10      6950336.46
#Sta/Elev= 30
  4075.7 1945.44  4194.9 1942.19  4242.5 1942.10  4285.5 1939.41  4480.9 1932.99
  4505.7 1930.87  4511.1 1932.01  4573.8 1928.86  4596.3 1930.07  4605.9 1928.77
  4621.2 1929.69  4627.3 1928.69  4651.4 1929.16  4681.6 1927.76  4723.5 1928.36
  4736.6 1926.82  4849.9 1931.08  4914.5 1931.15  4929.1 1929.78  4935.3 1931.16
  4958.2 1930.98  4964.5 1932.21  5014.6 1931.29  5114.8 1932.24  5175.2 1930.23
  5187.9 1929.24  5193.3 1926.47  5193.6 1925.97  5197.4 1926.47  5856.5 1943.31
#Mann=3,-1,0
  4075.7    0.07       0  5193.3    0.07       0  5197.4    0.07       0
Bank Sta=5193.3,5197.4
Exp/Cntr=0.3,0.1

Type RM Length L Ch R = 1,3322,449,449,449
BEGIN DESCRIPTION:
Mapping XS 9b0ede70
END DESCRIPTION:
XS GIS Cut Line= 6
      1398205.69      6952021.11      1398460.04      6951359.80
      1398525.87      6951261.05      1398561.77      6951219.16
      1398579.73      6951099.47      1398480.99      6950354.42
#Sta/Elev= 30
  4084.9 1945.36  4239.9 1942.47  4398.5 1935.25  4488.5 1934.24  4652.4 1928.64
  4712.4 1929.56  4731.1 1926.53  4784.7 1928.99  4848.6 1925.85  4863.6 1929.39
  4869.6 1927.36  4878.6 1930.29  4884.6 1927.83  4910.9 1931.32  4920.6 1928.73
  4928.3 1929.95  4934.9 1926.95  4949.1 1931.76  4955.7 1928.36  4963.4 1930.64
  4965.9 1927.18  5018.4 1930.36  5021.4 1925.82  5021.6 1925.32  5025.5 1925.82
  5086.5 1929.31  5168.4 1926.06  5188.1 1931.06  5220.8 1927.09  5839.9 1942.00
#Mann=3,-1,0
  4084.9    0.07       0  5021.4    0.07       0  5025.5    0.07       0
Bank Sta=5021.4,5025.5
Exp/Cntr=0.3,0.1

Type RM Length L Ch R = 1,2873,497,497,497
BEGIN DESCRIPTION:
Mapping XS 697b22d3
END DESCRIPTION:
XS GIS Cut Line= 3
      1398588.71      6952188.64      1398911.87      6951401.69
      1398934.17      6950852.56
#Sta/Elev= 30
  4135.2 1944.84  4169.3 1942.47  4217.3 1941.03  4246.7 1941.89  4276.4 1938.83
  4300.0 1938.08  4341.3 1938.54  4362.9 1936.45  4406.7 1935.09  4454.7 1935.32
  4492.6 1932.29  4532.0 1931.45  4561.4 1932.04  4600.7 1928.98  4638.7 1928.18
  4662.7 1928.79  4698.0 1925.86  4745.4 1926.32  4784.5 1923.05  4822.7 1921.56
  4852.1 1922.47  4903.4 1919.63  4903.6 1919.13  4907.5 1919.63  4932.5 1919.74
  5049.7 1920.95  5089.7 1923.20  5149.7 1924.77  5339.9 1923.16  5535.5 1923.99
#Mann=4,-1,0
  4135.2   0.045       0  4903.4    0.07       0  4907.5   0.045       0
  4932.5    0.07       0
Bank Sta=4903.4,4907.5
Exp/Cntr=0.3,0.1

Type RM Length L Ch R = 1,2376,514,514,514
BEGIN DESCRIPTION:
Mapping XS aa18c080
END DESCRIPTION:
XS GIS Cut Line= 4
      1398978.13      6952333.91      1399365.00      6951529.30
      1399369.61      6951049.54      1398670.21      6950632.84
#Sta/Elev= 30
  4116.8 1937.48  4187.4 1934.26  4232.6 1934.67  4267.6 1932.16  4323.1 1930.98
  4345.3 1931.76  4402.2 1927.72  4447.4 1928.48  4500.6 1925.11  4532.4 1926.12
  4560.6 1923.68  4605.9 1922.60  4634.1 1923.52  4689.3 1921.19  5019.1 1918.72
  5148.8 1917.20  5149.1 1916.70  5153.0 1917.20  5470.9 1918.50  5565.6 1917.64
  5646.1 1919.88  5682.4 1919.04  5719.4 1919.35  5735.0 1920.82  5793.4 1920.19
  5830.4 1922.03  5844.0 1921.21  5902.2 1923.26  5974.4 1923.47  6303.5 1931.38
#Mann=4,-1,0
  4116.8   0.045       0  5019.1    0.07       0  5148.8   0.045       0
  5153.0    0.07       0
Bank Sta=5148.8,5153
Exp/Cntr=0.3,0.1

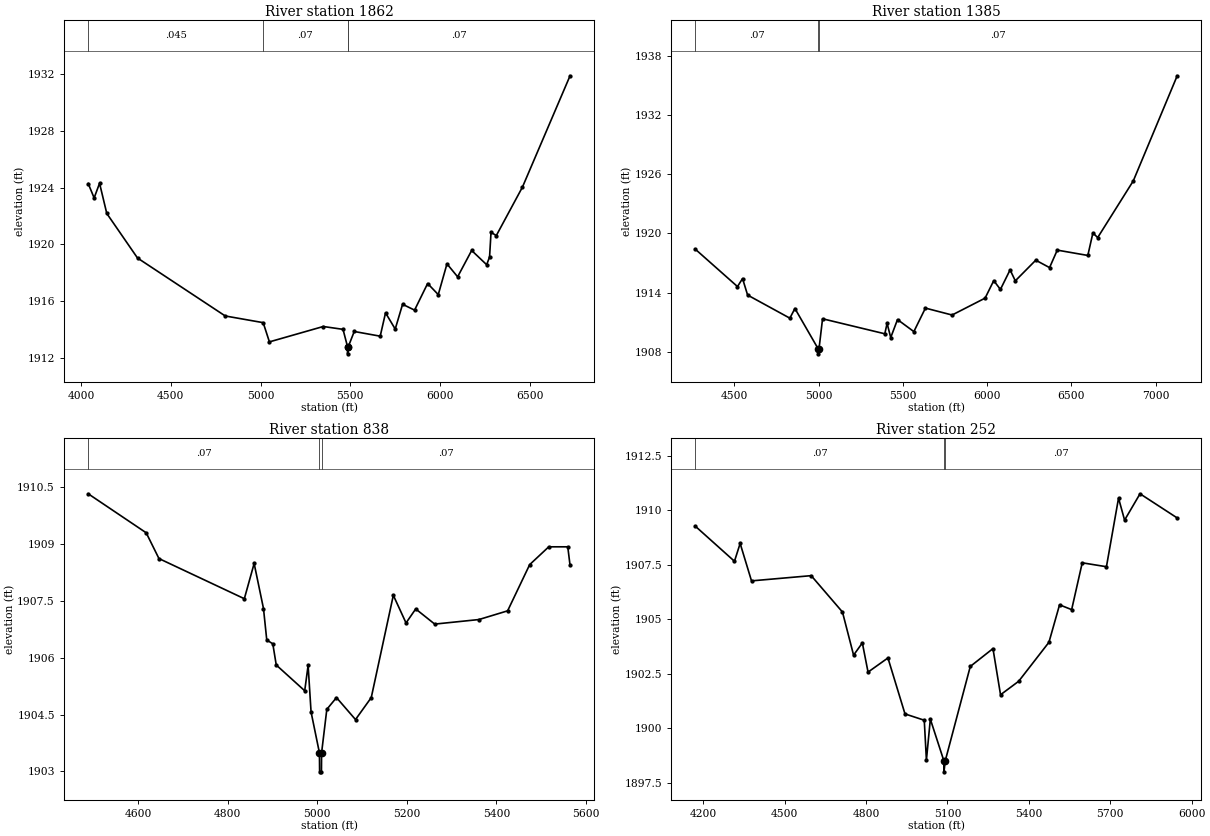
Type RM Length L Ch R = 1,1862,477,477,477
BEGIN DESCRIPTION:
Mapping XS 75ae05ad
END DESCRIPTION:
XS GIS Cut Line= 4
      1399731.74      6952490.84      1399842.45      6951539.33
      1399845.82      6951048.63      1398698.65      6950590.80
#Sta/Elev= 30
  4040.3 1924.28  4073.4 1923.27  4103.6 1924.30  4143.8 1922.18  4315.0 1919.05
  4803.6 1914.98  5014.9 1914.51  5049.6 1913.16  5349.6 1914.24  5459.6 1914.04
  5484.7 1912.82  5484.9 1912.32  5488.9 1912.82  5522.1 1913.89  5666.7 1913.56
  5696.4 1915.20  5750.3 1914.06  5791.3 1915.80  5858.1 1915.39  5930.8 1917.26
  5990.1 1916.48  6038.6 1918.64  6097.9 1917.73  6176.1 1919.58  6259.6 1918.58
  6275.8 1919.12  6283.9 1920.85  6313.5 1920.63  6458.9 1924.03  6724.1 1931.85
#Mann=4,-1,0
  4040.3   0.045       0  5014.9    0.07       0  5484.7   0.045       0
  5488.9    0.07       0
Bank Sta=5484.7,5488.9
Exp/Cntr=0.3,0.1

Type RM Length L Ch R = 1,1385,547,547,547
BEGIN DESCRIPTION:
Mapping XS a6df4794
END DESCRIPTION:
XS GIS Cut Line= 4
      1400357.11      6952317.34      1400306.24      6951605.16
      1400239.05      6951191.86      1398674.27      6950462.84
#Sta/Elev= 30
  4269.0 1918.40  4519.0 1914.62  4549.1 1915.43  4579.1 1913.76  4829.8 1911.42
  4859.8 1912.40  4998.0 1908.31  4998.4 1907.81  5002.7 1908.31  5023.8 1911.36
  5393.1 1909.84  5406.7 1910.89  5428.3 1909.46  5468.5 1911.28  5565.5 1910.06
  5634.1 1912.44  5792.3 1911.74  5988.2 1913.45  6039.5 1915.22  6079.1 1914.33
  6136.5 1916.31  6167.4 1915.20  6288.8 1917.29  6370.7 1916.54  6416.4 1918.31
  6597.7 1917.77  6627.8 1920.05  6656.2 1919.58  6867.5 1925.32  7128.0 1935.96
#Mann=3,-1,0
  4269.0    0.07       0  4998.0    0.07       0  5002.7    0.07       0
Bank Sta=4998,5002.7
Exp/Cntr=0.3,0.1

Type RM Length L Ch R = 1,838,586,586,586
BEGIN DESCRIPTION:
Mapping XS 9e4481b4
END DESCRIPTION:
XS GIS Cut Line= 3
      1401126.13      6951889.43      1400793.98      6951506.41
      1400373.05      6951122.48
#Sta/Elev= 30
  4488.0 1910.33  4617.6 1909.30  4646.1 1908.62  4836.9 1907.56  4858.8 1908.49
  4879.7 1907.30  4887.0 1906.47  4900.5 1906.37  4908.2 1905.81  4971.8 1905.13
  4979.4 1905.80  4986.0 1904.57  5004.7 1903.49  5005.1 1902.99  5009.2 1902.99
  5009.5 1903.49  5021.2 1904.64  5042.8 1904.95  5085.3 1904.37  5120.5 1904.95
  5169.8 1907.65  5198.2 1906.92  5219.8 1907.29  5262.3 1906.89  5361.0 1907.01
  5425.2 1907.24  5474.5 1908.46  5517.1 1908.93  5559.6 1908.93  5564.7 1908.44
#Mann=3,-1,0
  4488.0    0.07       0  5004.7    0.07       0  5009.5    0.07       0
Bank Sta=5004.7,5009.5
Exp/Cntr=0.3,0.1

Type RM Length L Ch R = 1,252,0,0,0
BEGIN DESCRIPTION:
Sandy Creek Trib3 1.0
END DESCRIPTION:
XS GIS Cut Line= 3
      1401224.86      6951805.64      1400978.06      6951014.12
      1400132.68      6950587.79
#Sta/Elev= 30
  4170.9 1909.27  4315.1 1907.66  4336.0 1908.48  4377.9 1906.76  4597.9 1907.00
  4713.1 1905.33  4754.1 1903.35  4786.4 1903.91  4807.4 1902.57  4880.7 1903.22
  4943.6 1900.65  5014.6 1900.36  5022.5 1898.53  5037.0 1900.41  5087.0 1898.49
  5087.3 1897.99  5091.8 1898.49  5184.2 1902.83  5267.8 1903.65  5295.7 1901.53
  5362.6 1902.15  5474.1 1903.94  5513.2 1905.66  5557.8 1905.44  5596.8 1907.59
  5686.0 1907.41  5730.6 1910.56  5752.9 1909.55  5809.8 1910.76  5946.8 1909.65
#Mann=3,-1,0
  4170.9    0.07       0  5087.0    0.07       0  5091.8    0.07       0
Bank Sta=5087,5091.8
Exp/Cntr=0.3,0.1

Chan Stop Cuts=-1