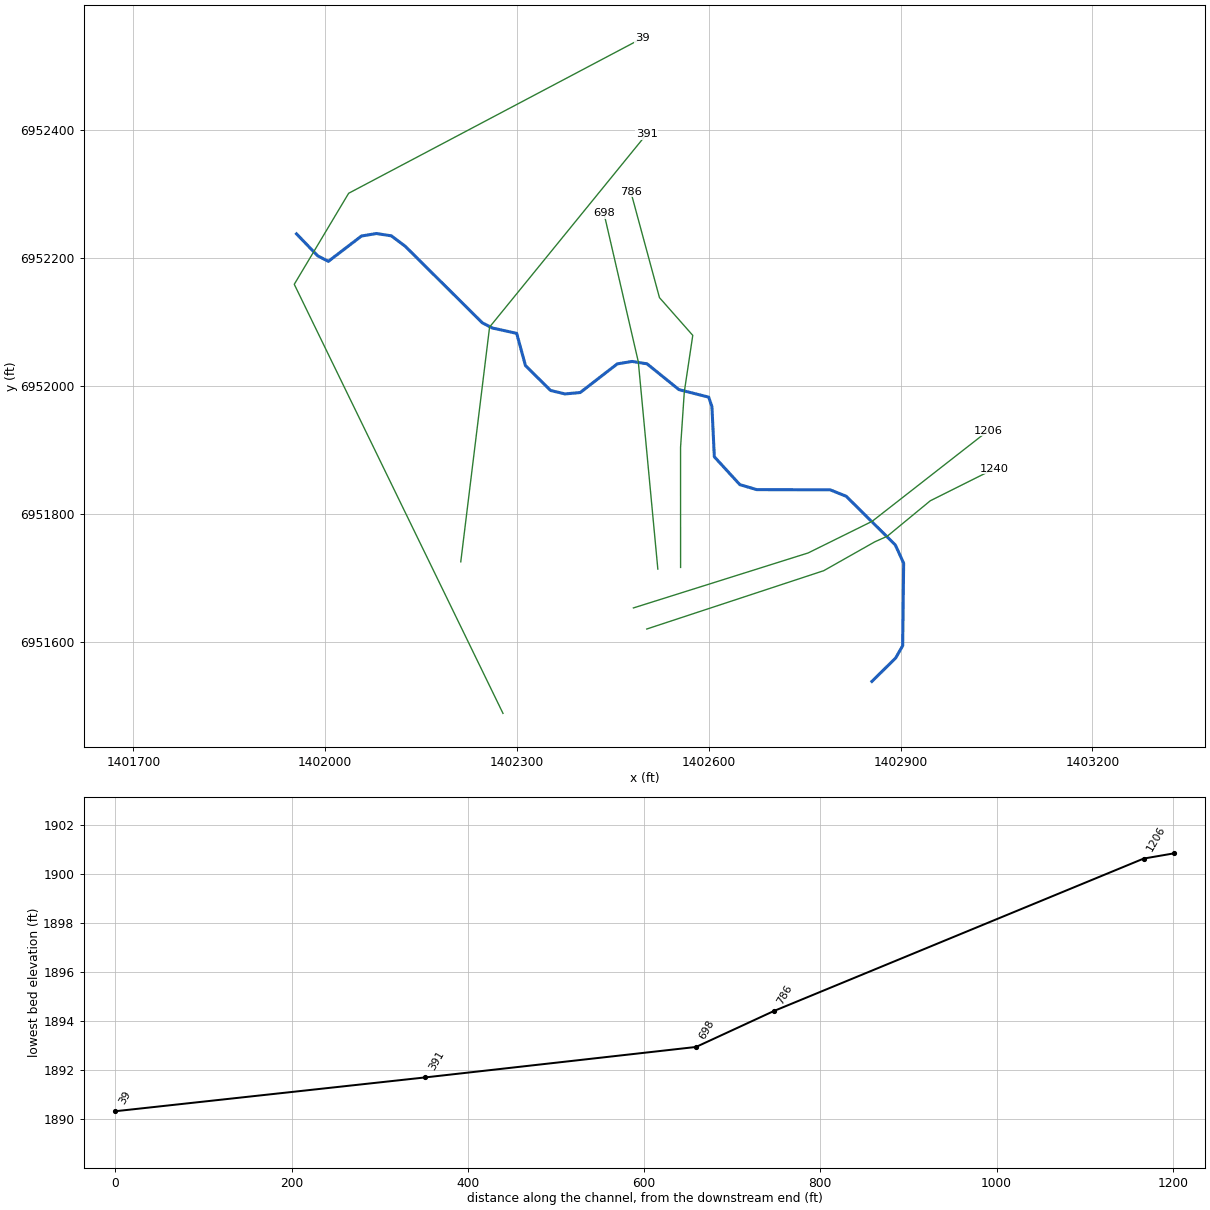
--- Sandy Creek Trib4.prj (project) ---

Proj Title=Sandy Creek Trib4 Base Level Engineering
Current Plan=p01
Default Exp/Contr=0.3,0.1
English Units
Geom File=g01
Flow File=f01
Plan File=p01
BEGIN DESCRIPTION:
Sandy Creek Trib4
END DESCRIPTION:

--- Sandy Creek Trib4.p01 (plan) ---

Plan Title=Multiple Run
Short Identifier=Multiple
Geom File=g01
Flow File=f01
Subcritical Flow
K Sum by GR= 0
Std Step Tol= 0.01
Critical Tol= 0.01
Num of Std Step Trials= 20
Max Error Tol= 0.3
Flow Tol Ratio= 0.001
Split Flow NTrial= 30
Split Flow Tol= 0.02
Split Flow Ratio= 0.02
Log Output Level= 0
Friction Slope Method= 1
Unsteady Friction Slope Method= 2
Unsteady Bridges Friction Slope Method= 1
Parabolic Critical Depth
Global Vel Dist=  1 , 1 , 1
Global Log Level= 0
CheckData=True
Encroach Param= -1, 0, 0, 0
BEGIN DESCRIPTION:
Multiple Run
END DESCRIPTION:

--- Sandy Creek Trib4.f01 (steady flow) ---

Flow Title=Multiple
Number of Profiles=7
Profile Names=10-year,25-year,50-year,1pct_min,100-year,1pct_plu,500-year
River Rch & RM= Sandy Creek Trib,Reach-1,1240
     310     443     555     346     690    1377    1081
Boundary for River Rch & Prof#=Sandy Creek Trib,Reach-1,1
Up Type=0
Dn Type=3
Dn Slope=0.005
Boundary for River Rch & Prof#=Sandy Creek Trib,Reach-1,2
Up Type=0
Dn Type=3
Dn Slope=0.005
Boundary for River Rch & Prof#=Sandy Creek Trib,Reach-1,3
Up Type=0
Dn Type=3
Dn Slope=0.005
Boundary for River Rch & Prof#=Sandy Creek Trib,Reach-1,4
Up Type=0
Dn Type=3
Dn Slope=0.005
Boundary for River Rch & Prof#=Sandy Creek Trib,Reach-1,5
Up Type=0
Dn Type=3
Dn Slope=0.005
Boundary for River Rch & Prof#=Sandy Creek Trib,Reach-1,6
Up Type=0
Dn Type=3
Dn Slope=0.005
Boundary for River Rch & Prof#=Sandy Creek Trib,Reach-1,7
Up Type=0
Dn Type=3
Dn Slope=0.005

--- Sandy Creek Trib4.g01 (geometry) ---

Geom Title=Existing Conditions

River Reach=Sandy Creek Trib,Reach-1
Reach XY= 30
      1402855.00      6951538.00      1402892.09      6951574.50
      1402903.12      6951593.79      1402904.64      6951722.84
      1402891.65      6951751.35      1402814.82      6951827.53
      1402789.84      6951837.60      1402674.88      6951837.93
      1402648.48      6951845.68      1402608.54      6951889.32
      1402604.78      6951967.74      1402599.75      6951982.56
      1402553.20      6951994.34      1402503.31      6952034.67
      1402480.01      6952038.41      1402456.73      6952034.60
      1402398.84      6951989.80      1402375.03      6951987.58
      1402352.47      6951993.02      1402313.17      6952031.87
      1402299.37      6952082.34      1402261.43      6952090.69
      1402245.58      6952098.89      1402125.09      6952218.57
      1402103.36      6952234.86      1402080.01      6952238.45
      1402056.64      6952234.57      1402004.88      6952194.95
      1401988.17      6952203.56      1401955.00      6952238.00

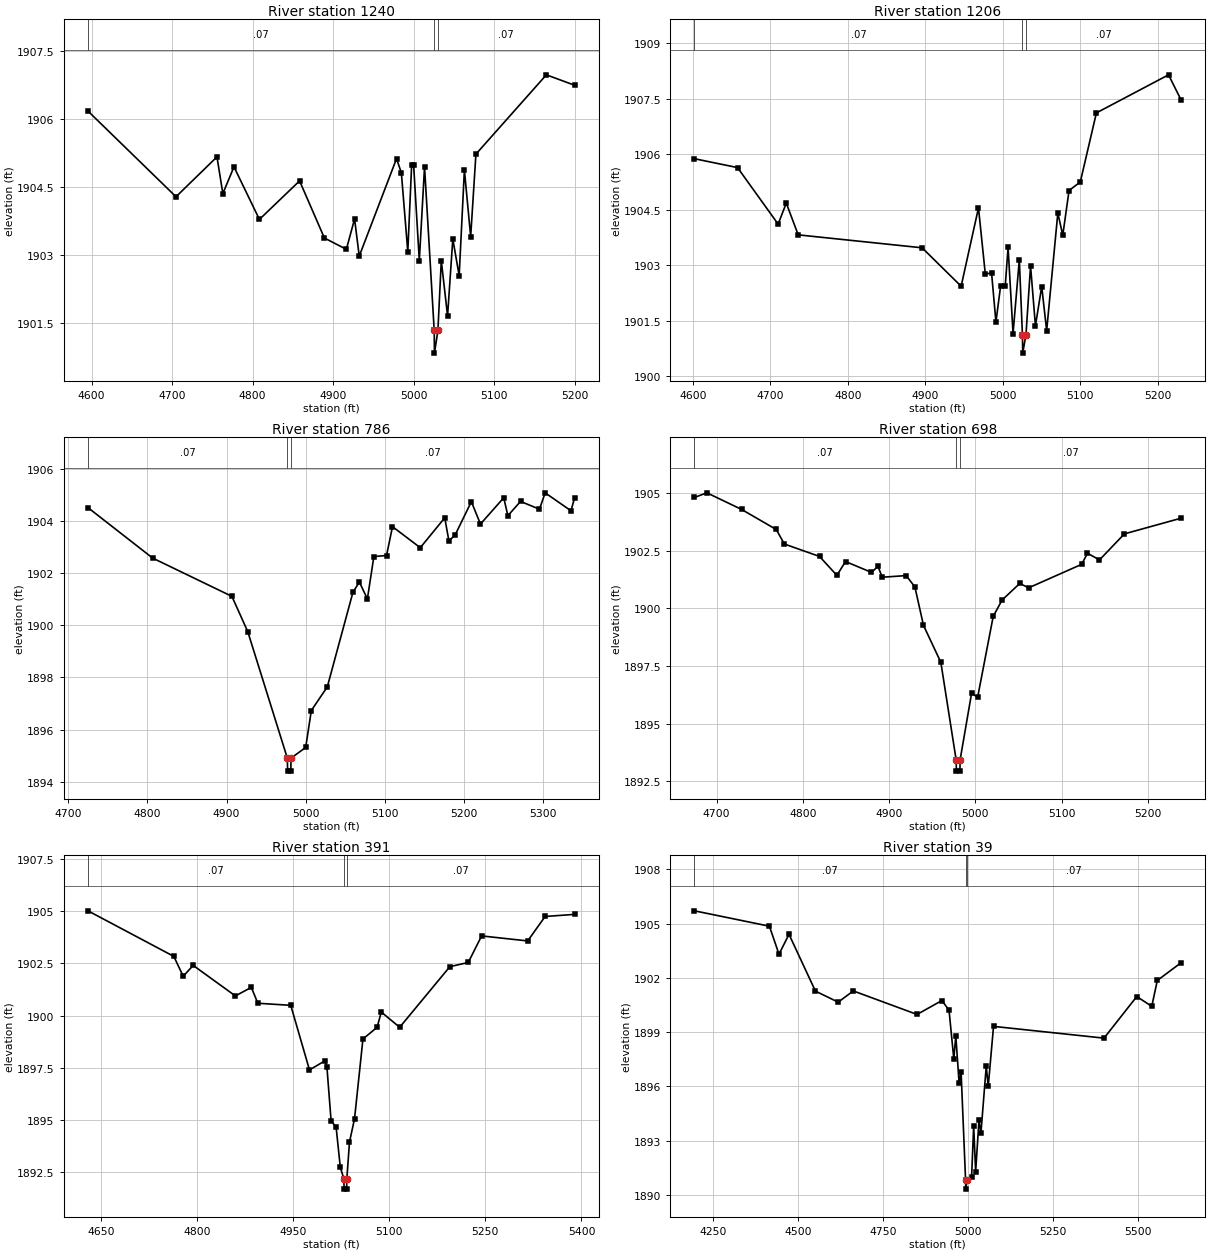
Type RM Length L Ch R = 1,1240,34,34,34
BEGIN DESCRIPTION:
Sandy Creek Trib4 6.0
END DESCRIPTION:
XS GIS Cut Line= 6
      1402502.83      6951619.91      1402779.67      6951711.15
      1402859.53      6951756.29      1402878.86      6951764.94
      1402946.34      6951820.52      1403047.03      6951870.87
#Sta/Elev= 30
  4595.6 1906.17  4704.9 1904.28  4755.8 1905.16  4763.1 1904.35  4776.9 1904.94
  4808.5 1903.78  4858.4 1904.63  4889.2 1903.37  4916.5 1903.12  4926.7 1903.79
  4932.5 1902.97  4978.8 1905.12  4984.8 1904.81  4992.8 1903.07  4997.6 1904.99
  5000.0 1904.99  5007.1 1902.87  5013.6 1904.94  5025.6 1901.33  5025.9 1900.83
  5030.2 1901.33  5034.4 1902.87  5042.2 1901.65  5048.7 1903.35  5056.6 1902.54
  5063.1 1904.87  5070.9 1903.40  5077.4 1905.22  5164.9 1906.97  5200.0 1906.74
#Mann=3,-1,0
  4595.6    0.07       0  5025.6    0.07       0  5030.2    0.07       0
Bank Sta=5025.6,5030.2
Exp/Cntr=0.3,0.1

Type RM Length L Ch R = 1,1206,420,420,420
BEGIN DESCRIPTION:
Sandy Creek Trib4 5.0
END DESCRIPTION:
XS GIS Cut Line= 4
      1402482.01      6951652.90      1402755.36      6951738.93
      1402855.35      6951788.35      1403036.62      6951929.90
#Sta/Elev= 30
  4601.9 1905.88  4657.5 1905.64  4709.9 1904.11  4720.4 1904.68  4735.8 1903.82
  4895.7 1903.47  4946.1 1902.43  4968.5 1904.55  4977.3 1902.76  4985.4 1902.79
  4991.0 1901.46  4997.0 1902.43  5003.0 1902.43  5006.7 1903.48  5013.1 1901.15
  5021.2 1903.15  5025.2 1901.12  5025.6 1900.62  5029.8 1901.12  5035.7 1902.98
  5042.0 1901.36  5050.1 1902.42  5056.5 1901.23  5070.9 1904.41  5077.3 1903.81
  5085.4 1905.02  5099.9 1905.25  5120.7 1907.12  5213.8 1908.15  5230.0 1907.47
#Mann=3,-1,0
  4601.9    0.07       0  5025.2    0.07       0  5029.8    0.07       0
Bank Sta=5025.2,5029.8
Exp/Cntr=0.3,0.1

Type RM Length L Ch R = 1,786,88,88,88
BEGIN DESCRIPTION:
Sandy Creek Trib4 4.0
END DESCRIPTION:
XS GIS Cut Line= 6
      1402555.77      6951716.26      1402555.71      6951903.86
      1402561.59      6951990.96      1402574.81      6952079.20
      1402522.73      6952138.23      1402477.85      6952303.91
#Sta/Elev= 30
  4725.1 1904.53  4806.8 1902.59  4906.8 1901.12  4926.9 1899.76  4976.8 1894.90
  4977.2 1894.40  4981.2 1894.40  4981.5 1894.90  5000.0 1895.31  5007.1 1896.73
  5027.3 1897.64  5059.7 1901.28  5067.8 1901.67  5077.9 1901.02  5086.1 1902.65
  5102.1 1902.69  5109.6 1903.80  5144.7 1902.99  5175.6 1904.14  5180.8 1903.26
  5188.4 1903.46  5209.2 1904.76  5220.7 1903.90  5250.1 1904.91  5255.3 1904.22
  5271.3 1904.77  5295.2 1904.47  5302.4 1905.10  5335.0 1904.41  5339.6 1904.91
#Mann=3,-1,0
  4725.1    0.07       0  4976.8    0.07       0  4981.5    0.07       0
Bank Sta=4976.8,4981.5
Exp/Cntr=0.3,0.1

Type RM Length L Ch R = 1,698,307,307,307
BEGIN DESCRIPTION:
Sandy Creek Trib4 3.0
END DESCRIPTION:
XS GIS Cut Line= 3
      1402520.18      6951713.66      1402489.63      6952037.92
      1402435.92      6952270.19
#Sta/Elev= 30
  4674.3 1904.81  4688.7 1905.01  4728.9 1904.29  4769.1 1903.42  4778.5 1902.79
  4819.3 1902.25  4839.4 1901.43  4849.4 1902.03  4879.5 1901.56  4887.0 1901.82
  4892.0 1901.35  4919.7 1901.42  4929.8 1900.93  4939.8 1899.26  4959.9 1897.66
  4977.6 1893.44  4978.0 1892.94  4982.0 1892.94  4982.3 1893.44  4995.5 1896.31
  5002.6 1896.15  5020.6 1899.65  5030.9 1900.36  5051.4 1901.08  5061.7 1900.89
  5123.2 1901.91  5129.9 1902.39  5143.8 1902.10  5172.7 1903.23  5238.4 1903.91
#Mann=3,-1,0
  4674.3    0.07       0  4977.6    0.07       0  4982.3    0.07       0
Bank Sta=4977.6,4982.3
Exp/Cntr=0.3,0.1

Type RM Length L Ch R = 1,391,352,352,352
BEGIN DESCRIPTION:
Sandy Creek Trib4 2.0
END DESCRIPTION:
XS GIS Cut Line= 3
      1402211.97      6951725.08      1402257.01      6952092.12
      1402502.73      6952394.07
#Sta/Elev= 30
  4630.2 1905.01  4764.1 1902.83  4778.7 1901.88  4794.3 1902.40  4860.1 1900.94
  4885.0 1901.35  4895.1 1900.59  4946.5 1900.49  4975.7 1897.40  5000.0 1897.84
  5002.9 1897.54  5009.4 1894.98  5017.3 1894.65  5023.8 1892.74  5029.3 1892.20
  5029.7 1891.70  5033.7 1891.70  5034.0 1892.20  5038.1 1893.95  5046.0 1895.07
  5059.1 1898.88  5081.2 1899.44  5087.7 1900.17  5116.4 1899.44  5194.7 1902.34
  5223.4 1902.54  5244.2 1903.81  5316.1 1903.57  5343.3 1904.74  5389.3 1904.84
#Mann=3,-1,0
  4630.2    0.07       0  5029.3    0.07       0  5034.0    0.07       0
Bank Sta=5029.3,5034
Exp/Cntr=0.3,0.1

Type RM Length L Ch R = 1,39,0,0,0
BEGIN DESCRIPTION:
Sandy Creek Trib4 1.0
END DESCRIPTION:
XS GIS Cut Line= 4
      1402277.99      6951487.98      1401951.55      6952159.06
      1402036.61      6952301.43      1402495.32      6952543.76
#Sta/Elev= 30
  4194.8 1905.71  4415.2 1904.86  4443.3 1903.31  4472.8 1904.41  4550.5 1901.27
  4617.4 1900.66  4661.9 1901.28  4849.3 1899.98  4922.5 1900.75  4943.4 1900.21
  4957.4 1897.52  4963.3 1898.80  4973.0 1896.17  4978.8 1896.81  4992.0 1890.82
  4992.4 1890.32  4996.7 1890.82  5009.7 1890.97  5015.8 1893.82  5021.6 1891.29
  5031.4 1894.12  5037.2 1893.43  5052.8 1897.12  5058.6 1896.00  5074.2 1899.32
  5399.1 1898.67  5495.4 1900.97  5539.5 1900.43  5555.8 1901.86  5625.7 1902.84
#Mann=3,-1,0
  4194.8    0.07       0  4992.0    0.07       0  4996.7    0.07       0
Bank Sta=4992,4996.7
Exp/Cntr=0.3,0.1

Chan Stop Cuts=-1