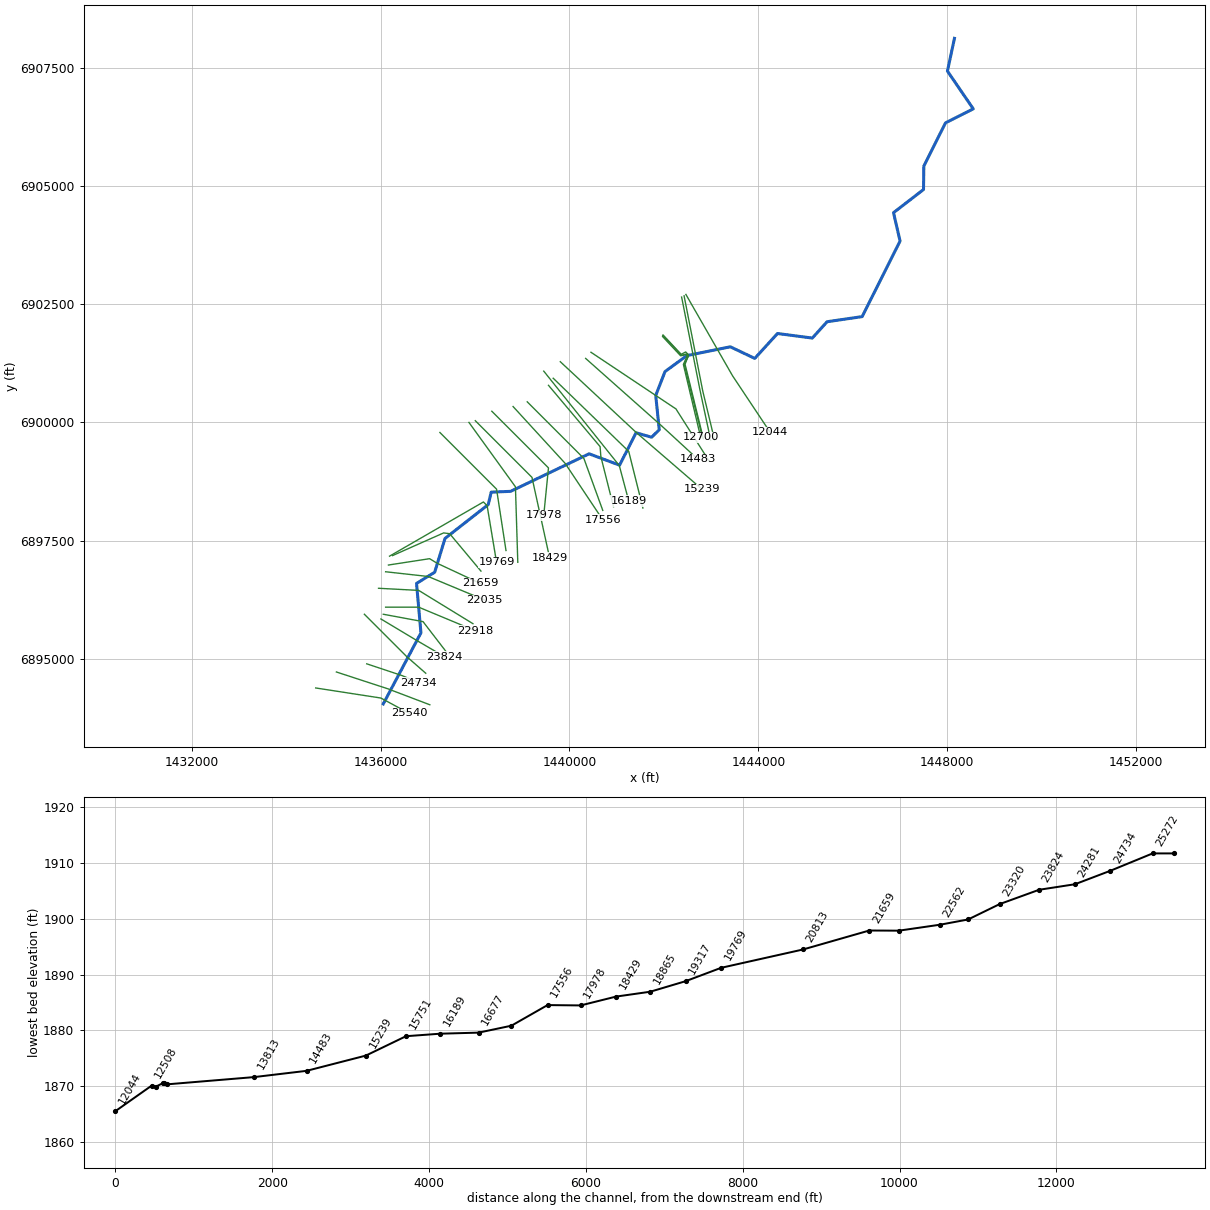
--- South Fork.prj (project) ---

Proj Title=South Fork Base Level Engineering
Current Plan=p01
Default Exp/Contr=0.3,0.1
English Units
Geom File=g01
Flow File=f01
Plan File=p01
BEGIN DESCRIPTION:
South Fork
END DESCRIPTION:

--- South Fork.p01 (plan) ---

Plan Title=Multiple Run
Short Identifier=Multiple
Geom File=g01
Flow File=f01
Subcritical Flow
K Sum by GR= 0
Std Step Tol= 0.01
Critical Tol= 0.01
Num of Std Step Trials= 20
Max Error Tol= 0.3
Flow Tol Ratio= 0.001
Split Flow NTrial= 30
Split Flow Tol= 0.02
Split Flow Ratio= 0.02
Log Output Level= 0
Friction Slope Method= 1
Unsteady Friction Slope Method= 2
Unsteady Bridges Friction Slope Method= 1
Parabolic Critical Depth
Global Vel Dist=  1 , 1 , 1
Global Log Level= 0
CheckData=True
Encroach Param= -1, 0, 0, 0
BEGIN DESCRIPTION:
Multiple Run
END DESCRIPTION:

--- South Fork.f01 (steady flow) ---

Flow Title=Multiple
Number of Profiles=7
Profile Names=10-year,25-year,50-year,1pct_min,100-year,1pct_plu,500-year
River Rch & RM= South Fork,Reach-1,25540
     283     402     502     312     623    1244     972
River Rch & RM= South Fork,Reach-1,23824
     372     534     672     420     839    1674    1323
River Rch & RM= South Fork,Reach-1,17978
     757    1121    1440     917    1830    3651    2994
River Rch & RM= South Fork,Reach-1,8121
     790    1161    1485     941    1878    3746    3041
River Rch & RM= South Fork,Reach-1,742
     934    1383    1778    1132    2258    4506    3691
Boundary for River Rch & Prof#=South Fork,Reach-1,1
Up Type=0
Dn Type=3
Dn Slope=0.005
Boundary for River Rch & Prof#=South Fork,Reach-1,2
Up Type=0
Dn Type=3
Dn Slope=0.005
Boundary for River Rch & Prof#=South Fork,Reach-1,3
Up Type=0
Dn Type=3
Dn Slope=0.005
Boundary for River Rch & Prof#=South Fork,Reach-1,4
Up Type=0
Dn Type=3
Dn Slope=0.005
Boundary for River Rch & Prof#=South Fork,Reach-1,5
Up Type=0
Dn Type=3
Dn Slope=0.005
Boundary for River Rch & Prof#=South Fork,Reach-1,6
Up Type=0
Dn Type=3
Dn Slope=0.005
Boundary for River Rch & Prof#=South Fork,Reach-1,7
Up Type=0
Dn Type=3
Dn Slope=0.005

--- South Fork.g01 (geometry) ---

Geom Title=Existing Conditions

River Reach=South Fork,Reach-1
Reach XY= 30
      1436055.00      6894038.00      1436853.03      6895543.89
      1436760.08      6896590.86      1437144.53      6896828.18
      1437363.14      6897544.06      1438278.84      6898261.12
      1438341.36      6898524.56      1438753.53      6898541.55
      1440415.44      6899336.96      1441061.19      6899095.75
      1441409.81      6899782.44      1441739.71      6899687.82
      1441901.46      6899846.50      1441827.03      6900573.31
      1442023.59      6901079.12      1442485.89      6901416.67
      1443406.82      6901603.79      1443924.57      6901357.55
      1444406.65      6901884.90      1445144.37      6901788.55
      1445456.46      6902134.46      1446199.92      6902243.04
      1447003.05      6903843.97      1446864.13      6904444.74
      1447499.58      6904935.33      1447506.54      6905432.15
      1447965.75      6906347.68      1448553.50      6906643.82
      1448006.57      6907443.65      1448155.00      6908138.00

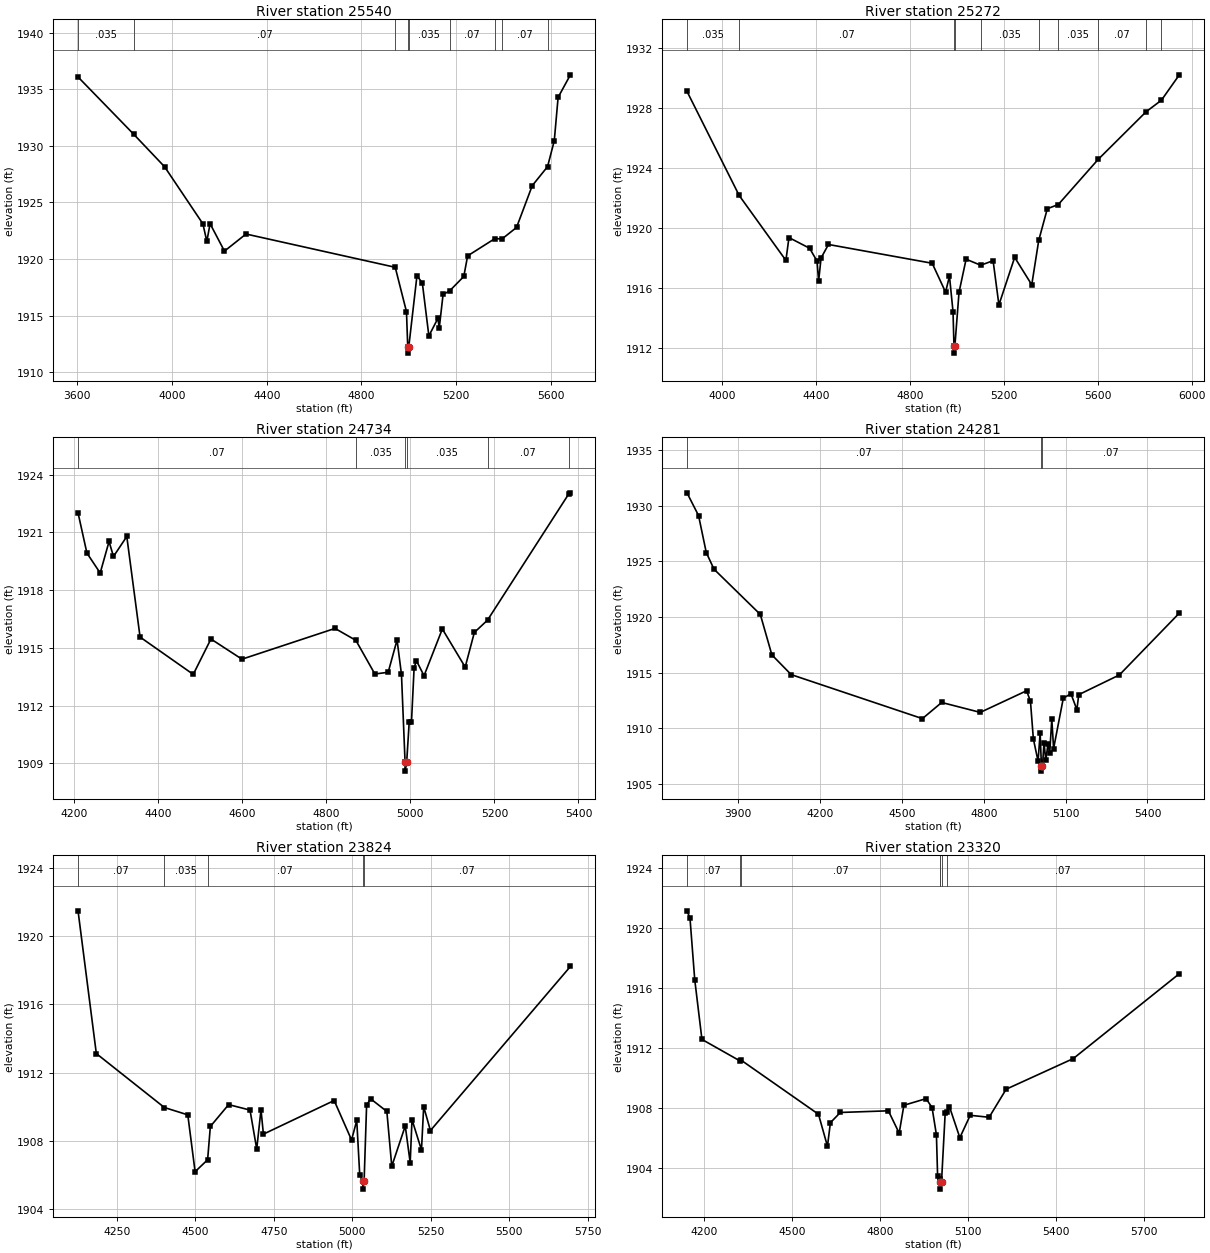
Type RM Length L Ch R = 1,25540,268,268,268
BEGIN DESCRIPTION:
South Fork 39.0
END DESCRIPTION:
XS GIS Cut Line= 3
      1434623.63      6894376.23      1436004.57      6894163.04
      1436605.03      6893837.98
#Sta/Elev= 30
  3602.7 1936.08  3837.5 1931.03  3968.4 1928.15  4130.2 1923.11  4146.8 1921.56
  4160.6 1923.12  4221.3 1920.70  4312.4 1922.21  4942.8 1919.27  4990.3 1915.35
  4995.7 1912.19  4995.9 1911.69  4999.7 1912.19  5034.6 1918.53  5057.3 1917.88
  5084.9 1913.21  5123.0 1914.76  5128.7 1913.90  5144.9 1916.87  5172.2 1917.18
  5232.4 1918.46  5248.6 1920.28  5363.4 1921.80  5394.3 1921.78  5455.3 1922.79
  5521.6 1926.48  5586.3 1928.16  5614.7 1930.45  5630.9 1934.28  5682.8 1936.27
#Mann=9,-1,0
  3602.7   0.035       0  3837.5    0.07       0  4942.8   0.035       0
  4995.7   0.035       0  4999.7   0.035       0  5172.2    0.07       0
  5363.4   0.035       0  5394.3    0.07       0  5586.3   0.035       0
Bank Sta=4995.7,4999.7
Exp/Cntr=0.3,0.1

Type RM Length L Ch R = 1,25272,538,538,538
BEGIN DESCRIPTION:
Mapping XS 52a28ae8
END DESCRIPTION:
XS GIS Cut Line= 3
      1435062.06      6894714.75      1436151.44      6894358.86
      1437040.62      6894020.54
#Sta/Elev= 30
  3850.3 1929.11  4072.7 1922.18  4271.7 1917.86  4284.7 1919.38  4372.6 1918.67
  4404.5 1917.81  4411.0 1916.47  4421.5 1918.02  4453.0 1918.92  4894.9 1917.67
  4951.8 1915.75  4968.5 1916.81  4983.6 1914.45  4987.6 1912.19  4987.8 1911.69
  4991.6 1912.19  5009.2 1915.74  5039.3 1917.94  5101.5 1917.54  5154.3 1917.84
  5179.1 1914.90  5246.2 1918.06  5319.0 1916.24  5348.7 1919.19  5385.3 1921.30
  5432.1 1921.58  5601.8 1924.58  5806.0 1927.75  5871.3 1928.52  5947.7 1930.21
#Mann=10,-1,0
  3850.3   0.035       0  4072.7    0.07       0  4987.6    0.07       0
  4991.6    0.07       0  5101.5   0.035       0  5348.7    0.07       0
  5432.1   0.035       0  5601.8    0.07       0  5806.0   0.035       0
  5871.3    0.07       0
Bank Sta=4987.6,4991.6
Exp/Cntr=0.3,0.1

Type RM Length L Ch R = 1,24734,453,453,453
BEGIN DESCRIPTION:
South Fork 38.0
END DESCRIPTION:
XS GIS Cut Line= 3
      1435704.99      6894888.00      1436455.00      6894638.00
      1436805.03      6894487.99
#Sta/Elev= 30
  4209.4 1922.02  4230.5 1919.93  4262.1 1918.89  4283.2 1920.53  4293.7 1919.75
  4325.4 1920.79  4357.0 1915.56  4483.5 1913.62  4525.6 1915.46  4599.4 1914.41
  4820.8 1916.01  4870.4 1915.39  4915.6 1913.64  4947.3 1913.73  4968.4 1915.41
  4978.9 1913.62  4987.4 1909.09  4987.7 1908.59  4991.4 1909.09  4997.3 1911.14
  5002.7 1911.14  5009.0 1913.97  5014.5 1914.33  5032.6 1913.55  5076.1 1915.98
  5130.5 1914.00  5152.3 1915.80  5183.6 1916.44  5377.4 1923.02  5380.8 1923.06
#Mann=6,-1,0
  4209.4    0.07       0  4870.4   0.035       0  4987.4   0.035       0
  4991.4   0.035       0  5183.6    0.07       0  5377.4   0.035       0
Bank Sta=4987.4,4991.4
Exp/Cntr=0.3,0.1

Type RM Length L Ch R = 1,24281,457,457,457
BEGIN DESCRIPTION:
South Fork 37.0
END DESCRIPTION:
XS GIS Cut Line= 3
      1435655.00      6895938.00      1436555.00      6895038.00
      1436955.00      6894688.00
#Sta/Elev= 30
  3712.6 1931.14  3755.0 1929.10  3783.3 1925.78  3811.6 1924.29  3981.3 1920.23
  4023.7 1916.60  4094.4 1914.83  4575.3 1910.88  4646.0 1912.33  4787.4 1911.44
  4957.1 1913.38  4971.3 1912.44  4981.9 1909.07  4999.2 1907.06  5006.8 1909.59
  5011.4 1906.67  5011.6 1906.17  5015.4 1906.67  5021.0 1908.72  5027.6 1907.13
  5035.2 1908.58  5041.9 1907.79  5049.5 1910.83  5056.1 1908.20  5091.7 1912.72
  5119.7 1913.11  5141.5 1911.68  5148.2 1913.03  5297.2 1914.80  5516.9 1920.35
#Mann=3,-1,0
  3712.6    0.07       0  5011.4    0.07       0  5015.4    0.07       0
Bank Sta=5011.4,5015.4
Exp/Cntr=0.3,0.1

Type RM Length L Ch R = 1,23824,504,504,504
BEGIN DESCRIPTION:
South Fork 36.0
END DESCRIPTION:
XS GIS Cut Line= 3
      1436005.03      6895837.98      1436755.00      6895388.00
      1437354.98      6895038.01
#Sta/Elev= 30
  4125.8 1921.48  4184.1 1913.12  4401.0 1909.96  4475.6 1909.53  4498.9 1906.20
  4538.8 1906.90  4547.5 1908.85  4605.8 1910.13  4673.9 1909.81  4695.3 1907.53
  4708.9 1909.83  4716.6 1908.40  4942.1 1910.37  4997.5 1908.06  5014.1 1909.20
  5023.6 1906.01  5033.6 1905.68  5033.8 1905.18  5037.6 1905.68  5045.5 1910.10
  5058.3 1910.47  5110.0 1909.73  5125.7 1906.52  5168.7 1908.88  5184.4 1906.73
  5190.2 1909.25  5220.4 1907.47  5227.4 1910.01  5248.9 1908.61  5695.0 1918.22
#Mann=5,-1,0
  4125.8    0.07       0  4401.0   0.035       0  4538.8    0.07       0
  5033.6    0.07       0  5037.6    0.07       0
Bank Sta=5033.6,5037.6
Exp/Cntr=0.3,0.1

Type RM Length L Ch R = 1,23320,402,402,402
BEGIN DESCRIPTION:
South Fork 35.0
END DESCRIPTION:
XS GIS Cut Line= 3
      1436054.97      6895938.01      1436897.26      6895781.54
      1437396.67      6895132.31
#Sta/Elev= 30
  4143.3 1921.16  4153.5 1920.68  4169.7 1916.57  4194.2 1912.59  4322.4 1911.17
  4326.5 1911.22  4590.9 1907.60  4621.4 1905.47  4631.5 1907.04  4665.3 1907.72
  4828.8 1907.83  4865.5 1906.34  4881.6 1908.20  4957.0 1908.64  4977.4 1908.05
  4992.3 1906.23  4996.3 1903.51  5004.0 1903.29  5005.5 1903.11  5005.8 1902.61
  5009.7 1903.11  5022.1 1907.67  5026.9 1907.73  5036.7 1908.10  5072.0 1906.04
  5107.3 1907.53  5171.7 1907.40  5229.7 1909.27  5458.0 1911.31  5819.1 1916.97
#Mann=7,-1,0
  4143.3    0.07       0  4322.4   0.035       0  4326.5    0.07       0
  5004.0   0.035       0  5005.5    0.07       0  5009.7   0.035       0
  5026.9    0.07       0
Bank Sta=5005.5,5009.7
Exp/Cntr=0.3,0.1

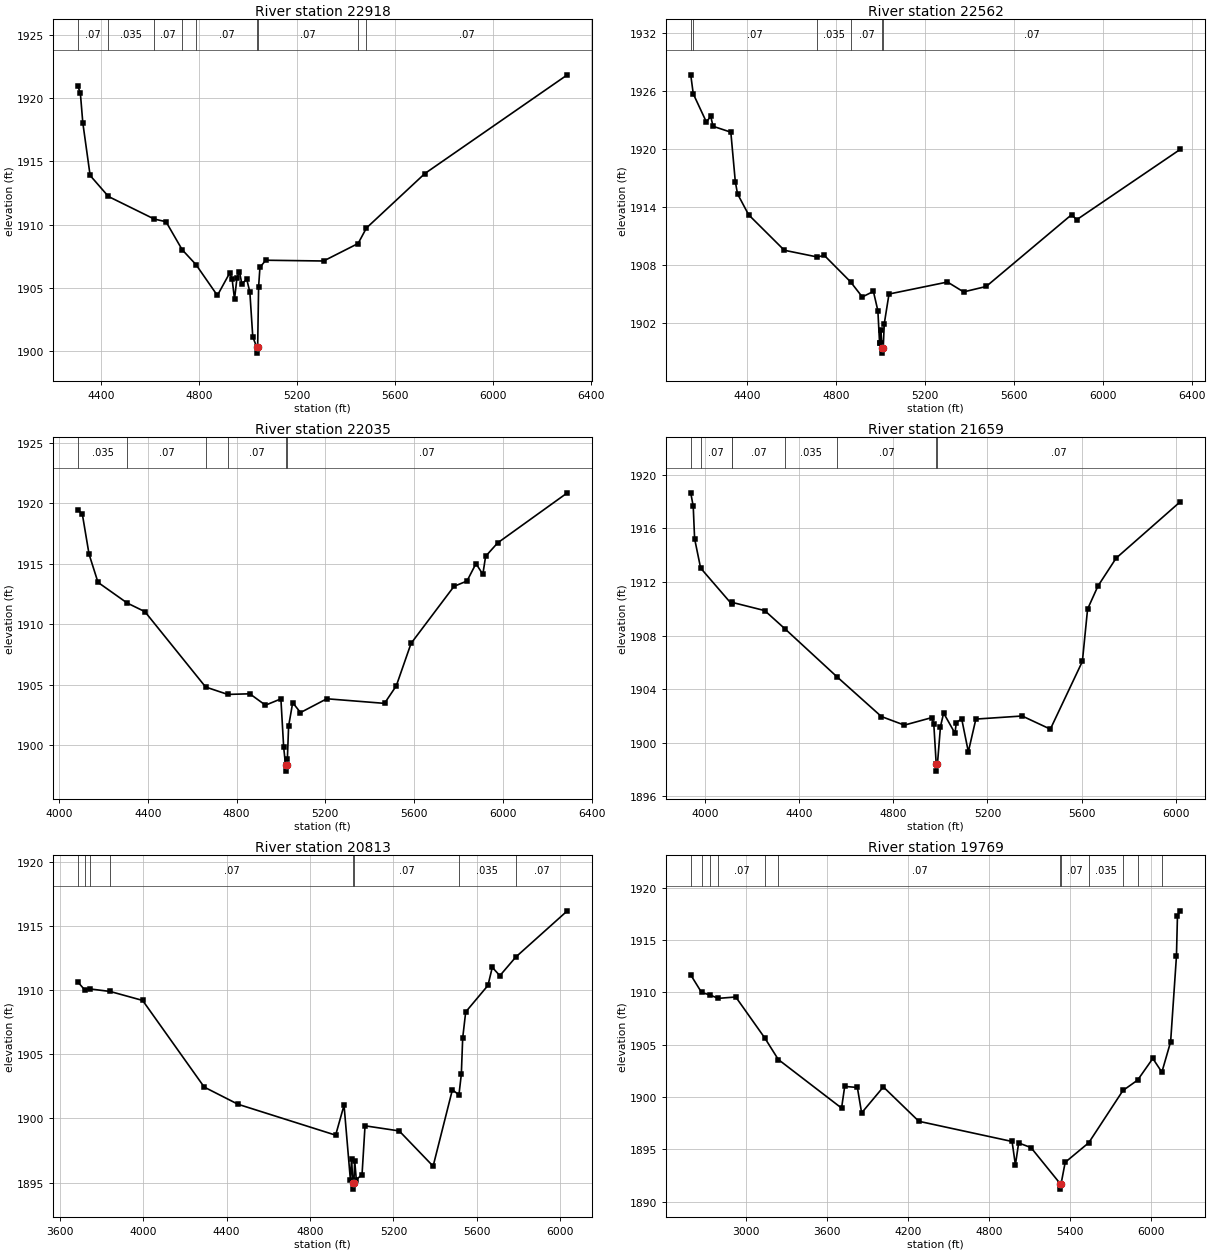
Type RM Length L Ch R = 1,22918,356,356,356
BEGIN DESCRIPTION:
South Fork 34.0
END DESCRIPTION:
XS GIS Cut Line= 3
      1436105.02      6896088.00      1436805.00      6896088.00
      1438005.02      6895587.99
#Sta/Elev= 30
  4304.8 1920.90  4314.8 1920.40  4324.8 1918.05  4354.8 1913.88  4429.6 1912.22
  4616.8 1910.44  4664.8 1910.23  4730.9 1908.02  4787.5 1906.84  4874.8 1904.41
  4924.8 1906.17  4934.8 1905.74  4944.8 1904.11  4954.8 1905.80  4964.8 1906.29
  4974.8 1905.33  4994.8 1905.69  5007.5 1904.67  5019.4 1901.14  5035.2 1900.36
  5035.4 1899.86  5039.4 1900.36  5043.2 1905.08  5048.7 1906.63  5072.5 1907.19
  5308.7 1907.13  5449.8 1908.51  5483.7 1909.73  5722.5 1914.03  6304.8 1921.82
#Mann=9,-1,0
  4304.8    0.07       0  4429.6   0.035       0  4616.8    0.07       0
  4730.9   0.035       0  4787.5    0.07       0  5035.2    0.07       0
  5039.4    0.07       0  5449.8   0.035       0  5483.7    0.07       0
Bank Sta=5035.2,5039.4
Exp/Cntr=0.3,0.1

Type RM Length L Ch R = 1,22562,527,527,527
BEGIN DESCRIPTION:
South Fork 33.0
END DESCRIPTION:
XS GIS Cut Line= 3
      1435955.02      6896488.00      1436805.44      6896443.18
      1437954.98      6895738.01
#Sta/Elev= 30
  4148.4 1927.66  4159.7 1925.70  4218.5 1922.80  4238.4 1923.37  4248.5 1922.35
  4328.6 1921.74  4348.7 1916.64  4358.7 1915.37  4408.7 1913.21  4569.0 1909.55
  4716.3 1908.86  4749.2 1909.01  4866.8 1906.29  4919.5 1904.73  4969.5 1905.30
  4989.6 1903.31  4997.3 1899.94  5000.0 1899.94  5002.9 1901.31  5008.8 1899.43
  5009.2 1898.93  5013.6 1899.43  5018.3 1901.96  5039.6 1905.03  5302.5 1906.27
  5374.9 1905.25  5476.5 1905.81  5861.4 1913.24  5882.6 1912.69  6348.6 1919.96
#Mann=6,-1,0
  4148.4   0.035       0  4159.7    0.07       0  4716.3   0.035       0
  4866.8    0.07       0  5008.8    0.07       0  5013.6    0.07       0
Bank Sta=5008.8,5013.6
Exp/Cntr=0.3,0.1

Type RM Length L Ch R = 1,22035,376,376,376
BEGIN DESCRIPTION:
South Fork 32.0
END DESCRIPTION:
XS GIS Cut Line= 3
      1436104.96      6896838.00      1437005.00      6896738.00
      1438205.02      6896237.99
#Sta/Elev= 30
  4085.2 1919.48  4105.4 1919.08  4135.5 1915.79  4175.8 1913.46  4307.6 1911.75
  4387.1 1911.04  4660.9 1904.81  4760.5 1904.20  4860.0 1904.25  4930.4 1903.31
  5000.0 1903.83  5012.4 1899.86  5020.9 1898.36  5021.2 1897.86  5025.7 1898.36
  5029.2 1898.88  5034.7 1901.57  5053.1 1903.52  5088.3 1902.70  5206.9 1903.84
  5466.9 1903.46  5520.0 1904.91  5586.6 1908.42  5780.0 1913.13  5838.5 1913.57
  5879.1 1915.01  5910.0 1914.12  5922.4 1915.61  5976.6 1916.72  6290.8 1920.86
#Mann=6,-1,0
  4085.2   0.035       0  4307.6    0.07       0  4660.9   0.035       0
  4760.5    0.07       0  5020.9    0.07       0  5025.7    0.07       0
Bank Sta=5020.9,5025.7
Exp/Cntr=0.3,0.1

Type RM Length L Ch R = 1,21659,846,846,846
BEGIN DESCRIPTION:
Mapping XS 10f85ac7
END DESCRIPTION:
XS GIS Cut Line= 4
      1436164.49      6896980.39      1437036.85      6897114.94
      1437201.78      6897015.11      1438111.62      6896590.52
#Sta/Elev= 30
  3939.4 1918.64  3950.0 1917.63  3955.8 1915.22  3981.4 1913.03  4112.7 1910.36
  4115.6 1910.47  4253.6 1909.86  4341.6 1908.47  4559.7 1904.94  4749.4 1901.96
  4847.1 1901.32  4963.5 1901.88  4971.9 1901.44  4982.4 1898.39  4982.8 1897.89
  4987.4 1898.39  5000.4 1901.21  5013.8 1902.22  5062.1 1900.71  5067.6 1901.51
  5090.5 1901.79  5118.8 1899.33  5150.8 1901.77  5347.4 1902.00  5467.2 1901.02
  5603.3 1906.07  5625.4 1909.97  5669.5 1911.69  5746.7 1913.77  6018.9 1917.97
#Mann=8,-1,0
  3939.4   0.035       0  3981.4    0.07       0  4112.7   0.035       0
  4115.6    0.07       0  4341.6   0.035       0  4559.7    0.07       0
  4982.4    0.07       0  4987.4    0.07       0
Bank Sta=4982.4,4987.4
Exp/Cntr=0.3,0.1

Type RM Length L Ch R = 1,20813,1044,1044,1044
BEGIN DESCRIPTION:
South Fork 31.0
END DESCRIPTION:
XS GIS Cut Line= 4
      1436251.27      6897180.04      1437334.31      6897660.98
      1437461.65      6897644.69      1438124.95      6896851.60
#Sta/Elev= 30
  3686.6 1910.64  3719.2 1910.04  3742.9 1910.11  3841.0 1909.91  3997.0 1909.21
  4292.5 1902.45  4454.4 1901.11  4922.7 1898.70  4963.0 1901.04  4993.3 1895.24
  4999.2 1896.85  5005.1 1894.99  5005.5 1894.49  5010.2 1894.99  5014.1 1896.70
  5021.8 1895.23  5049.3 1895.62  5063.6 1899.43  5227.5 1899.03  5390.2 1896.28
  5482.6 1902.24  5514.0 1901.84  5525.5 1903.46  5532.0 1906.28  5546.4 1908.31
  5653.1 1910.38  5673.9 1911.79  5710.3 1911.14  5787.0 1912.60  6033.9 1916.20
#Mann=8,-1,0
  3686.6   0.035       0  3719.2    0.07       0  3742.9   0.035       0
  3841.0    0.07       0  5005.1    0.07       0  5010.2    0.07       0
  5514.0   0.035       0  5787.0    0.07       0
Bank Sta=5005.1,5010.2
Exp/Cntr=0.3,0.1

Type RM Length L Ch R = 1,19769,452,452,452
BEGIN DESCRIPTION:
South Fork 28.0
END DESCRIPTION:
XS GIS Cut Line= 4
      1436187.88      6897168.25      1438176.45      6898316.55
      1438255.00      6898238.00      1438454.99      6897038.03
#Sta/Elev= 30
  2592.3 1911.67  2672.6 1909.99  2735.7 1909.75  2795.1 1909.43  2925.7 1909.56
  3140.9 1905.64  3240.6 1903.59  3709.1 1898.95  3732.2 1901.02  3826.0 1900.92
  3857.5 1898.49  4018.4 1900.97  4281.1 1897.69  4971.4 1895.76  4996.1 1893.52
  5020.0 1895.62  5111.2 1895.18  5329.1 1891.71  5329.5 1891.21  5334.2 1891.71
  5364.6 1893.77  5539.1 1895.64  5792.4 1900.63  5900.8 1901.62  6013.5 1903.69
  6080.5 1902.38  6145.3 1905.28  6188.4 1913.44  6196.0 1917.34  6216.2 1917.79
#Mann=12,-1,0
  2592.3   0.035       0  2672.6    0.07       0  2735.7   0.035       0
  2795.1    0.07       0  3140.9   0.035       0  3240.6    0.07       0
  5329.1    0.07       0  5334.2    0.07       0  5539.1   0.035       0
  5792.4    0.07       0  5900.8   0.035       0  6080.5    0.07       0
Bank Sta=5329.1,5334.2
Exp/Cntr=0.3,0.1

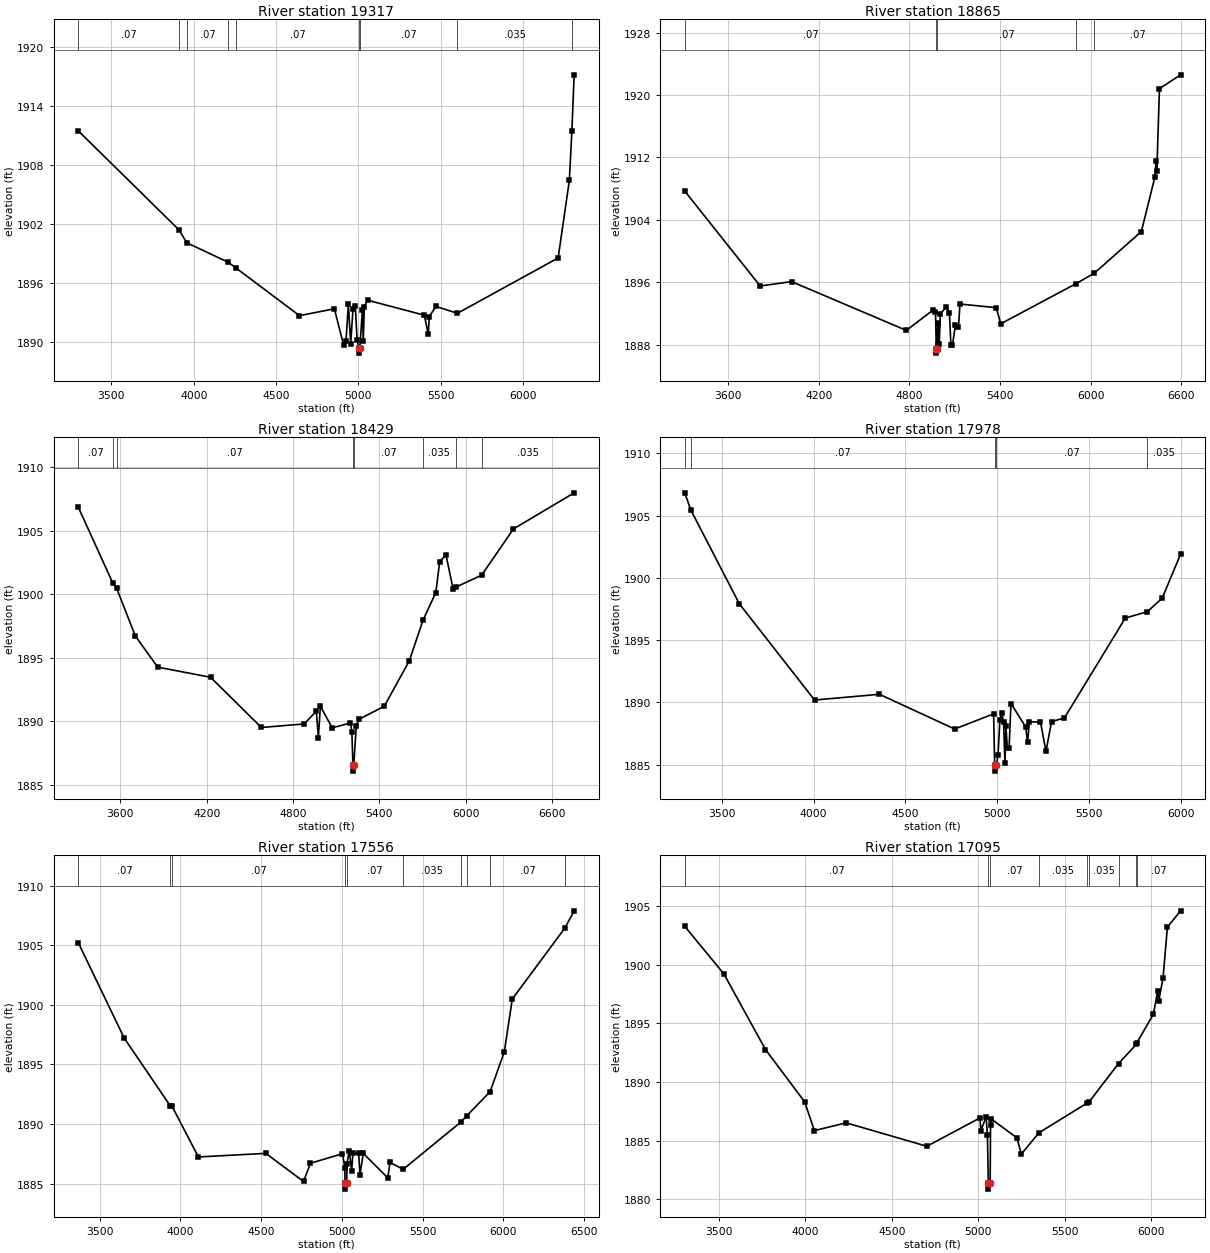
Type RM Length L Ch R = 1,19317,452,452,452
BEGIN DESCRIPTION:
South Fork 27.0
END DESCRIPTION:
XS GIS Cut Line= 3
      1437255.01      6899787.99      1438455.00      6898588.00
      1438654.99      6897288.04
#Sta/Elev= 30
  3299.0 1911.42  3908.2 1901.39  3959.0 1900.03  4206.2 1898.09  4259.9 1897.44
  4642.5 1892.63  4854.6 1893.33  4911.2 1889.61  4925.3 1890.08  4939.5 1893.82
  4953.6 1889.76  4967.8 1893.32  4981.9 1893.60  4992.5 1890.17  5003.2 1889.32
  5003.7 1888.82  5009.2 1889.32  5025.1 1893.25  5030.2 1890.06  5036.5 1893.55
  5056.7 1894.20  5400.7 1892.68  5424.8 1890.75  5431.1 1892.54  5471.6 1893.57
  5602.4 1892.87  6214.0 1898.50  6282.2 1906.39  6297.6 1911.45  6311.3 1917.12
#Mann=9,-1,0
  3299.0    0.07       0  3908.2   0.035       0  3959.0    0.07       0
  4206.2   0.035       0  4259.9    0.07       0  5003.2    0.07       0
  5009.2    0.07       0  5602.4   0.035       0  6297.6    0.07       0
Bank Sta=5003.2,5009.2
Exp/Cntr=0.3,0.1

Type RM Length L Ch R = 1,18865,436,436,436
BEGIN DESCRIPTION:
South Fork 26.0
END DESCRIPTION:
XS GIS Cut Line= 3
      1437870.19      6900001.21      1438855.00      6898638.00
      1438905.00      6897038.00
#Sta/Elev= 30
  3313.6 1907.68  3812.8 1895.53  4020.7 1896.09  4780.6 1889.84  4958.6 1892.47
  4973.3 1892.23  4978.8 1887.43  4979.3 1886.93  4984.8 1887.43  4988.0 1890.76
  4992.2 1888.04  4997.8 1888.04  5005.3 1891.93  5045.3 1892.87  5065.4 1892.09
  5075.4 1888.03  5085.4 1887.93  5105.4 1890.54  5125.4 1890.28  5135.4 1893.22
  5375.5 1892.75  5405.5 1890.69  5903.8 1895.83  6024.6 1897.17  6336.0 1902.50
  6426.0 1909.50  6433.5 1911.58  6438.5 1910.23  6456.0 1920.82  6596.1 1922.58
#Mann=5,-1,0
  3313.6    0.07       0  4978.8    0.07       0  4984.8    0.07       0
  5903.8   0.035       0  6024.6    0.07       0
Bank Sta=4978.8,4984.8
Exp/Cntr=0.3,0.1

Type RM Length L Ch R = 1,18429,451,451,451
BEGIN DESCRIPTION:
South Fork 25.0
END DESCRIPTION:
XS GIS Cut Line= 3
      1438005.01      6900037.99      1439205.00      6898838.00
      1439580.13      6897128.52
#Sta/Elev= 30
  3307.9 1906.86  3545.8 1900.93  3574.5 1900.47  3703.9 1896.72  3859.4 1894.26
  4227.1 1893.46  4580.7 1889.50  4877.7 1889.78  4962.5 1890.78  4976.7 1888.71
  4990.8 1891.18  5073.2 1889.47  5199.5 1889.86  5209.7 1889.15  5216.9 1886.56
  5217.4 1886.06  5223.0 1886.56  5240.4 1889.63  5258.7 1890.15  5434.9 1891.17
  5609.0 1894.76  5703.8 1897.94  5793.3 1900.14  5820.1 1902.57  5863.9 1903.11
  5912.9 1900.45  5931.2 1900.56  6112.0 1901.51  6332.7 1905.15  6755.1 1908.00
#Mann=8,-1,0
  3307.9    0.07       0  3545.8    0.16       0  3574.5    0.07       0
  5216.9    0.07       0  5223.0    0.07       0  5703.8   0.035       0
  5931.2    0.07       0  6112.0   0.035       0
Bank Sta=5216.9,5223
Exp/Cntr=0.3,0.1

Type RM Length L Ch R = 1,17978,422,422,422
BEGIN DESCRIPTION:
South Fork 24.0
END DESCRIPTION:
XS GIS Cut Line= 3
      1438354.98      6900238.02      1439555.00      6899038.00
      1439455.00      6898037.98
#Sta/Elev= 30
  3298.4 1906.83  3330.2 1905.48  3595.4 1897.92  4005.5 1890.19  4359.1 1890.65
  4769.2 1887.86  4981.3 1889.08  4987.0 1884.98  4987.5 1884.48  4996.9 1884.98
  5005.5 1885.81  5015.6 1888.61  5025.6 1889.13  5035.7 1888.41  5043.2 1885.10
  5048.3 1888.12  5055.8 1886.37  5065.8 1886.37  5075.9 1889.91  5156.3 1888.02
  5166.3 1886.80  5176.4 1888.45  5236.7 1888.42  5266.8 1886.07  5297.0 1888.46
  5367.3 1888.75  5699.0 1896.77  5819.5 1897.29  5900.0 1898.37  6000.5 1901.91
#Mann=5,-1,0
  3298.4   0.035       0  3330.2    0.07       0  4987.0    0.07       0
  4996.9    0.07       0  5819.5   0.035       0
Bank Sta=4987,4996.9
Exp/Cntr=0.3,0.1

Type RM Length L Ch R = 1,17556,461,461,461
BEGIN DESCRIPTION:
South Fork 23.0
END DESCRIPTION:
XS GIS Cut Line= 3
      1438805.01      6900337.99      1439905.00      6899138.00
      1440705.00      6897937.99
#Sta/Elev= 30
  3367.7 1905.21  3651.0 1897.23  3937.3 1891.52  3947.6 1891.50  4111.0 1887.24
  4528.5 1887.54  4762.2 1885.18  4804.7 1886.71  5003.1 1887.51  5018.1 1886.33
  5018.9 1885.04  5019.4 1884.54  5029.3 1885.04  5031.6 1886.66  5045.1 1887.78
  5060.2 1886.08  5067.7 1887.53  5103.7 1887.53  5111.2 1885.75  5132.3 1887.54
  5284.0 1885.48  5297.5 1886.78  5378.9 1886.20  5737.5 1890.18  5772.4 1890.69
  5917.1 1892.71  6005.1 1896.05  6054.7 1900.49  6379.5 1906.43  6437.8 1907.89
#Mann=10,-1,0
  3367.7    0.07       0  3937.3   0.035       0  3947.6    0.07       0
  5018.9    0.07       0  5029.3    0.07       0  5378.9   0.035       0
  5737.5    0.07       0  5772.4   0.035       0  5917.1    0.07       0
  6379.5   0.035       0
Bank Sta=5018.9,5029.3
Exp/Cntr=0.3,0.1

Type RM Length L Ch R = 1,17095,418,418,418
BEGIN DESCRIPTION:
South Fork 22.0
END DESCRIPTION:
XS GIS Cut Line= 3
      1439105.03      6900437.97      1440305.00      6899238.00
      1440705.00      6898137.99
#Sta/Elev= 30
  3302.6 1903.29  3528.8 1899.23  3769.3 1892.77  3995.5 1888.31  4052.1 1885.85
  4235.9 1886.51  4702.6 1884.51  5009.6 1886.93  5014.9 1885.85  5045.5 1887.03
  5052.8 1885.46  5058.2 1881.35  5058.7 1880.85  5068.7 1881.35  5070.8 1886.31
  5076.1 1886.83  5223.7 1885.22  5249.0 1883.84  5351.2 1885.67  5628.1 1888.19
  5640.8 1888.30  5811.0 1891.58  5914.2 1893.22  5916.7 1893.34  6012.5 1895.79
  6037.7 1897.79  6043.1 1896.89  6068.3 1898.86  6093.6 1903.23  6170.1 1904.62
#Mann=9,-1,0
  3302.6    0.07       0  5058.2    0.07       0  5068.7    0.07       0
  5351.2   0.035       0  5628.1    0.07       0  5640.8   0.035       0
  5811.0    0.07       0  5914.2   0.035       0  5916.7    0.07       0
Bank Sta=5058.2,5068.7
Exp/Cntr=0.3,0.1

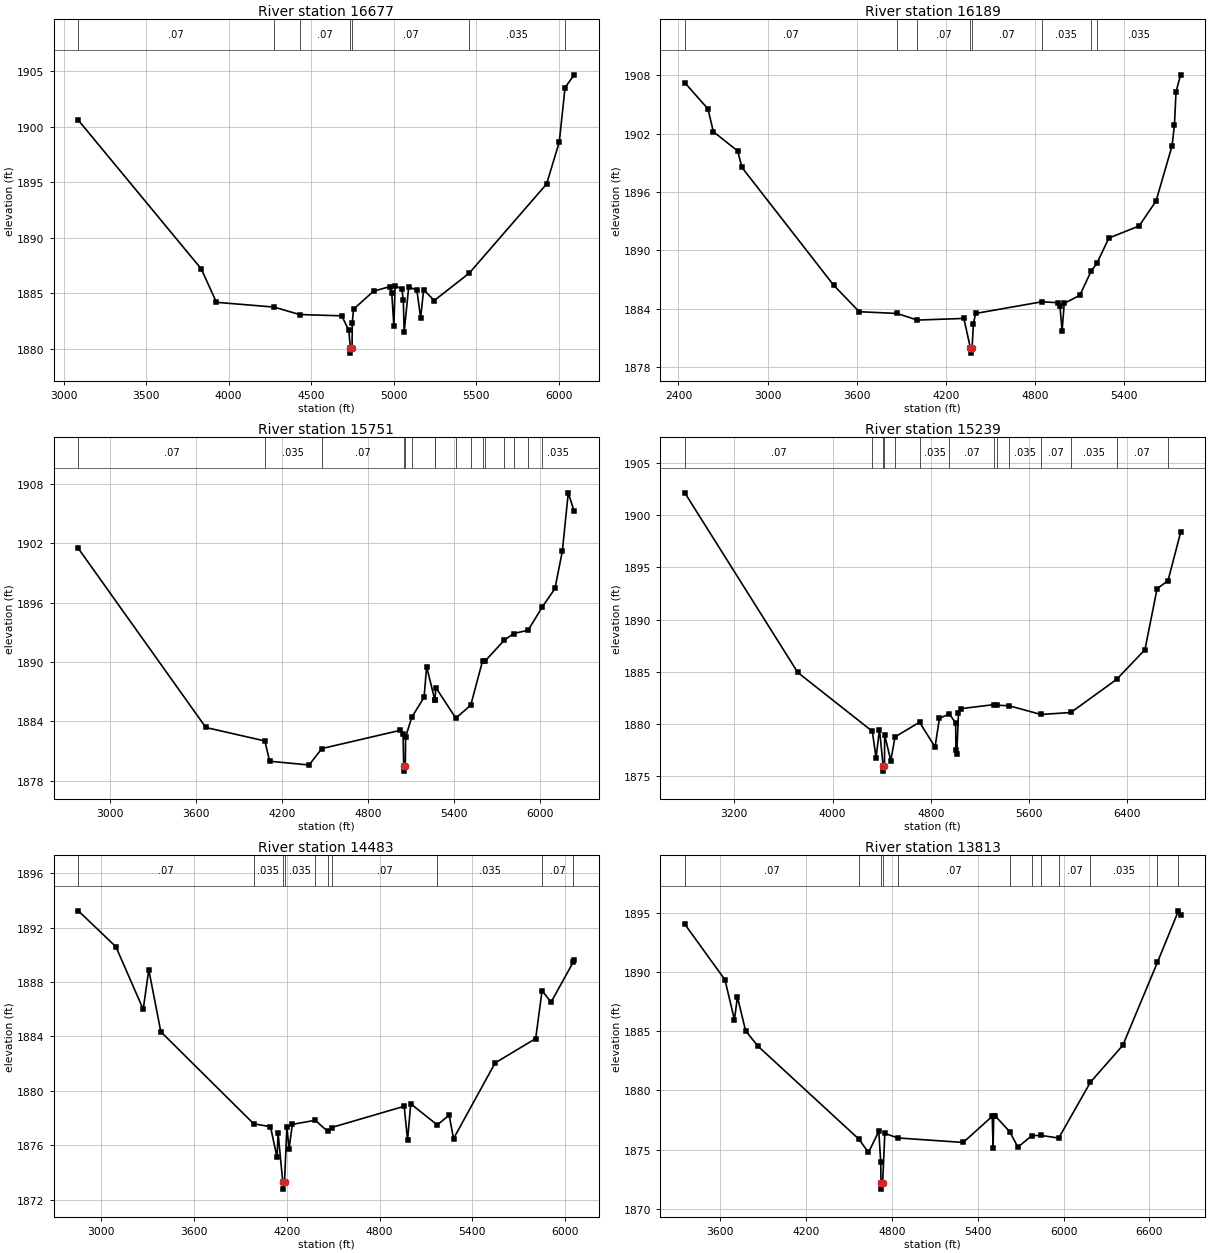
Type RM Length L Ch R = 1,16677,488,488,488
BEGIN DESCRIPTION:
South Fork 21.0
END DESCRIPTION:
XS GIS Cut Line= 4
      1439555.03      6900787.97      1440648.18      6899489.07
      1440664.68      6899277.19      1440932.03      6898215.64
#Sta/Elev= 30
  3089.8 1900.60  3834.8 1887.20  3926.7 1884.19  4275.5 1883.76  4430.3 1883.09
  4686.2 1882.97  4729.1 1881.66  4738.2 1880.11  4738.7 1879.61  4748.7 1880.11
  4750.0 1882.37  4757.7 1883.57  4878.8 1885.19  4979.1 1885.61  4989.2 1885.03
  5002.2 1882.03  5009.5 1885.68  5050.7 1885.39  5059.3 1884.36  5064.5 1881.53
  5092.0 1885.56  5141.5 1885.30  5164.2 1882.78  5182.6 1885.33  5246.7 1884.35
  5459.2 1886.82  5927.5 1894.85  6004.5 1898.63  6039.5 1903.54  6094.7 1904.69
#Mann=7,-1,0
  3089.8    0.07       0  4275.5   0.035       0  4430.3    0.07       0
  4738.2    0.07       0  4748.7    0.07       0  5459.2   0.035       0
  6039.5    0.07       0
Bank Sta=4738.2,4748.7
Exp/Cntr=0.3,0.1

Type RM Length L Ch R = 1,16189,438,438,438
BEGIN DESCRIPTION:
South Fork 20.0
END DESCRIPTION:
XS GIS Cut Line= 3
      1439454.98      6901088.03      1441055.00      6899088.00
      1441255.00      6898337.99
#Sta/Elev= 30
  2442.7 1907.24  2598.8 1904.54  2634.8 1902.20  2798.9 1900.21  2826.9 1898.53
  3445.6 1886.39  3616.9 1883.68  3872.5 1883.50  4007.3 1882.82  4321.2 1882.99
  4365.4 1879.92  4365.9 1879.42  4376.3 1879.92  4385.3 1882.41  4399.7 1883.50
  4845.3 1884.70  4953.6 1884.61  4968.0 1884.24  4982.4 1881.71  4996.8 1884.54
  5101.7 1885.37  5177.2 1887.83  5217.6 1888.69  5297.0 1891.26  5500.8 1892.50
  5614.6 1895.06  5722.6 1900.75  5738.8 1902.92  5749.1 1906.30  5780.2 1908.05
#Mann=8,-1,0
  2442.7    0.07       0  3872.5   0.035       0  4007.3    0.07       0
  4365.4   0.035       0  4376.3    0.07       0  4845.3   0.035       0
  5177.2    0.07       0  5217.6   0.035       0
Bank Sta=4365.4,4376.3
Exp/Cntr=0.3,0.1

Type RM Length L Ch R = 1,15751,512,512,512
BEGIN DESCRIPTION:
South Fork 19.0
END DESCRIPTION:
XS GIS Cut Line= 3
      1439655.00      6900938.00      1441255.00      6899388.00
      1441555.00      6898188.00
#Sta/Elev= 30
  2776.5 1901.48  3667.6 1883.38  4079.9 1882.02  4113.1 1879.97  4389.0 1879.59
  4478.2 1881.25  5027.4 1883.10  5045.4 1882.76  5050.2 1879.47  5050.7 1878.97
  5061.2 1879.47  5063.4 1882.42  5106.0 1884.40  5192.3 1886.43  5210.3 1889.53
  5267.8 1886.14  5268.2 1886.13  5274.7 1887.41  5414.3 1884.32  5518.6 1885.64
  5601.5 1890.13  5618.8 1890.10  5753.2 1892.21  5819.2 1892.88  5919.4 1893.21
  6019.7 1895.59  6107.1 1897.43  6158.6 1901.21  6199.9 1907.10  6241.1 1905.22
#Mann=16,-1,0
  2776.5    0.07       0  4079.9   0.035       0  4478.2    0.07       0
  5050.2    0.07       0  5061.2    0.07       0  5106.0   0.035       0
  5267.8    0.07       0  5268.2   0.035       0  5414.3    0.07       0
  5518.6   0.035       0  5601.5    0.07       0  5618.8   0.035       0
  5753.2    0.07       0  5819.2   0.035       0  5919.4    0.07       0
  6019.7   0.035       0
Bank Sta=5050.2,5061.2
Exp/Cntr=0.3,0.1

Type RM Length L Ch R = 1,15239,756,756,756
BEGIN DESCRIPTION:
South Fork 18.0
END DESCRIPTION:
XS GIS Cut Line= 3
      1439804.98      6901288.02      1441416.38      6899785.97
      1442805.03      6898587.97
#Sta/Elev= 30
  2797.1 1902.13  3716.8 1884.94  4324.0 1879.31  4353.9 1876.79  4382.2 1879.48
  4411.9 1876.00  4412.4 1875.50  4422.9 1876.00  4424.2 1878.97  4474.1 1876.51
  4509.2 1878.78  4708.4 1880.18  4834.6 1877.80  4870.3 1880.56  4951.7 1880.97
  5002.3 1880.10  5004.7 1877.51  5011.4 1877.12  5025.5 1881.07  5047.4 1881.48
  5318.2 1881.87  5342.1 1881.80  5436.0 1881.76  5696.8 1880.92  5940.2 1881.11
  6312.0 1884.27  6543.4 1887.12  6642.5 1892.96  6731.3 1893.72  6834.0 1898.35
#Mann=14,-1,0
  2797.1    0.07       0  4324.0   0.035       0  4411.9    0.07       0
  4422.9   0.035       0  4509.2    0.07       0  4708.4   0.035       0
  4951.7    0.07       0  5318.2   0.035       0  5342.1    0.07       0
  5436.0   0.035       0  5696.8    0.07       0  5940.2   0.035       0
  6312.0    0.07       0  6731.3   0.035       0
Bank Sta=4411.9,4422.9
Exp/Cntr=0.3,0.1

Type RM Length L Ch R = 1,14483,670,670,670
BEGIN DESCRIPTION:
Mapping XS a7698935
END DESCRIPTION:
XS GIS Cut Line= 3
      1440342.18      6901357.37      1441953.14      6899927.11
      1442724.92      6899216.58
#Sta/Elev= 30
  2854.3 1893.23  3097.0 1890.59  3273.4 1885.99  3309.4 1888.90  3387.2 1884.34
  3987.5 1877.57  4095.5 1877.36  4138.1 1875.10  4144.8 1876.90  4175.3 1873.27
  4175.8 1872.77  4186.3 1873.27  4201.7 1877.36  4215.9 1875.73  4236.8 1877.53
  4384.3 1877.83  4464.1 1877.03  4490.4 1877.30  4959.4 1878.86  4981.1 1876.39
  5002.0 1879.04  5173.5 1877.49  5249.9 1878.21  5278.3 1876.48  5547.1 1882.05
  5809.1 1883.84  5850.3 1887.37  5908.2 1886.51  6053.1 1889.49  6057.6 1889.59
#Mann=10,-1,0
  2854.3    0.07       0  3987.5   0.035       0  4175.3    0.07       0
  4186.3   0.035       0  4384.3    0.07       0  4464.1   0.035       0
  4490.4    0.07       0  5173.5   0.035       0  5850.3    0.07       0
  6053.1   0.035       0
Bank Sta=4175.3,4186.3
Exp/Cntr=0.3,0.1

Type RM Length L Ch R = 1,13813,1113,1113,1113
BEGIN DESCRIPTION:
South Fork 16.0
END DESCRIPTION:
XS GIS Cut Line= 3
      1440454.98      6901488.01      1442255.00      6900288.00
      1442955.00      6899187.99
#Sta/Elev= 30
  3351.0 1894.07  3632.0 1889.36  3698.1 1885.98  3719.1 1887.91  3776.2 1885.05
  3863.3 1883.74  4568.2 1875.88  4635.5 1874.75  4707.6 1876.54  4721.1 1873.93
  4723.0 1872.15  4723.5 1871.65  4734.3 1872.15  4749.7 1876.36  4841.6 1875.98
  5298.0 1875.60  5500.8 1877.81  5506.8 1875.17  5511.3 1877.80  5522.0 1877.84
  5623.0 1876.51  5680.3 1875.20  5777.6 1876.18  5845.3 1876.19  5965.8 1875.97
  6187.6 1880.70  6413.5 1883.81  6656.0 1890.84  6803.0 1895.20  6818.2 1894.86
#Mann=12,-1,0
  3351.0    0.07       0  4568.2   0.035       0  4723.0    0.07       0
  4734.3   0.035       0  4841.6    0.07       0  5623.0   0.035       0
  5777.6    0.07       0  5845.3   0.035       0  5965.8    0.07       0
  6187.6   0.035       0  6656.0    0.07       0  6803.0   0.035       0
Bank Sta=4723,4734.3
Exp/Cntr=0.3,0.1

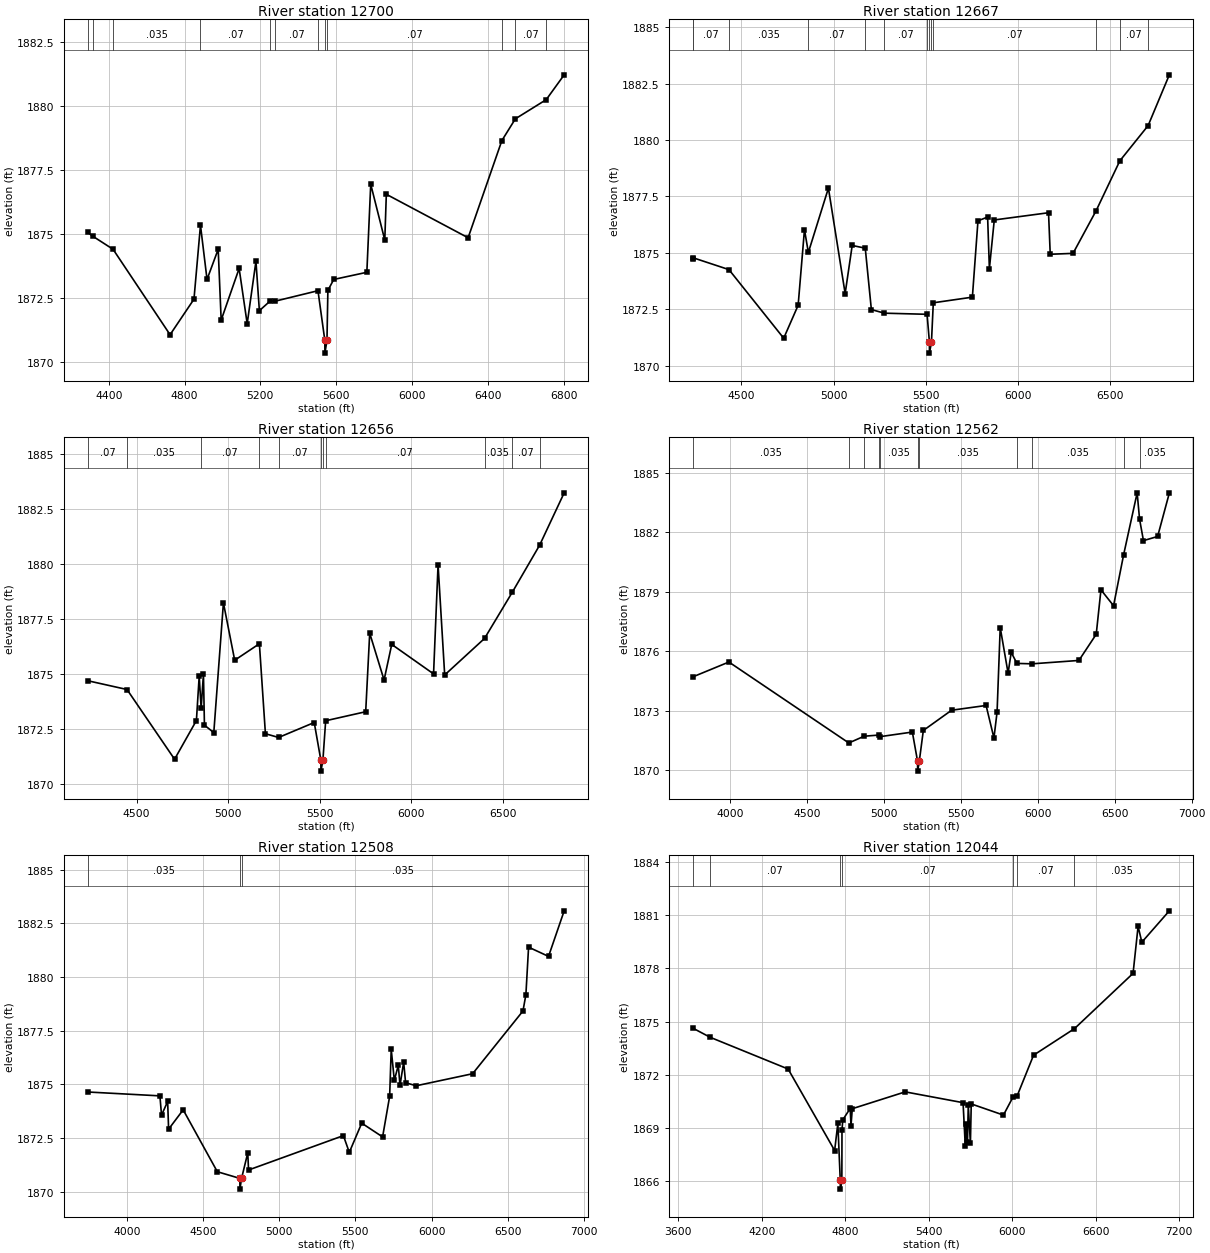
Type RM Length L Ch R = 1,12700,33,33,33
BEGIN DESCRIPTION:
Mapping XS 157fd63b
END DESCRIPTION:
XS GIS Cut Line= 6
      1441972.24      6901820.26      1442353.81      6901413.00
      1442474.88      6901438.69      1442485.89      6901394.66
      1442412.51      6901229.55      1442779.42      6899684.87
#Sta/Elev= 30
  4288.5 1875.07  4317.9 1874.91  4422.7 1874.41  4723.6 1871.07  4849.7 1872.46
  4884.0 1875.35  4918.6 1873.23  4977.5 1874.41  4993.2 1871.64  5088.0 1873.66
  5130.5 1871.50  5176.7 1873.94  5194.8 1872.01  5252.1 1872.39  5277.3 1872.38
  5504.0 1872.79  5540.2 1870.85  5540.7 1870.35  5551.5 1870.85  5556.3 1872.80
  5587.1 1873.23  5761.9 1873.51  5782.4 1876.95  5856.6 1874.77  5864.7 1876.56
  6296.3 1874.86  6474.4 1878.66  6545.6 1879.51  6708.5 1880.26  6803.2 1881.23
#Mann=12,-1,0
  4288.5   0.035       0  4317.9    0.07       0  4422.7   0.035       0
  4884.0    0.07       0  5252.1   0.035       0  5277.3    0.07       0
  5504.0   0.035       0  5540.2    0.07       0  5551.5    0.07       0
  6474.4   0.035       0  6545.6    0.07       0  6708.5   0.035       0
Bank Sta=5540.2,5551.5
Exp/Cntr=0.3,0.1

Type RM Length L Ch R = 1,12667,11,11,11
BEGIN DESCRIPTION:
Mapping XS d3929023
END DESCRIPTION:
XS GIS Cut Line= 6
      1441975.92      6901845.93      1442372.15      6901424.01
      1442500.57      6901457.03      1442518.91      6901402.00
      1442430.86      6901229.55      1442819.42      6899671.65
#Sta/Elev= 30
  4236.8 1874.75  4240.2 1874.78  4432.9 1874.26  4729.7 1871.22  4807.9 1872.68
  4842.2 1876.03  4863.3 1875.02  4972.0 1877.87  5062.7 1873.20  5100.9 1875.33
  5171.7 1875.21  5204.8 1872.49  5275.6 1872.33  5506.8 1872.28  5519.3 1871.06
  5519.8 1870.56  5530.6 1871.06  5540.5 1872.79  5752.3 1873.04  5782.6 1876.42
  5834.9 1876.59  5844.5 1874.30  5871.0 1876.46  6165.1 1876.78  6174.3 1874.94
  6297.9 1874.98  6423.0 1876.87  6551.6 1879.08  6704.8 1880.64  6819.8 1882.89
#Mann=13,-1,0
  4236.8   0.035       0  4240.2    0.07       0  4432.9   0.035       0
  4863.3    0.07       0  5171.7   0.035       0  5275.6    0.07       0
  5506.8   0.035       0  5519.3    0.07       0  5530.6   0.035       0
  5540.5    0.07       0  6423.0   0.035       0  6551.6    0.07       0
  6704.8   0.035       0
Bank Sta=5519.3,5530.6
Exp/Cntr=0.3,0.1

Type RM Length L Ch R = 1,12656,94,94,94
BEGIN DESCRIPTION:
Mapping XS c20a26d2
END DESCRIPTION:
XS GIS Cut Line= 6
      1441986.02      6901850.60      1442366.06      6901443.99
      1442461.74      6901494.48      1442522.87      6901433.35
      1442448.45      6901234.02      1442836.48      6899655.33
#Sta/Elev= 30
  4232.1 1874.71  4447.3 1874.31  4707.2 1871.14  4826.5 1872.90  4841.8 1874.92
  4852.4 1873.46  4865.0 1875.01  4870.4 1872.69  4921.5 1872.35  4974.1 1878.25
  5035.7 1875.64  5170.6 1876.39  5203.6 1872.30  5275.7 1872.13  5470.3 1872.81
  5506.4 1871.10  5506.9 1870.60  5517.7 1871.10  5532.8 1872.89  5751.5 1873.30
  5773.4 1876.87  5851.9 1874.74  5893.7 1876.36  6122.3 1875.02  6146.9 1879.98
  6183.1 1874.97  6400.7 1876.63  6552.4 1878.73  6701.8 1880.87  6836.0 1883.25
#Mann=11,-1,0
  4232.1    0.07       0  4447.3   0.035       0  4852.4    0.07       0
  5170.6   0.035       0  5275.7    0.07       0  5506.4    0.07       0
  5517.7    0.07       0  5532.8    0.07       0  6400.7   0.035       0
  6552.4    0.07       0  6701.8   0.035       0
Bank Sta=5506.4,5517.7
Exp/Cntr=0.3,0.1

Type RM Length L Ch R = 1,12562,54,54,54
BEGIN DESCRIPTION:
Mapping XS 8c4fd4ae
END DESCRIPTION:
XS GIS Cut Line= 3
      1442375.39      6902657.48      1442766.02      6900678.30
      1442991.71      6899623.64
#Sta/Elev= 30
  3759.0 1874.70  3993.7 1875.45  4772.8 1871.37  4872.0 1871.71  4971.3 1871.77
  4977.5 1871.69  5185.5 1871.92  5219.3 1870.45  5219.8 1869.95  5230.6 1870.45
  5256.8 1872.00  5440.4 1873.02  5664.5 1873.26  5715.5 1871.62  5735.9 1872.93
  5756.3 1877.19  5807.4 1874.89  5827.8 1875.94  5864.7 1875.38  5964.2 1875.36
  6267.5 1875.53  6380.0 1876.85  6410.7 1879.09  6492.5 1878.29  6558.3 1880.87
  6645.9 1883.98  6661.6 1882.65  6686.8 1881.57  6778.9 1881.78  6854.9 1883.97
#Mann=11,-1,0
  3759.0   0.035       0  4772.8    0.07       0  4872.0   0.035       0
  4971.3    0.07       0  4977.5   0.035       0  5219.3   0.035       0
  5230.6   0.035       0  5864.7    0.07       0  5964.2   0.035       0
  6558.3    0.07       0  6661.6   0.035       0
Bank Sta=5219.3,5230.6
Exp/Cntr=0.3,0.1

Type RM Length L Ch R = 1,12508,464,464,464
BEGIN DESCRIPTION:
Mapping XS 482b540c
END DESCRIPTION:
XS GIS Cut Line= 3
      1442427.48      6902683.52      1442822.44      6900669.62
      1443074.17      6899623.65
#Sta/Elev= 30
  3742.6 1874.65  4217.0 1874.47  4227.8 1873.57  4267.9 1874.21  4274.2 1872.92
  4369.8 1873.82  4594.0 1870.94  4741.8 1870.63  4742.3 1870.13  4753.1 1870.63
  4793.8 1871.82  4798.9 1871.02  5421.5 1872.62  5460.2 1871.84  5541.8 1873.20
  5678.8 1872.56  5725.1 1874.45  5735.4 1876.64  5755.8 1875.19  5781.7 1875.89
  5793.1 1874.96  5817.1 1876.04  5829.8 1875.08  5899.4 1874.94  6269.7 1875.50
  6600.2 1878.42  6619.4 1879.18  6637.0 1881.39  6768.0 1880.96  6870.7 1883.08
#Mann=3,-1,0
  3742.6   0.035       0  4741.8   0.035       0  4753.1   0.035       0
Bank Sta=4741.8,4753.1
Exp/Cntr=0.3,0.1

Type RM Length L Ch R = 1,12044,525,525,525
BEGIN DESCRIPTION:
South Fork 14.0
END DESCRIPTION:
XS GIS Cut Line= 3
      1442465.90      6902712.49      1443455.00      6900988.00
      1444251.59      6899791.77
#Sta/Elev= 30
  3705.1 1874.63  3830.5 1874.11  4390.4 1872.32  4724.8 1867.72  4747.8 1869.25
  4765.2 1866.04  4765.7 1865.54  4776.6 1866.04  4777.6 1868.88  4783.4 1869.45
  4836.6 1870.10  4842.3 1869.12  4851.6 1870.08  5232.0 1871.03  5647.8 1870.42
  5663.6 1868.00  5670.1 1869.20  5679.4 1868.19  5685.2 1870.27  5700.6 1868.12
  5706.6 1870.35  5938.0 1869.72  6007.5 1870.75  6035.8 1870.79  6154.4 1873.10
  6448.6 1874.60  6869.7 1877.72  6905.7 1880.37  6932.8 1879.48  7130.3 1881.25
#Mann=7,-1,0
  3705.1   0.035       0  3830.5    0.07       0  4765.2    0.07       0
  4776.6    0.07       0  6007.5   0.035       0  6035.8    0.07       0
  6448.6   0.035       0
Bank Sta=4765.2,4776.6
Exp/Cntr=0.3,0.1