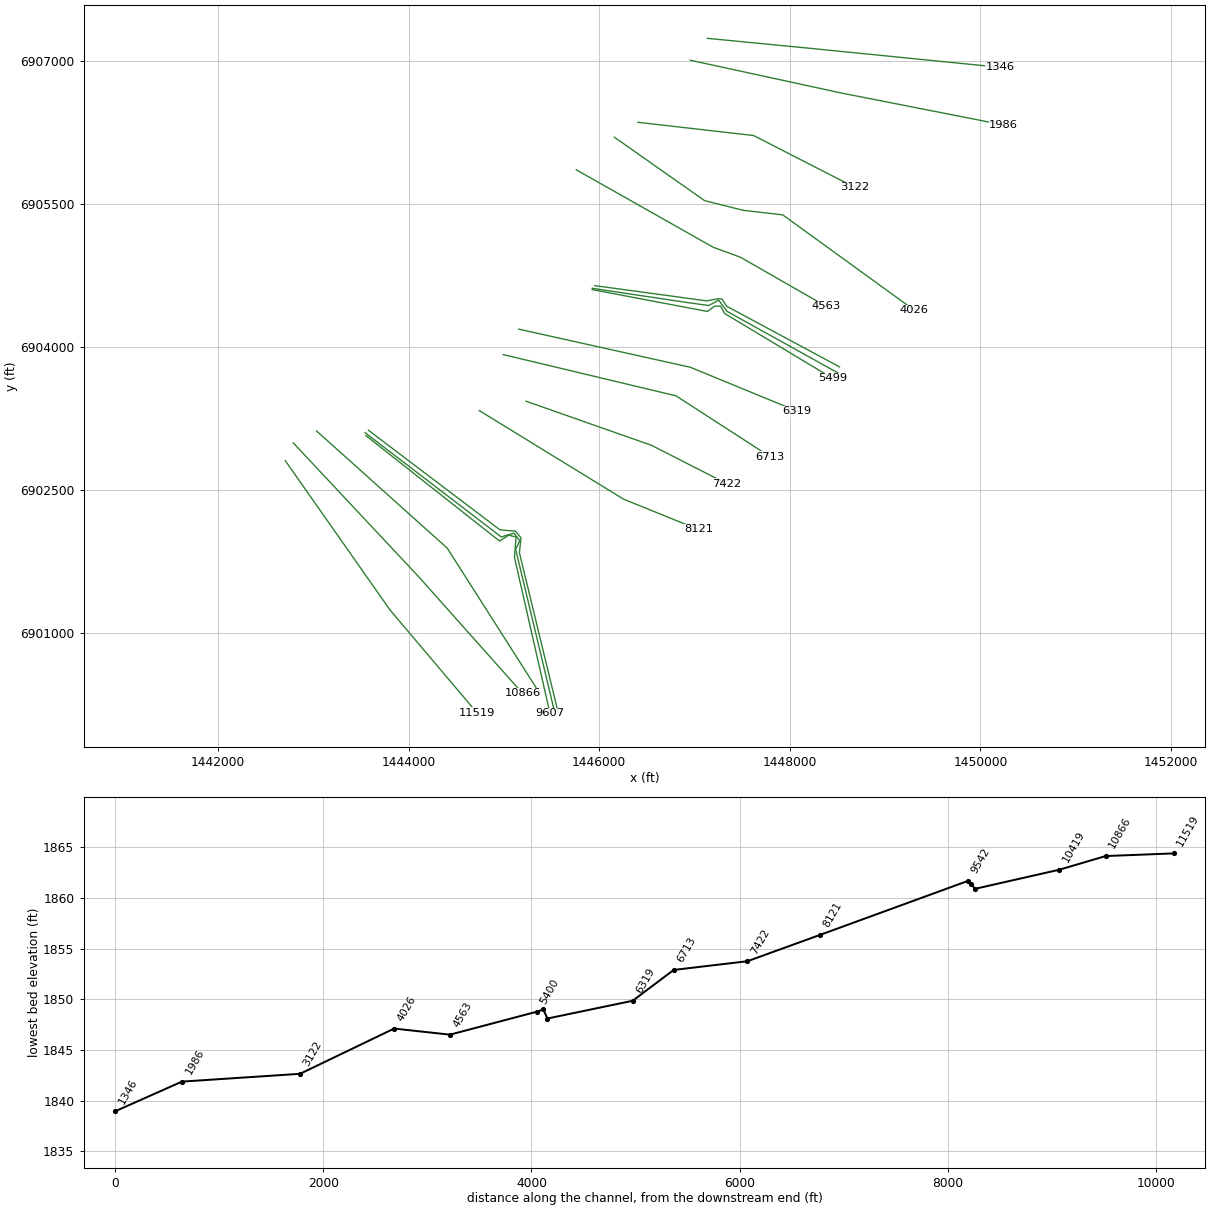
HEC-RAS study South Fork.prj: South Fork Base Level Engineering

--- South Fork.g01 (geometry) --- (continued)

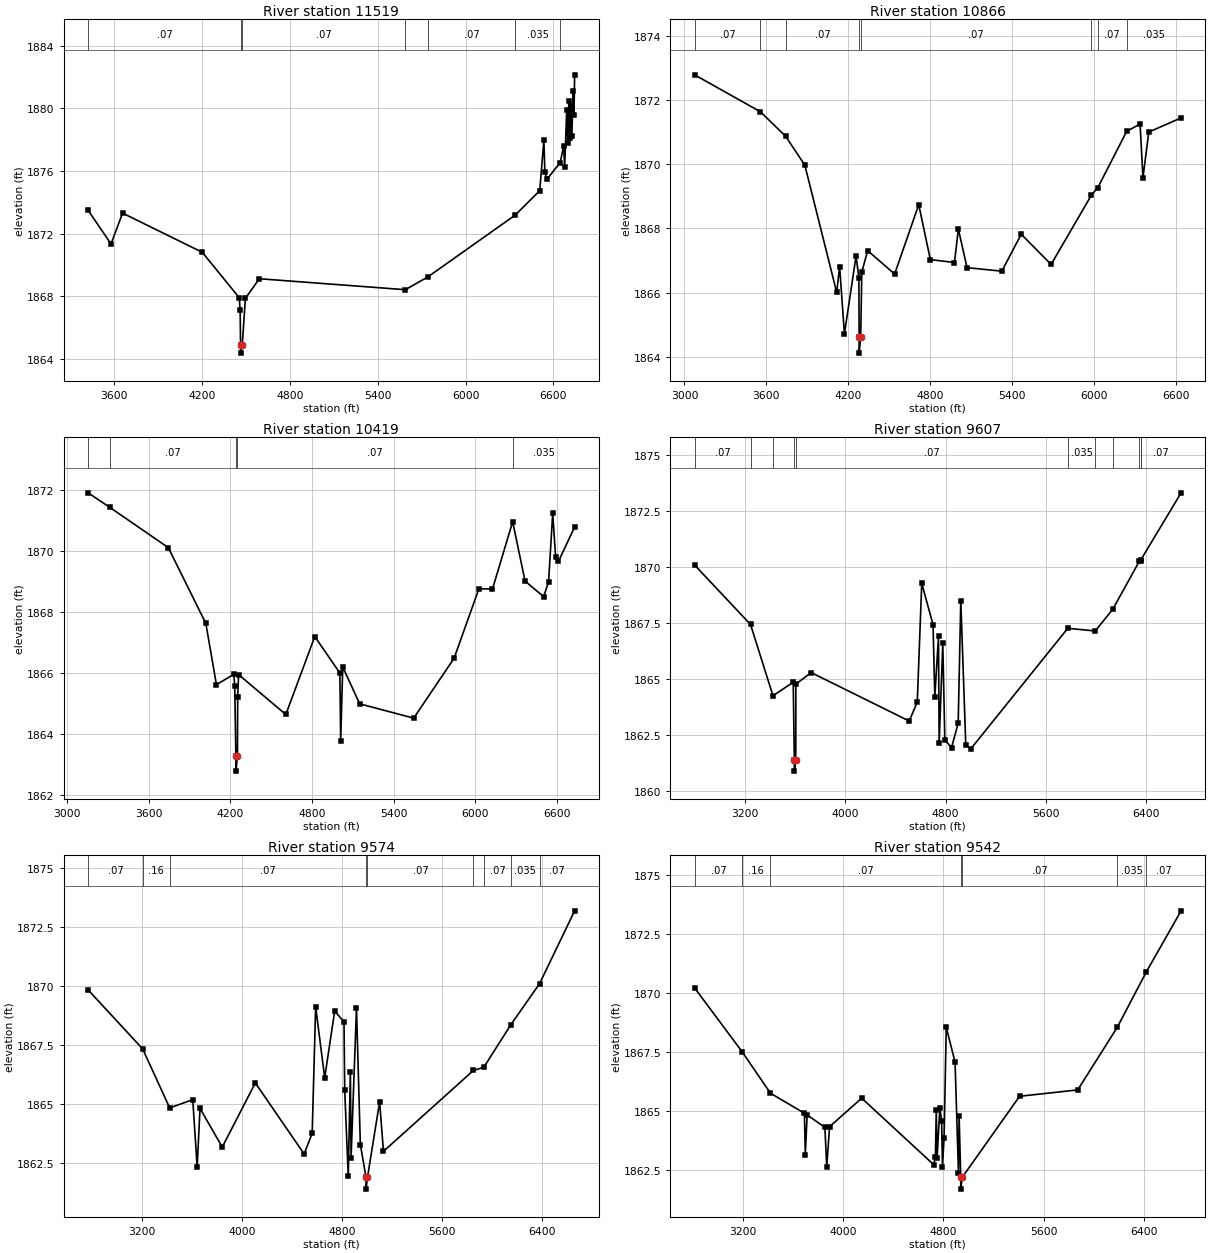
Type RM Length L Ch R = 1,11519,653,653,653
BEGIN DESCRIPTION:
South Fork 13.0
END DESCRIPTION:
XS GIS Cut Line= 3
      1442705.47      6902806.26      1443805.00      6901238.00
      1444714.79      6900161.72
#Sta/Elev= 30
  3420.5 1873.50  3577.1 1871.35  3655.7 1873.32  4200.5 1870.82  4453.2 1867.92
  4459.4 1867.13  4462.3 1864.88  4462.8 1864.38  4473.8 1864.88  4495.1 1867.87
  4590.1 1869.13  5588.6 1868.43  5742.8 1869.25  6338.5 1873.19  6506.5 1874.75
  6535.1 1877.98  6541.7 1875.95  6555.9 1875.48  6646.4 1876.55  6670.3 1877.60
  6676.8 1876.25  6691.1 1879.91  6697.7 1877.78  6705.4 1880.47  6712.0 1878.14
  6719.7 1880.13  6726.3 1878.25  6734.0 1881.10  6740.5 1879.58  6745.1 1882.15
#Mann=7,-1,0
  3420.5    0.07       0  4462.3    0.07       0  4473.8    0.07       0
  5588.6   0.035       0  5742.8    0.07       0  6338.5   0.035       0
  6646.4    0.07       0
Bank Sta=4462.3,4473.8
Exp/Cntr=0.3,0.1

Type RM Length L Ch R = 1,10866,447,447,447
BEGIN DESCRIPTION:
South Fork 12.0
END DESCRIPTION:
XS GIS Cut Line= 3
      1442788.77      6902993.79      1444105.00      6901588.00
      1445195.08      6900363.52
#Sta/Elev= 30
  3074.2 1872.78  3557.0 1871.63  3740.9 1870.87  3882.1 1869.97  4115.6 1866.01
  4137.0 1866.81  4172.3 1864.72  4257.3 1867.14  4278.3 1866.47  4279.8 1864.62
  4280.3 1864.12  4291.3 1864.62  4299.8 1866.64  4342.3 1867.31  4540.1 1866.58
  4716.9 1868.74  4801.9 1867.03  4978.7 1866.94  5007.1 1867.98  5070.7 1866.78
  5325.7 1866.67  5467.8 1867.82  5686.9 1866.88  5982.7 1869.04  6029.3 1869.27
  6240.3 1871.02  6338.8 1871.25  6360.0 1869.58  6402.6 1871.00  6639.4 1871.44
#Mann=8,-1,0
  3074.2    0.07       0  3557.0    0.16       0  3740.9    0.07       0
  4279.8    0.07       0  4291.3    0.07       0  5982.7   0.035       0
  6029.3    0.07       0  6240.3   0.035       0
Bank Sta=4279.8,4291.3
Exp/Cntr=0.3,0.1

Type RM Length L Ch R = 1,10419,812,812,812
BEGIN DESCRIPTION:
South Fork 11.0
END DESCRIPTION:
XS GIS Cut Line= 3
      1443033.56      6903118.79      1444405.00      6901888.00
      1445335.69      6900426.04
#Sta/Elev= 30
  3153.7 1871.91  3313.9 1871.43  3743.2 1870.11  4019.0 1867.62  4096.8 1865.61
  4224.6 1865.95  4231.3 1865.57  4239.8 1863.27  4240.3 1862.77  4251.3 1863.27
  4253.0 1865.21  4259.7 1865.94  4606.8 1864.63  4819.7 1867.19  5004.1 1865.99
  5010.0 1863.76  5025.2 1866.19  5149.7 1864.98  5546.7 1864.51  5843.9 1866.48
  6025.9 1868.76  6125.8 1868.75  6274.0 1870.96  6365.4 1869.01  6501.9 1868.50
  6538.1 1868.99  6568.5 1871.24  6589.7 1869.81  6610.9 1869.66  6729.5 1870.79
#Mann=5,-1,0
  3153.7   0.035       0  3313.9    0.07       0  4239.8    0.07       0
  4251.3    0.07       0  6274.0   0.035       0
Bank Sta=4239.8,4251.3
Exp/Cntr=0.3,0.1

Type RM Length L Ch R = 1,9607,33,33,33
BEGIN DESCRIPTION:
Mapping XS 235c50f4
END DESCRIPTION:
XS GIS Cut Line= 6
      1443551.61      6903069.80      1444953.52      6901963.03
      1445049.01      6902023.79      1445127.13      6902006.43
      1445109.77      6901793.76      1445483.03      6900153.14
#Sta/Elev= 30
  2798.7 1870.10  3244.9 1867.44  3424.0 1864.25  3585.4 1864.86  3594.0 1861.38
  3594.5 1860.88  3605.7 1861.38  3606.3 1864.77  3728.1 1865.29  4510.4 1863.12
  4574.6 1863.97  4610.3 1869.28  4700.4 1867.43  4714.4 1864.19  4743.9 1866.92
  4749.0 1862.13  4778.1 1866.60  4794.3 1862.28  4847.6 1861.93  4900.9 1863.03
  4921.6 1868.50  4961.6 1862.03  5001.9 1861.88  5774.8 1867.27  5993.6 1867.15
  6133.4 1868.12  6345.6 1870.27  6354.8 1870.27  6356.2 1870.32  6678.4 1873.33
#Mann=11,-1,0
  2798.7    0.07       0  3244.9    0.16       0  3424.0    0.07       0
  3594.0    0.07       0  3605.7    0.07       0  5774.8   0.035       0
  5993.6    0.07       0  6133.4   0.035       0  6345.6    0.07       0
  6354.8   0.035       0  6356.2    0.07       0
Bank Sta=3594,3605.7
Exp/Cntr=0.3,0.1

Type RM Length L Ch R = 1,9574,32,32,32
BEGIN DESCRIPTION:
Mapping XS 4017b781
END DESCRIPTION:
XS GIS Cut Line= 6
      1443542.90      6903100.20      1444970.88      6902006.43
      1445105.43      6902045.49      1445166.19      6901967.37
      1445122.79      6901876.22      1445530.77      6900170.50
#Sta/Elev= 30
  2771.0 1869.85  3207.4 1867.35  3423.8 1864.85  3608.2 1865.20  3643.5 1862.35
  3666.3 1864.83  3844.3 1863.19  4108.7 1865.91  4499.4 1862.90  4563.8 1863.78
  4591.5 1869.14  4663.8 1866.13  4744.1 1868.96  4818.4 1868.49  4824.0 1865.60
  4852.4 1861.96  4869.4 1866.39  4874.9 1862.74  4918.2 1869.08  4949.1 1863.30
  4994.6 1861.91  4995.1 1861.41  5006.3 1861.91  5103.3 1865.11  5134.1 1863.01
  5854.2 1866.44  5936.9 1866.57  6153.9 1868.38  6382.6 1870.11  6663.6 1873.20
#Mann=9,-1,0
  2771.0    0.07       0  3207.4    0.16       0  3423.8    0.07       0
  4994.6    0.07       0  5006.3    0.07       0  5854.2   0.035       0
  5936.9    0.07       0  6153.9   0.035       0  6382.6    0.07       0
Bank Sta=4994.6,5006.3
Exp/Cntr=0.3,0.1

Type RM Length L Ch R = 1,9542,1421,1421,1421
BEGIN DESCRIPTION:
Mapping XS 75193cae
END DESCRIPTION:
XS GIS Cut Line= 6
      1443577.66      6903126.21      1444957.86      6902080.21
      1445118.45      6902067.19      1445179.21      6901997.75
      1445161.85      6901841.50      1445569.83      6900157.51
#Sta/Elev= 30
  2818.1 1870.21  3196.8 1867.50  3422.7 1865.74  3693.1 1864.89  3700.1 1863.11
  3714.7 1864.82  3856.2 1864.29  3870.7 1862.62  3893.6 1864.32  4149.5 1865.53
  4722.5 1862.71  4736.5 1863.04  4743.4 1865.02  4750.1 1863.01  4771.9 1865.13
  4786.1 1864.58  4792.8 1862.62  4805.6 1863.86  4823.0 1868.53  4893.1 1867.06
  4920.3 1862.36  4925.4 1864.77  4938.3 1862.17  4938.8 1861.67  4950.0 1862.17
  5407.0 1865.61  5870.1 1865.88  6184.5 1868.53  6417.9 1870.90  6693.7 1873.48
#Mann=7,-1,0
  2818.1    0.07       0  3196.8    0.16       0  3422.7    0.07       0
  4938.3    0.07       0  4950.0    0.07       0  6184.5   0.035       0
  6417.9    0.07       0
Bank Sta=4938.3,4950
Exp/Cntr=0.3,0.1

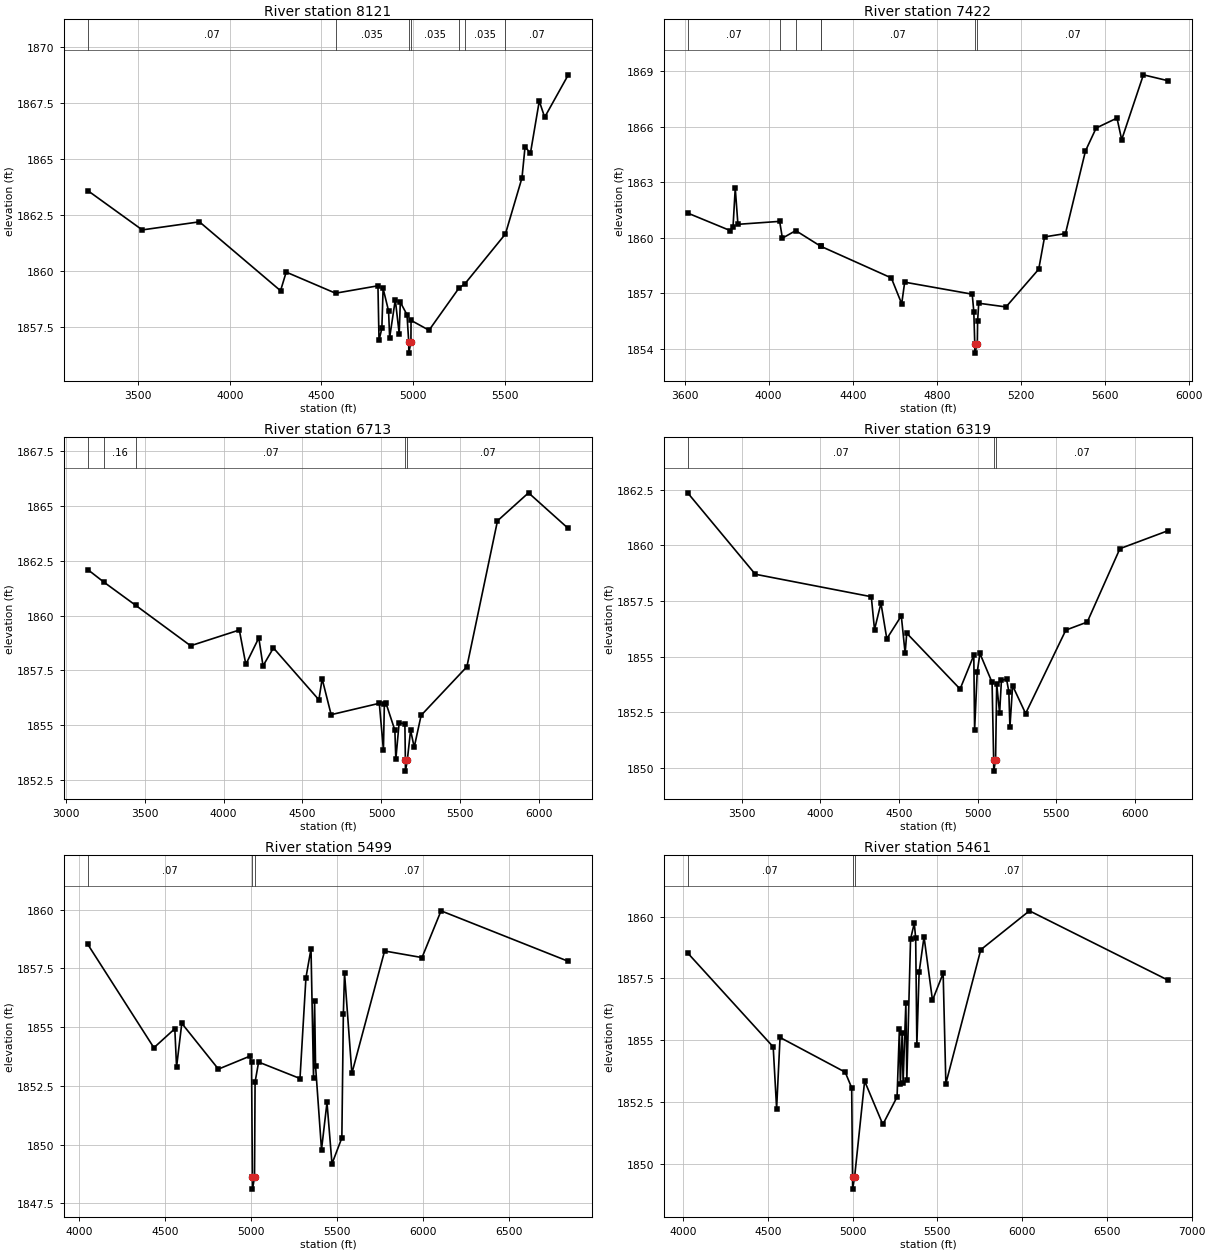
Type RM Length L Ch R = 1,8121,699,699,699
BEGIN DESCRIPTION:
South Fork 10.0
END DESCRIPTION:
XS GIS Cut Line= 3
      1444741.89      6903332.32      1446254.33      6902403.27
      1447039.10      6902084.34
#Sta/Elev= 30
  3225.0 1863.59  3522.1 1861.84  3834.1 1862.20  4276.8 1859.13  4307.6 1859.96
  4576.8 1859.02  4808.3 1859.35  4814.2 1856.92  4829.6 1857.45  4836.5 1859.23
  4866.3 1858.23  4872.2 1857.04  4903.0 1858.73  4924.3 1857.22  4930.4 1858.62
  4966.9 1858.06  4976.3 1856.85  4976.8 1856.35  4988.3 1856.85  4989.0 1857.81
  5087.1 1857.37  5249.8 1859.24  5282.9 1859.44  5504.1 1861.66  5594.4 1864.16
  5611.1 1865.54  5640.6 1865.26  5688.7 1867.58  5718.2 1866.86  5847.1 1868.75
#Mann=7,-1,0
  3225.0    0.07       0  4576.8   0.035       0  4976.3   0.035       0
  4988.3   0.035       0  5249.8    0.07       0  5282.9   0.035       0
  5504.1    0.07       0
Bank Sta=4976.3,4988.3
Exp/Cntr=0.3,0.1

Type RM Length L Ch R = 1,7422,709,709,709
BEGIN DESCRIPTION:
Mapping XS 8129d16d
END DESCRIPTION:
XS GIS Cut Line= 3
      1445231.55      6903431.24      1446549.22      6902967.71
      1447339.74      6902564.13
#Sta/Elev= 30
  3614.7 1861.33  3817.4 1860.38  3830.4 1860.57  3841.0 1862.68  3853.7 1860.72
  4052.1 1860.88  4065.2 1859.97  4128.6 1860.38  4247.7 1859.53  4248.0 1859.53
  4583.0 1857.82  4632.4 1856.42  4646.6 1857.59  4967.7 1856.94  4975.2 1856.00
  4979.8 1854.25  4980.3 1853.75  4991.9 1854.25  4993.4 1855.51  4998.7 1856.45
  5128.3 1856.25  5283.8 1858.29  5311.7 1860.04  5411.0 1860.22  5506.1 1864.69
  5556.9 1865.93  5656.0 1866.47  5678.3 1865.30  5781.5 1868.81  5899.1 1868.49
#Mann=7,-1,0
  3614.7    0.07       0  4052.1    0.16       0  4128.6    0.07       0
  4247.7    0.16       0  4248.0    0.07       0  4979.8    0.07       0
  4991.9    0.07       0
Bank Sta=4979.8,4991.9
Exp/Cntr=0.3,0.1

Type RM Length L Ch R = 1,6713,394,394,394
BEGIN DESCRIPTION:
South Fork 7.0
END DESCRIPTION:
XS GIS Cut Line= 3
      1444991.96      6903920.83      1446805.00      6903488.00
      1447794.04      6902847.90
#Sta/Elev= 30
  3140.9 1862.10  3240.5 1861.54  3443.5 1860.47  3791.7 1858.62  4100.2 1859.34
  4141.3 1857.77  4223.5 1858.98  4250.2 1857.70  4316.1 1858.52  4603.9 1856.15
  4624.5 1857.11  4681.5 1855.47  4986.4 1855.99  5012.5 1853.86  5018.4 1855.94
  5027.6 1856.02  5085.0 1854.76  5091.0 1853.43  5112.1 1855.10  5148.4 1855.05
  5151.5 1853.39  5152.0 1852.89  5163.7 1853.39  5184.6 1854.76  5207.4 1853.98
  5251.2 1855.44  5540.9 1857.66  5734.7 1864.33  5931.2 1865.61  6183.0 1863.98
#Mann=5,-1,0
  3140.9    0.07       0  3240.5    0.16       0  3443.5    0.07       0
  5151.5    0.07       0  5163.7    0.07       0
Bank Sta=5151.5,5163.7
Exp/Cntr=0.3,0.1

Type RM Length L Ch R = 1,6319,820,820,820
BEGIN DESCRIPTION:
South Fork 6.0
END DESCRIPTION:
XS GIS Cut Line= 3
      1445155.02      6904188.00      1446955.00      6903788.00
      1448075.29      6903327.08
#Sta/Elev= 30
  3156.2 1862.36  3586.4 1858.70  4324.0 1857.69  4344.5 1856.21  4385.5 1857.40
  4422.6 1855.80  4514.8 1856.83  4539.1 1855.15  4549.4 1856.05  4888.7 1853.54
  4975.8 1855.06  4980.9 1851.69  4997.5 1854.30  5014.8 1855.14  5092.0 1853.84
  5102.1 1850.35  5102.6 1849.85  5114.3 1850.35  5121.4 1853.77  5140.0 1852.45
  5151.5 1853.93  5183.9 1853.99  5198.7 1853.42  5205.5 1851.82  5222.6 1853.69
  5305.3 1852.44  5561.1 1856.19  5697.1 1856.55  5904.9 1859.85  6211.5 1860.66
#Mann=3,-1,0
  3156.2    0.07       0  5102.1    0.07       0  5114.3    0.07       0
Bank Sta=5102.1,5114.3
Exp/Cntr=0.3,0.1

Type RM Length L Ch R = 1,5499,38,38,38
BEGIN DESCRIPTION:
Mapping XS 16f2ed95
END DESCRIPTION:
XS GIS Cut Line= 6
      1445925.95      6904603.13      1447134.29      6904373.96
      1447210.68      6904429.52      1447273.18      6904429.52
      1447314.85      6904353.13      1448446.46      6903672.77
#Sta/Elev= 30
  4048.6 1858.52  4433.0 1854.12  4554.7 1854.93  4564.9 1853.30  4595.3 1855.16
  4808.3 1853.21  4990.8 1853.76  5001.0 1853.51  5006.1 1848.60  5006.6 1848.10
  5018.4 1848.60  5021.6 1852.66  5042.2 1853.51  5282.9 1852.81  5317.6 1857.11
  5347.0 1858.33  5361.6 1852.84  5367.8 1856.12  5373.4 1853.35  5408.1 1849.78
  5440.0 1851.79  5469.0 1849.18  5526.4 1850.28  5535.2 1855.57  5542.0 1857.30
  5584.7 1853.03  5775.1 1858.24  5992.7 1857.96  6103.4 1859.95  6843.7 1857.80
#Mann=3,-1,0
  4048.6    0.07       0  5006.1    0.07       0  5018.4    0.07       0
Bank Sta=5006.1,5018.4
Exp/Cntr=0.3,0.1

Type RM Length L Ch R = 1,5461,61,61,61
BEGIN DESCRIPTION:
Mapping XS 322fccc8
END DESCRIPTION:
XS GIS Cut Line= 6
      1445925.91      6904617.03      1446898.18      6904471.19
      1447148.18      6904436.46      1447252.35      6904492.02
      1447342.63      6904373.96      1448507.42      6903726.85
#Sta/Elev= 30
  4026.4 1858.53  4531.1 1854.74  4551.3 1852.25  4571.5 1855.12  4955.8 1853.72
  4994.2 1853.09  4999.3 1849.50  4999.8 1849.00  5011.6 1849.50  5070.5 1853.36
  5178.0 1851.61  5261.9 1852.72  5275.6 1855.45  5281.3 1853.23  5291.9 1855.31
  5297.5 1853.30  5313.8 1856.51  5319.5 1853.40  5341.5 1859.09  5363.4 1859.73
  5371.7 1859.13  5378.7 1854.81  5392.0 1857.75  5421.0 1859.18  5470.9 1856.62
  5533.8 1857.71  5549.8 1853.26  5755.8 1858.66  6042.9 1860.23  6861.1 1857.43
#Mann=3,-1,0
  4026.4    0.07       0  4999.3    0.07       0  5011.6    0.07       0
Bank Sta=4999.3,5011.6
Exp/Cntr=0.3,0.1

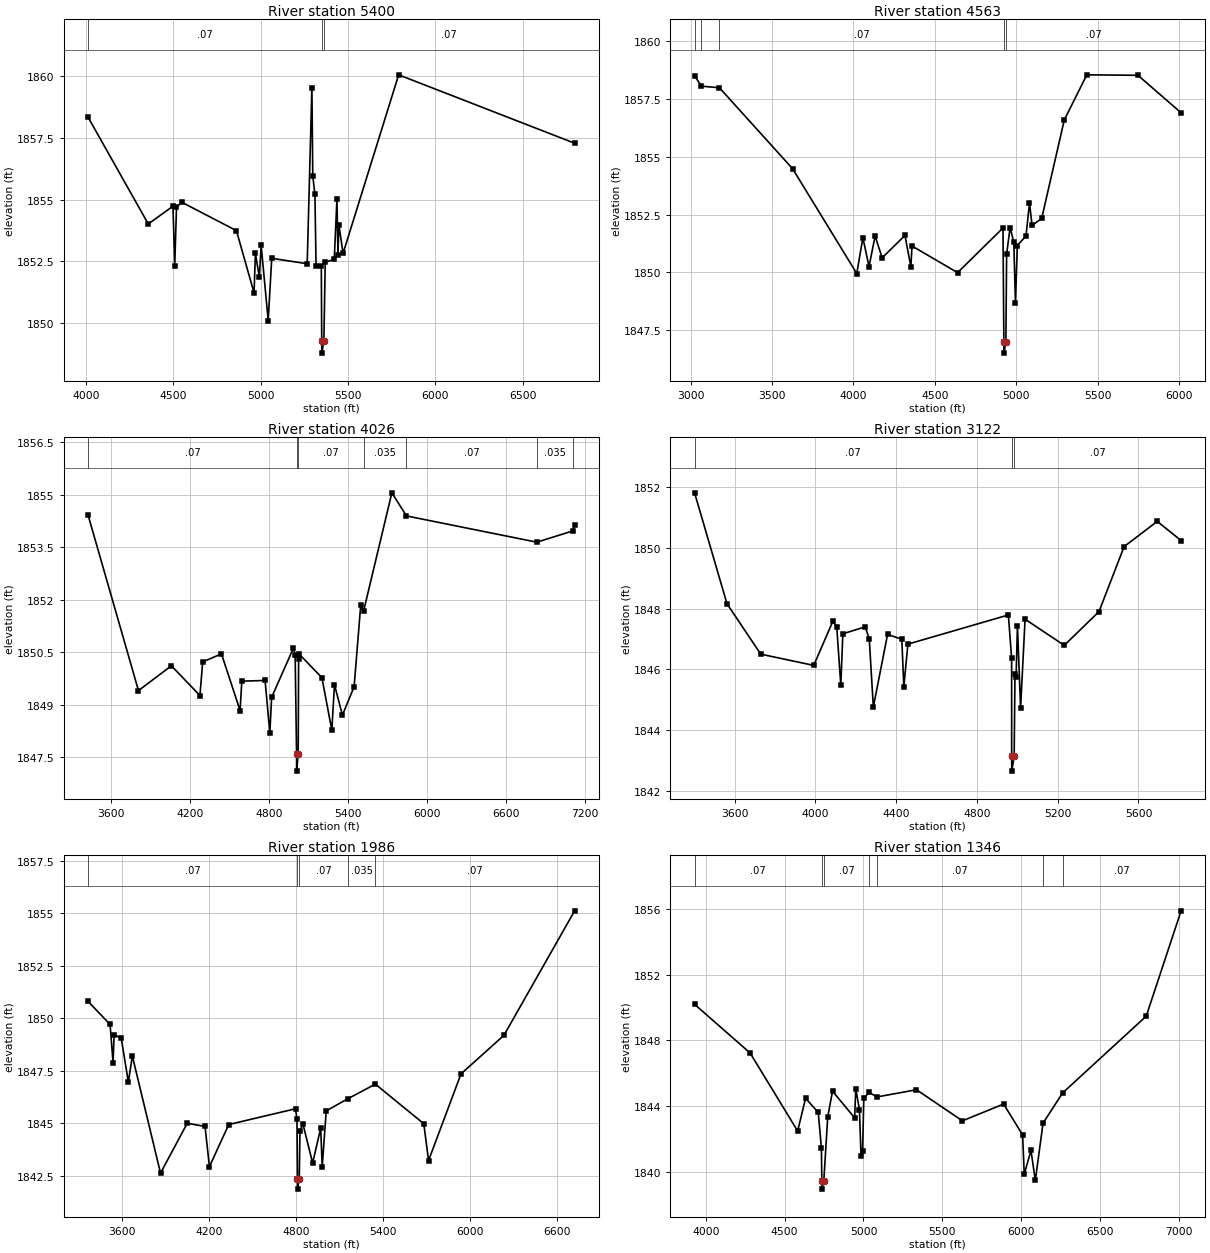
Type RM Length L Ch R = 1,5400,837,837,837
BEGIN DESCRIPTION:
Mapping XS 81beef59
END DESCRIPTION:
XS GIS Cut Line= 6
      1445953.73      6904644.80      1447127.35      6904485.07
      1447238.46      6904505.91      1447287.07      6904505.91
      1447335.68      6904429.52      1448521.55      6903791.51
#Sta/Elev= 30
  4012.9 1858.33  4357.1 1854.01  4498.3 1854.73  4508.4 1852.32  4518.5 1854.68
  4548.7 1854.89  4861.4 1853.74  4962.3 1851.22  4969.9 1852.82  4992.6 1851.85
  5002.7 1853.15  5043.2 1850.10  5063.4 1852.62  5266.2 1852.40  5293.2 1859.53
  5298.2 1855.95  5310.4 1855.21  5317.0 1852.31  5347.0 1852.31  5349.4 1849.28
  5349.9 1848.78  5361.7 1849.28  5369.4 1852.46  5421.1 1852.58  5436.3 1855.01
  5442.2 1852.77  5447.5 1853.97  5471.5 1852.82  5789.5 1860.05  6796.2 1857.28
#Mann=3,-1,0
  4012.9    0.07       0  5349.4    0.07       0  5361.7    0.07       0
Bank Sta=5349.4,5361.7
Exp/Cntr=0.3,0.1

Type RM Length L Ch R = 1,4563,537,537,537
BEGIN DESCRIPTION:
Mapping XS 3da0a9c1
END DESCRIPTION:
XS GIS Cut Line= 4
      1445758.88      6905861.30      1447196.79      6905047.57
      1447481.51      6904943.41      1448377.32      6904429.54
#Sta/Elev= 30
  3025.0 1858.50  3067.2 1858.05  3177.8 1857.98  3627.2 1854.48  4021.2 1849.95
  4058.7 1851.50  4096.3 1850.25  4133.8 1851.57  4177.1 1850.63  4317.1 1851.60
  4353.4 1850.24  4360.4 1851.14  4640.4 1849.99  4919.1 1851.92  4924.6 1847.01
  4925.1 1846.51  4937.0 1847.01  4941.5 1850.78  4962.8 1851.94  4985.7 1851.30
  4995.7 1848.68  5007.4 1851.16  5060.5 1851.58  5082.0 1853.00  5097.8 1852.03
  5156.8 1852.33  5295.7 1856.59  5434.0 1858.54  5748.0 1858.52  6013.1 1856.90
#Mann=5,-1,0
  3025.0    0.07       0  3067.2   0.035       0  3177.8    0.07       0
  4924.6    0.07       0  4937.0    0.07       0
Bank Sta=4924.6,4937
Exp/Cntr=0.3,0.1

Type RM Length L Ch R = 1,4026,904,904,904
BEGIN DESCRIPTION:
South Fork 3.0
END DESCRIPTION:
XS GIS Cut Line= 5
      1446158.24      6906204.15      1447105.36      6905537.64
      1447508.04      6905436.58      1447925.96      6905387.85
      1449304.99      6904388.01
#Sta/Elev= 30
  3426.7 1854.42  3809.4 1849.41  4059.5 1850.12  4276.4 1849.27  4297.3 1850.23
  4440.1 1850.46  4581.6 1848.84  4594.8 1849.68  4771.7 1849.70  4807.7 1848.20
  4821.6 1849.22  4986.6 1850.62  5000.0 1850.44  5010.9 1847.61  5011.4 1847.11
  5023.3 1847.61  5026.5 1850.31  5031.5 1850.45  5203.5 1849.78  5278.8 1848.28
  5299.0 1849.58  5359.4 1848.71  5448.2 1849.52  5498.5 1851.85  5520.2 1851.68
  5735.1 1855.06  5846.3 1854.40  6837.1 1853.65  7108.7 1853.97  7124.1 1854.13
#Mann=7,-1,0
  3426.7    0.07       0  5010.9    0.07       0  5023.3    0.07       0
  5520.2   0.035       0  5846.3    0.07       0  6837.1   0.035       0
  7108.7    0.07       0
Bank Sta=5010.9,5023.3
Exp/Cntr=0.3,0.1

Type RM Length L Ch R = 1,3122,1136,1136,1136
BEGIN DESCRIPTION:
Mapping XS 20900a53
END DESCRIPTION:
XS GIS Cut Line= 3
      1446405.60      6906360.42      1447620.40      6906221.19
      1448675.98      6905679.51
#Sta/Elev= 30
  3402.0 1851.81  3562.4 1848.16  3729.6 1846.50  3992.1 1846.13  4086.4 1847.58
  4106.0 1847.40  4126.1 1845.47  4136.2 1847.17  4246.9 1847.40  4267.0 1847.00
  4287.2 1844.76  4357.6 1847.15  4428.1 1846.99  4438.2 1845.43  4458.3 1846.83
  4955.9 1847.79  4972.0 1846.36  4972.2 1843.15  4972.7 1842.65  4984.6 1843.15
  4988.6 1845.86  4994.2 1845.75  5000.8 1847.44  5016.4 1844.73  5038.6 1847.65
  5232.7 1846.79  5404.6 1847.90  5529.1 1850.04  5693.1 1850.87  5811.2 1850.24
#Mann=3,-1,0
  3402.0    0.07       0  4972.2    0.07       0  4984.6    0.07       0
Bank Sta=4972.2,4984.6
Exp/Cntr=0.3,0.1

Type RM Length L Ch R = 1,1986,640,640,640
BEGIN DESCRIPTION:
Mapping XS 1cd4729d
END DESCRIPTION:
XS GIS Cut Line= 3
      1446956.85      6907011.45      1448550.96      6906665.63
      1450243.63      6906332.65
#Sta/Elev= 30
  3364.1 1850.80  3515.7 1849.71  3536.2 1847.88  3543.4 1849.22  3592.5 1849.06
  3641.7 1846.97  3669.2 1848.21  3863.6 1842.64  4047.8 1845.01  4170.6 1844.86
  4201.0 1842.95  4334.3 1844.95  4794.8 1845.70  4805.0 1845.21  4808.3 1842.38
  4808.8 1841.88  4820.8 1842.38  4825.5 1844.64  4845.9 1844.98  4912.9 1843.12
  4968.7 1844.78  4979.0 1842.93  5006.7 1845.60  5154.0 1846.17  5345.8 1846.87
  5679.8 1844.99  5712.8 1843.24  5936.7 1847.36  6232.6 1849.19  6720.4 1855.11
#Mann=5,-1,0
  3364.1    0.07       0  4808.3    0.07       0  4820.8    0.07       0
  5154.0   0.035       0  5345.8    0.07       0
Bank Sta=4808.3,4820.8
Exp/Cntr=0.3,0.1

Type RM Length L Ch R = 1,1346,604,604,604
BEGIN DESCRIPTION:
South Fork 2.0
END DESCRIPTION:
XS GIS Cut Line= 3
      1447134.32      6907242.02      1448205.00      6907138.00
      1450205.01      6906938.00
#Sta/Elev= 30
  3928.8 1850.19  4281.1 1847.23  4582.5 1842.49  4632.8 1844.48  4713.2 1843.62
  4733.2 1841.45  4735.9 1839.46  4736.4 1838.96  4748.4 1839.46  4773.4 1843.36
  4803.6 1844.91  4944.2 1843.29  4951.0 1845.07  4974.4 1843.78  4984.4 1840.99
  4994.5 1841.27  5002.0 1844.49  5035.8 1844.84  5085.4 1844.56  5336.2 1845.00
  5627.6 1843.11  5888.9 1844.13  6009.5 1842.25  6019.6 1839.86  6062.3 1841.31
  6089.9 1839.49  6139.0 1842.97  6263.5 1844.81  6793.4 1849.47  7014.5 1855.87
#Mann=7,-1,0
  3928.8    0.07       0  4735.9    0.07       0  4748.4    0.07       0
  5035.8    0.16       0  5085.4    0.07       0  6139.0   0.035       0
  6263.5    0.07       0
Bank Sta=4735.9,4748.4
Exp/Cntr=0.3,0.1