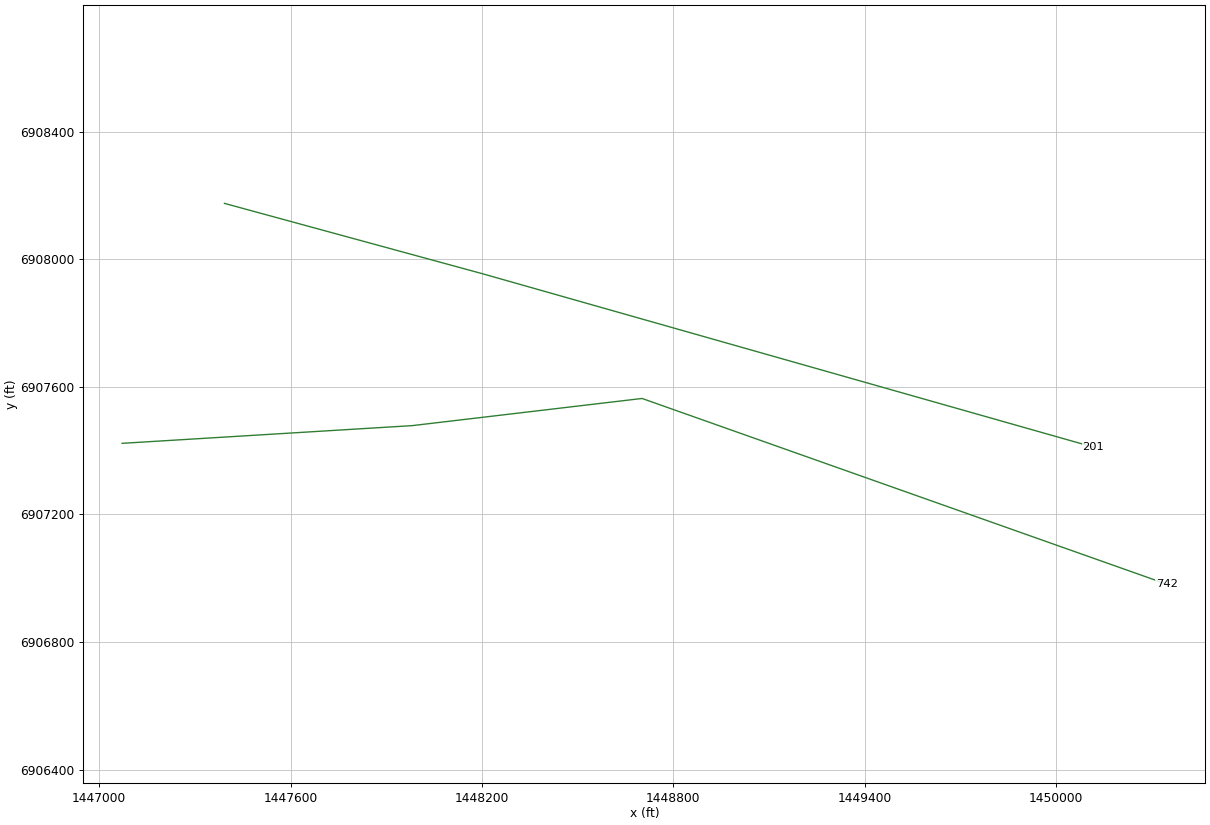
HEC-RAS study South Fork.prj: South Fork Base Level Engineering

--- South Fork.g01 (geometry) --- (continued)

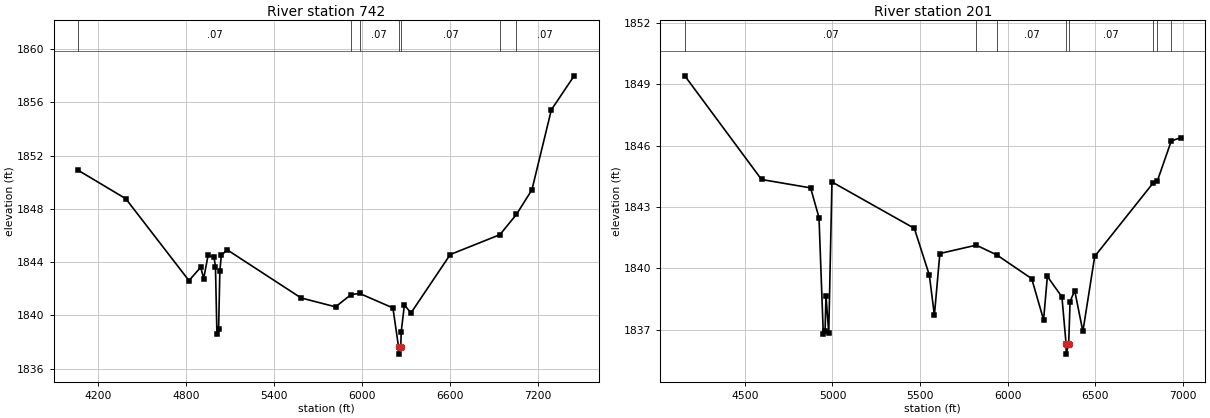
Type RM Length L Ch R = 1,742,541,541,541
BEGIN DESCRIPTION:
Mapping XS b793b5a3
END DESCRIPTION:
XS GIS Cut Line= 4
      1447071.78      6907422.57      1447981.51      6907478.13
      1448701.80      6907563.25      1450346.58      6906981.08
#Sta/Elev= 30
  4063.5 1850.89  4387.3 1848.76  4818.1 1842.61  4898.3 1843.62  4918.3 1842.76
  4948.4 1844.51  4988.5 1844.38  4998.6 1843.67  5008.7 1838.62  5020.1 1838.95
  5028.8 1843.37  5038.9 1844.52  5079.1 1844.92  5582.6 1841.31  5817.9 1840.64
  5923.2 1841.56  5981.2 1841.65  6209.0 1840.56  6247.9 1837.59  6248.4 1837.09
  6262.5 1837.59  6265.5 1838.77  6287.1 1840.77  6332.6 1840.19  6600.0 1844.57
  6938.6 1846.06  7051.3 1847.58  7156.9 1849.43  7289.5 1855.44  7445.0 1857.99
#Mann=7,-1,0
  4063.5    0.07       0  5923.2    0.16       0  5981.2    0.07       0
  6247.9    0.07       0  6262.5    0.07       0  6938.6   0.035       0
  7051.3    0.07       0
Bank Sta=6247.9,6262.5
Exp/Cntr=0.3,0.1

Type RM Length L Ch R = 1,201,0,0,0
BEGIN DESCRIPTION:
South Fork 1.0
END DESCRIPTION:
XS GIS Cut Line= 3
      1447392.62      6908174.84      1448205.44      6907953.18
      1450116.55      6907410.76
#Sta/Elev= 30
  4157.5 1849.42  4595.3 1844.35  4875.2 1843.94  4923.2 1842.49  4947.7 1836.80
  4957.8 1836.92  4963.0 1838.67  4978.8 1836.83  4997.2 1844.23  5467.3 1841.96
  5552.9 1839.67  5581.6 1837.71  5612.8 1840.73  5820.4 1841.14  5938.0 1840.66
  6136.9 1839.50  6204.7 1837.49  6226.2 1839.61  6309.3 1838.61  6333.1 1836.31
  6333.6 1835.81  6347.8 1836.31  6355.9 1838.38  6382.1 1838.92  6428.9 1836.92
  6496.4 1840.59  6829.8 1844.18  6853.8 1844.28  6933.5 1846.24  6986.6 1846.39
#Mann=8,-1,0
  4157.5    0.07       0  5820.4    0.16       0  5938.0    0.07       0
  6333.1    0.07       0  6347.8    0.07       0  6829.8   0.035       0
  6853.8    0.07       0  6933.5   0.035       0
Bank Sta=6333.1,6347.8
Exp/Cntr=0.3,0.1

Chan Stop Cuts=-1