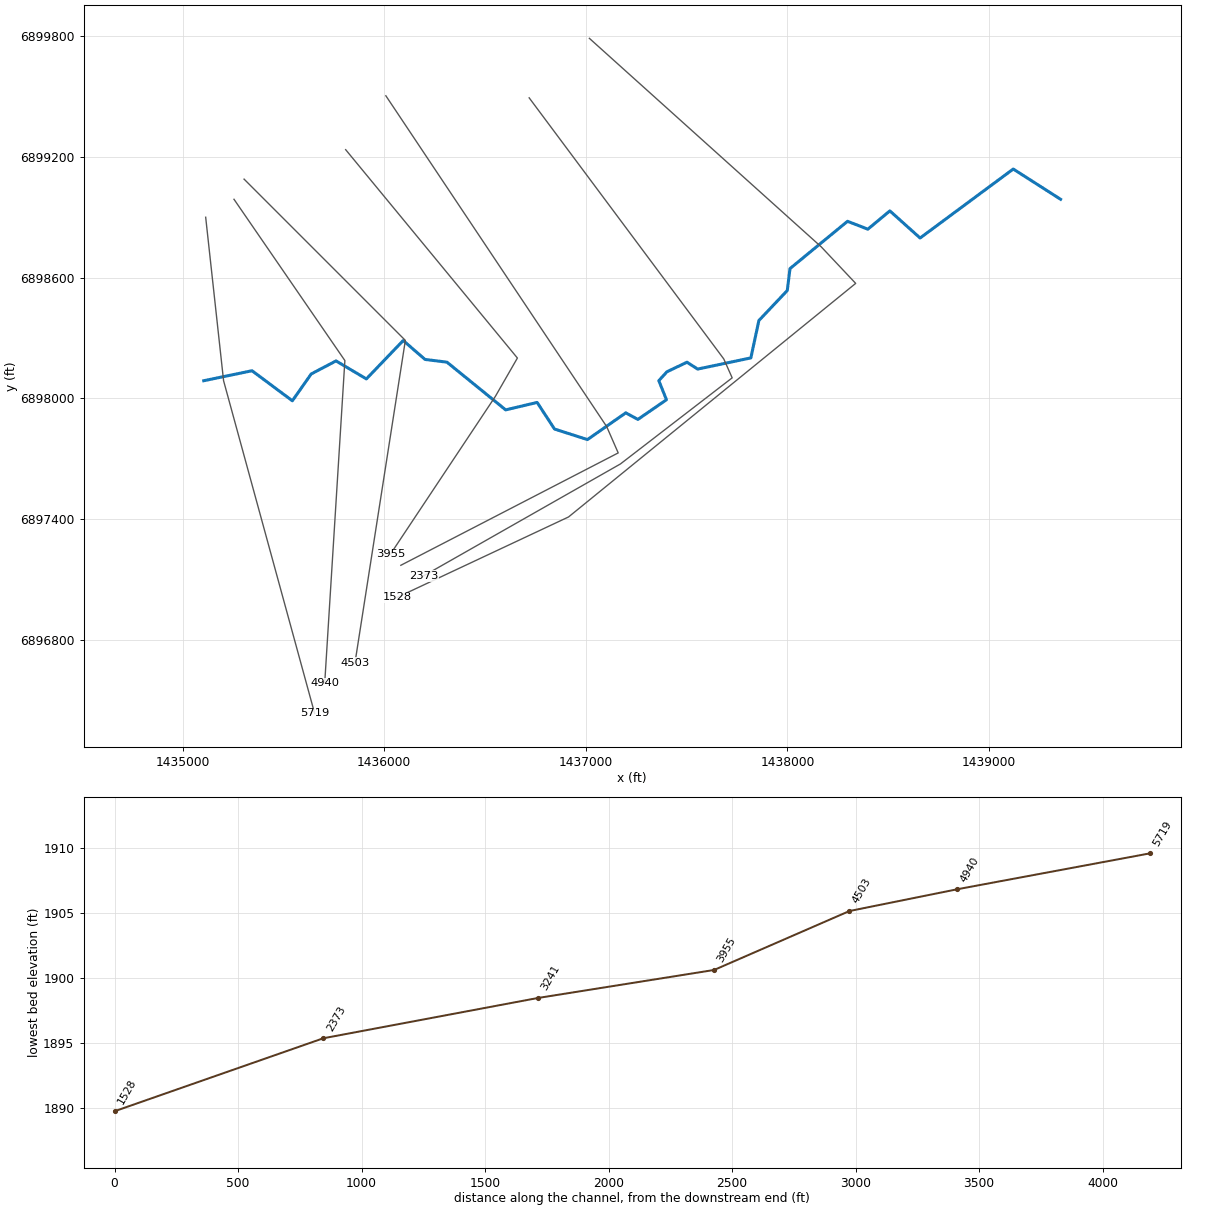
--- South Fork Trib1.prj (project) ---

Proj Title=South Fork Trib1 Base Level Engineering
Current Plan=p01
Default Exp/Contr=0.3,0.1
English Units
Geom File=g01
Flow File=f01
Plan File=p01
BEGIN DESCRIPTION:
South Fork Trib1
END DESCRIPTION:

--- South Fork Trib1.p01 (plan) ---

Plan Title=Multiple Run
Short Identifier=Multiple
Geom File=g01
Flow File=f01
Subcritical Flow
K Sum by GR= 0
Std Step Tol= 0.01
Critical Tol= 0.01
Num of Std Step Trials= 20
Max Error Tol= 0.3
Flow Tol Ratio= 0.001
Split Flow NTrial= 30
Split Flow Tol= 0.02
Split Flow Ratio= 0.02
Log Output Level= 0
Friction Slope Method= 1
Unsteady Friction Slope Method= 2
Unsteady Bridges Friction Slope Method= 1
Parabolic Critical Depth
Global Vel Dist=  1 , 1 , 1
Global Log Level= 0
CheckData=True
Encroach Param= -1, 0, 0, 0
BEGIN DESCRIPTION:
Multiple Run
END DESCRIPTION:

--- South Fork Trib1.f01 (steady flow) ---

Flow Title=Multiple
Number of Profiles=7
Profile Names=10-year,25-year,50-year,1pct_min,100-year,1pct_plu,500-year
River Rch & RM= South Fork Trib1,Reach-1,5719
     277     382     468     285     568    1134     847
River Rch & RM= South Fork Trib1,Reach-1,2373
     340     478     593     365     728    1454    1114
Boundary for River Rch & Prof#=South Fork Trib1,Reach-1,1
Up Type=0
Dn Type=3
Dn Slope=0.005
Boundary for River Rch & Prof#=South Fork Trib1,Reach-1,2
Up Type=0
Dn Type=3
Dn Slope=0.005
Boundary for River Rch & Prof#=South Fork Trib1,Reach-1,3
Up Type=0
Dn Type=3
Dn Slope=0.005
Boundary for River Rch & Prof#=South Fork Trib1,Reach-1,4
Up Type=0
Dn Type=3
Dn Slope=0.005
Boundary for River Rch & Prof#=South Fork Trib1,Reach-1,5
Up Type=0
Dn Type=3
Dn Slope=0.005
Boundary for River Rch & Prof#=South Fork Trib1,Reach-1,6
Up Type=0
Dn Type=3
Dn Slope=0.005
Boundary for River Rch & Prof#=South Fork Trib1,Reach-1,7
Up Type=0
Dn Type=3
Dn Slope=0.005

--- South Fork Trib1.g01 (geometry) ---

Geom Title=Existing Conditions

River Reach=South Fork Trib1,Reach-1
Reach XY= 30
      1435105.00      6898088.00      1435344.45      6898137.51
      1435544.51      6897988.49      1435637.95      6898121.51
      1435761.12      6898186.24      1435911.69      6898096.96
      1436094.31      6898287.46      1436202.58      6898193.54
      1436311.17      6898180.14      1436602.58      6897943.41
      1436758.67      6897980.30      1436844.90      6897848.39
      1437008.32      6897796.04      1437198.34      6897928.68
      1437258.33      6897896.02      1437400.19      6897993.62
      1437362.27      6898088.28      1437402.16      6898132.20
      1437501.76      6898179.76      1437554.90      6898145.80
      1437818.74      6898201.20      1437858.54      6898386.53
      1437999.48      6898535.57      1438012.86      6898644.19
      1438298.27      6898878.85      1438398.95      6898839.68
      1438508.34      6898930.40      1438658.23      6898795.83
      1439120.34      6899138.05      1439355.00      6898988.00

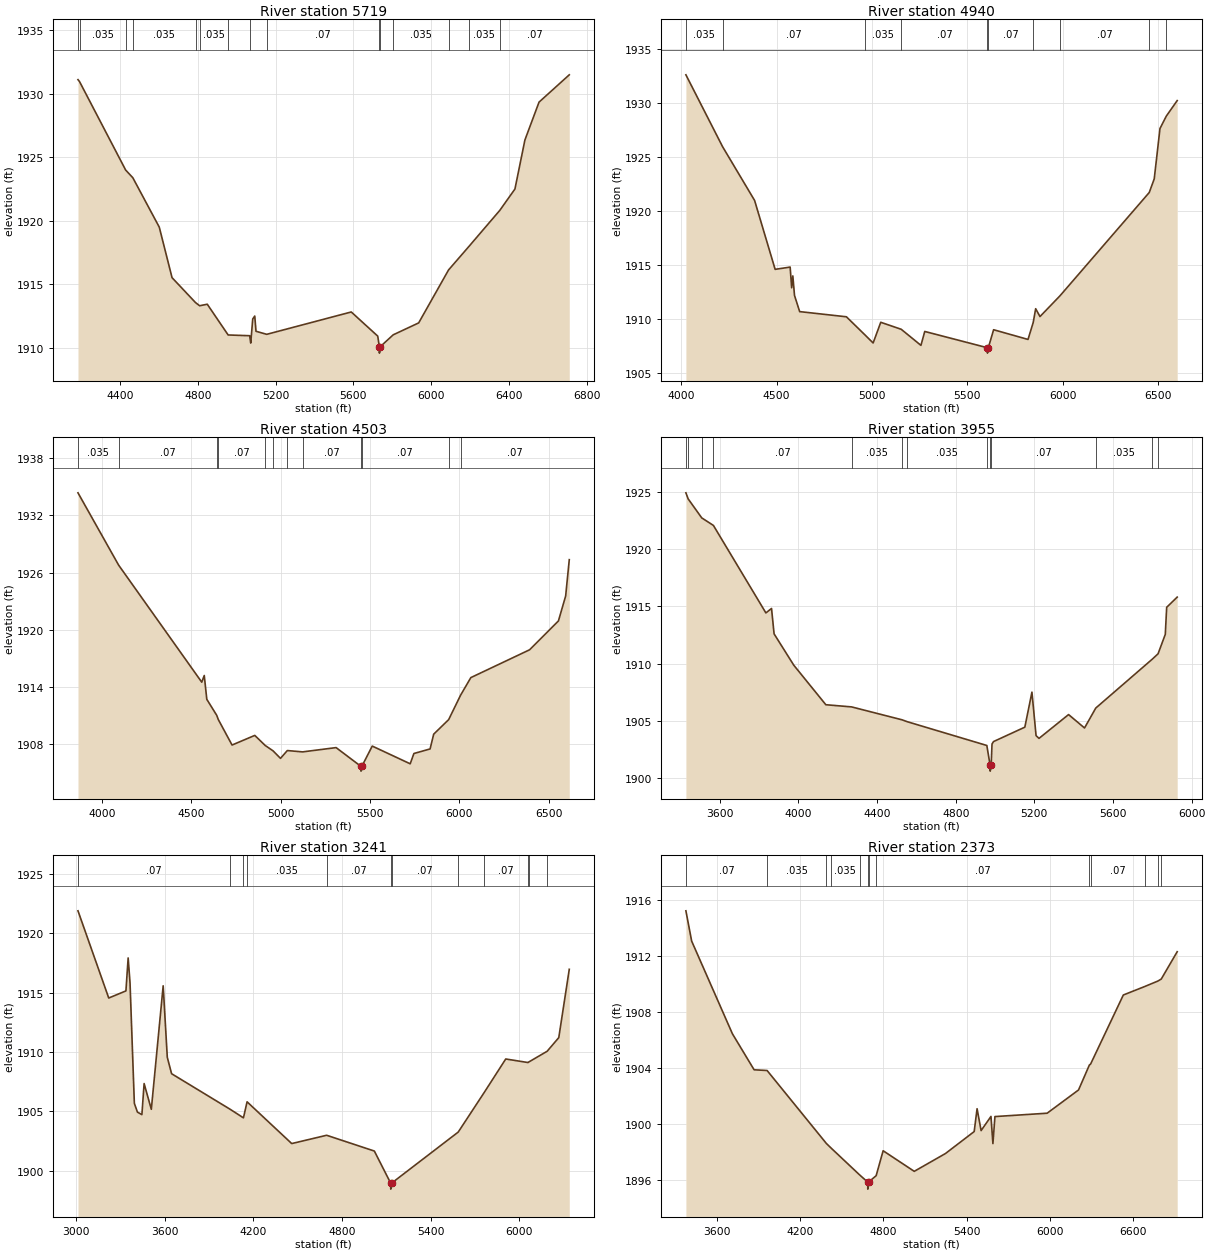
Type RM Length L Ch R = 1,5719,779,779,779
BEGIN DESCRIPTION:
South Fork Trib1 4.0
END DESCRIPTION:
XS GIS Cut Line= 3
      1435114.55      6898898.95      1435203.36      6898088.00
      1435655.00      6896438.00
#Sta/Elev= 30
  4184.2 1931.12  4192.1 1930.97  4429.5 1924.00  4466.2 1923.40  4602.2 1919.51
  4668.0 1915.53  4788.6 1913.57  4809.7 1913.32  4849.1 1913.44  4956.4 1911.02
  5067.2 1910.96  5072.6 1910.38  5082.9 1912.28  5093.3 1912.51  5099.7 1911.31
  5154.9 1911.07  5589.5 1912.83  5725.7 1910.93  5734.1 1910.09  5734.4 1909.59
  5738.1 1910.09  5805.2 1911.03  5936.3 1911.97  6090.0 1916.14  6192.5 1917.95
  6353.5 1920.83  6431.3 1922.51  6482.6 1926.37  6555.2 1929.35  6710.7 1931.50
#Mann=15,-1,0
  4184.2    0.07       0  4192.1   0.035       0  4429.5    0.07       0
  4466.2   0.035       0  4788.6    0.07       0  4809.7   0.035       0
  4956.4    0.07       0  5067.2   0.035       0  5154.9    0.07       0
  5734.1    0.07       0  5738.1    0.07       0  5805.2   0.035       0
  6090.0    0.07       0  6192.5   0.035       0  6353.5    0.07       0
Bank Sta=5734.1,5738.1
Exp/Cntr=0.3,0.1

Type RM Length L Ch R = 1,4940,437,437,437
BEGIN DESCRIPTION:
South Fork Trib1 3.0
END DESCRIPTION:
XS GIS Cut Line= 3
      1435254.99      6898988.02      1435805.00      6898188.00
      1435705.00      6896587.97
#Sta/Elev= 30
  4025.3 1932.64  4217.3 1925.98  4385.2 1920.99  4492.8 1914.60  4571.4 1914.81
  4579.4 1912.89  4585.5 1913.99  4594.3 1912.18  4621.3 1910.68  4866.2 1910.20
  4961.7 1908.55  5006.2 1907.77  5046.2 1909.69  5153.5 1909.04  5256.7 1907.55
  5276.7 1908.84  5604.8 1907.33  5605.2 1906.83  5609.8 1907.33  5637.4 1909.00
  5817.7 1908.10  5844.9 1909.67  5857.8 1910.95  5880.4 1910.22  5984.9 1912.14
  6453.0 1921.73  6479.0 1922.99  6509.1 1927.66  6542.2 1928.81  6599.3 1930.25
#Mann=10,-1,0
  4025.3   0.035       0  4217.3    0.07       0  4961.7   0.035       0
  5153.5    0.07       0  5604.8   0.035       0  5609.8    0.07       0
  5844.9   0.035       0  5984.9    0.07       0  6453.0   0.035       0
  6542.2    0.07       0
Bank Sta=5604.8,5609.8
Exp/Cntr=0.3,0.1

Type RM Length L Ch R = 1,4503,548,548,548
BEGIN DESCRIPTION:
South Fork Trib1 2.0
END DESCRIPTION:
XS GIS Cut Line= 3
      1435304.98      6899088.02      1436105.00      6898288.00
      1435855.00      6896688.02
#Sta/Elev= 30
  3864.9 1934.37  4092.5 1926.78  4557.9 1914.49  4572.0 1915.19  4586.2 1912.69
  4641.8 1911.01  4650.5 1910.57  4727.6 1907.89  4854.9 1908.90  4913.5 1907.84
  4957.1 1907.28  4998.8 1906.49  5037.1 1907.31  5122.9 1907.17  5310.1 1907.62
  5449.3 1905.65  5449.6 1905.15  5454.3 1905.65  5512.5 1907.78  5725.0 1905.92
  5745.8 1907.00  5836.4 1907.48  5856.6 1909.03  5940.5 1910.56  6006.8 1913.11
  6064.6 1914.97  6393.6 1917.89  6555.0 1920.92  6595.5 1923.54  6615.7 1927.35
#Mann=12,-1,0
  3864.9   0.035       0  4092.5    0.07       0  4641.8   0.035       0
  4650.5    0.07       0  4913.5   0.035       0  4957.1    0.07       0
  5037.1   0.035       0  5122.9    0.07       0  5449.3    0.07       0
  5454.3    0.07       0  5940.5   0.035       0  6006.8    0.07       0
Bank Sta=5449.3,5454.3
Exp/Cntr=0.3,0.1

Type RM Length L Ch R = 1,3955,714,714,714
BEGIN DESCRIPTION:
Mapping XS eeaab327
END DESCRIPTION:
XS GIS Cut Line= 4
      1435808.91      6899234.09      1436660.76      6898200.56
      1436551.76      6898010.82      1436030.98      6897227.63
#Sta/Elev= 30
  3427.9 1924.92  3439.4 1924.39  3508.5 1922.73  3567.9 1922.07  3834.7 1914.43
  3863.4 1914.82  3876.4 1912.60  3976.7 1909.86  4139.6 1906.41  4270.6 1906.22
  4527.7 1905.09  4553.1 1904.93  4958.4 1902.85  4975.3 1901.11  4975.6 1900.61
  4980.3 1901.11  4984.8 1902.98  4992.3 1903.19  5151.7 1904.45  5187.8 1907.51
  5208.8 1903.71  5223.8 1903.47  5374.1 1905.55  5455.3 1904.38  5512.5 1906.12
  5800.5 1910.40  5829.3 1910.86  5866.1 1912.56  5873.1 1914.92  5926.6 1915.81
#Mann=13,-1,0
  3427.9   0.035       0  3439.4    0.07       0  3508.5   0.035       0
  3567.9    0.07       0  4270.6   0.035       0  4527.7    0.07       0
  4553.1   0.035       0  4958.4    0.07       0  4975.3    0.07       0
  4980.3    0.07       0  5512.5   0.035       0  5800.5    0.07       0
  5829.3   0.035       0
Bank Sta=4975.3,4980.3
Exp/Cntr=0.3,0.1

Type RM Length L Ch R = 1,3241,868,868,868
BEGIN DESCRIPTION:
Mapping XS cbc58275
END DESCRIPTION:
XS GIS Cut Line= 4
      1436008.33      6899501.36      1437103.76      6897860.24
      1437160.77      6897729.93      1436082.60      6897172.53
#Sta/Elev= 30
  3010.9 1921.91  3219.3 1914.56  3335.8 1915.16  3350.9 1917.94  3363.6 1915.84
  3392.9 1905.68  3413.9 1904.94  3444.0 1904.73  3459.0 1907.35  3507.9 1905.18
  3588.2 1915.59  3616.1 1909.56  3645.2 1908.18  4042.1 1905.18  4132.1 1904.46
  4156.8 1905.81  4459.3 1902.29  4695.9 1902.99  5019.2 1901.66  5129.9 1898.95
  5130.4 1898.45  5135.6 1898.95  5587.6 1903.26  5763.8 1906.60  5909.5 1909.42
  6061.1 1909.12  6064.8 1909.16  6190.0 1910.07  6268.9 1911.22  6340.0 1916.98
#Mann=12,-1,0
  3010.9    0.07       0  4042.1   0.035       0  4132.1    0.07       0
  4156.8   0.035       0  4695.9    0.07       0  5129.9    0.07       0
  5135.6    0.07       0  5587.6   0.035       0  5763.8    0.07       0
  6061.1   0.035       0  6064.8    0.07       0  6190.0   0.035       0
Bank Sta=5129.9,5135.6
Exp/Cntr=0.3,0.1

Type RM Length L Ch R = 1,2373,845,845,845
BEGIN DESCRIPTION:
Mapping XS 852ea7cf
END DESCRIPTION:
XS GIS Cut Line= 5
      1436719.13      6899491.20      1437684.42      6898196.04
      1437726.09      6898102.29      1437171.84      6897675.21
      1436194.86      6897119.66
#Sta/Elev= 30
  3376.0 1915.22  3417.4 1913.06  3711.3 1906.44  3867.7 1903.87  3961.2 1903.82
  4388.5 1898.61  4422.9 1898.28  4627.8 1896.37  4686.7 1895.85  4687.1 1895.35
  4692.4 1895.85  4747.4 1896.31  4797.7 1898.09  5022.0 1896.62  5246.8 1897.89
  5454.1 1899.46  5474.9 1901.09  5504.0 1899.53  5575.0 1900.54  5589.1 1898.60
  5603.6 1900.53  5980.0 1900.77  6206.3 1902.43  6284.4 1904.21  6293.3 1904.28
  6529.2 1909.21  6682.1 1909.81  6779.2 1910.21  6802.7 1910.35  6917.5 1912.30
#Mann=13,-1,0
  3376.0    0.07       0  3961.2   0.035       0  4388.5    0.16       0
  4422.9   0.035       0  4627.8    0.16       0  4686.7    0.07       0
  4692.4    0.16       0  4747.4    0.07       0  6284.4   0.035       0
  6293.3    0.07       0  6682.1   0.035       0  6779.2    0.07       0
  6802.7   0.035       0
Bank Sta=4686.7,4692.4
Exp/Cntr=0.3,0.1

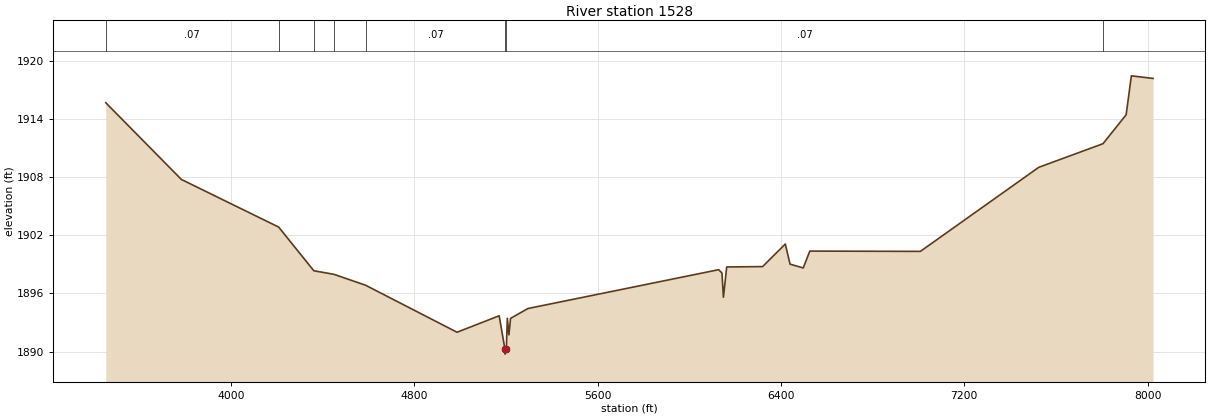
Type RM Length L Ch R = 1,1528,0,0,0
BEGIN DESCRIPTION:
South Fork Trib1 1.0
END DESCRIPTION:
XS GIS Cut Line= 5
      1437017.75      6899786.32      1438168.21      6898751.63
      1438338.70      6898570.83      1436914.52      6897412.31
      1436063.86      6897013.02
#Sta/Elev= 30
  3452.7 1915.69  3782.6 1907.77  4207.4 1902.85  4360.8 1898.34  4448.9 1897.97
  4587.2 1896.84  4986.0 1891.99  5169.9 1893.69  5195.2 1890.23  5195.7 1889.73
  5201.2 1890.23  5205.5 1893.43  5212.4 1891.72  5219.6 1893.42  5295.5 1894.44
  6127.9 1898.45  6142.3 1898.11  6148.8 1895.61  6163.1 1898.73  6319.7 1898.77
  6418.8 1901.10  6439.6 1899.02  6497.1 1898.63  6525.8 1900.37  7008.5 1900.34
  7525.1 1909.02  7805.6 1911.46  7906.7 1914.45  7929.5 1918.47  8024.1 1918.20
#Mann=8,-1,0
  3452.7    0.07       0  4207.4   0.035       0  4360.8    0.07       0
  4448.9   0.035       0  4587.2    0.07       0  5195.2    0.07       0
  5201.2    0.07       0  7805.6   0.035       0
Bank Sta=5195.2,5201.2
Exp/Cntr=0.3,0.1

Chan Stop Cuts=-1